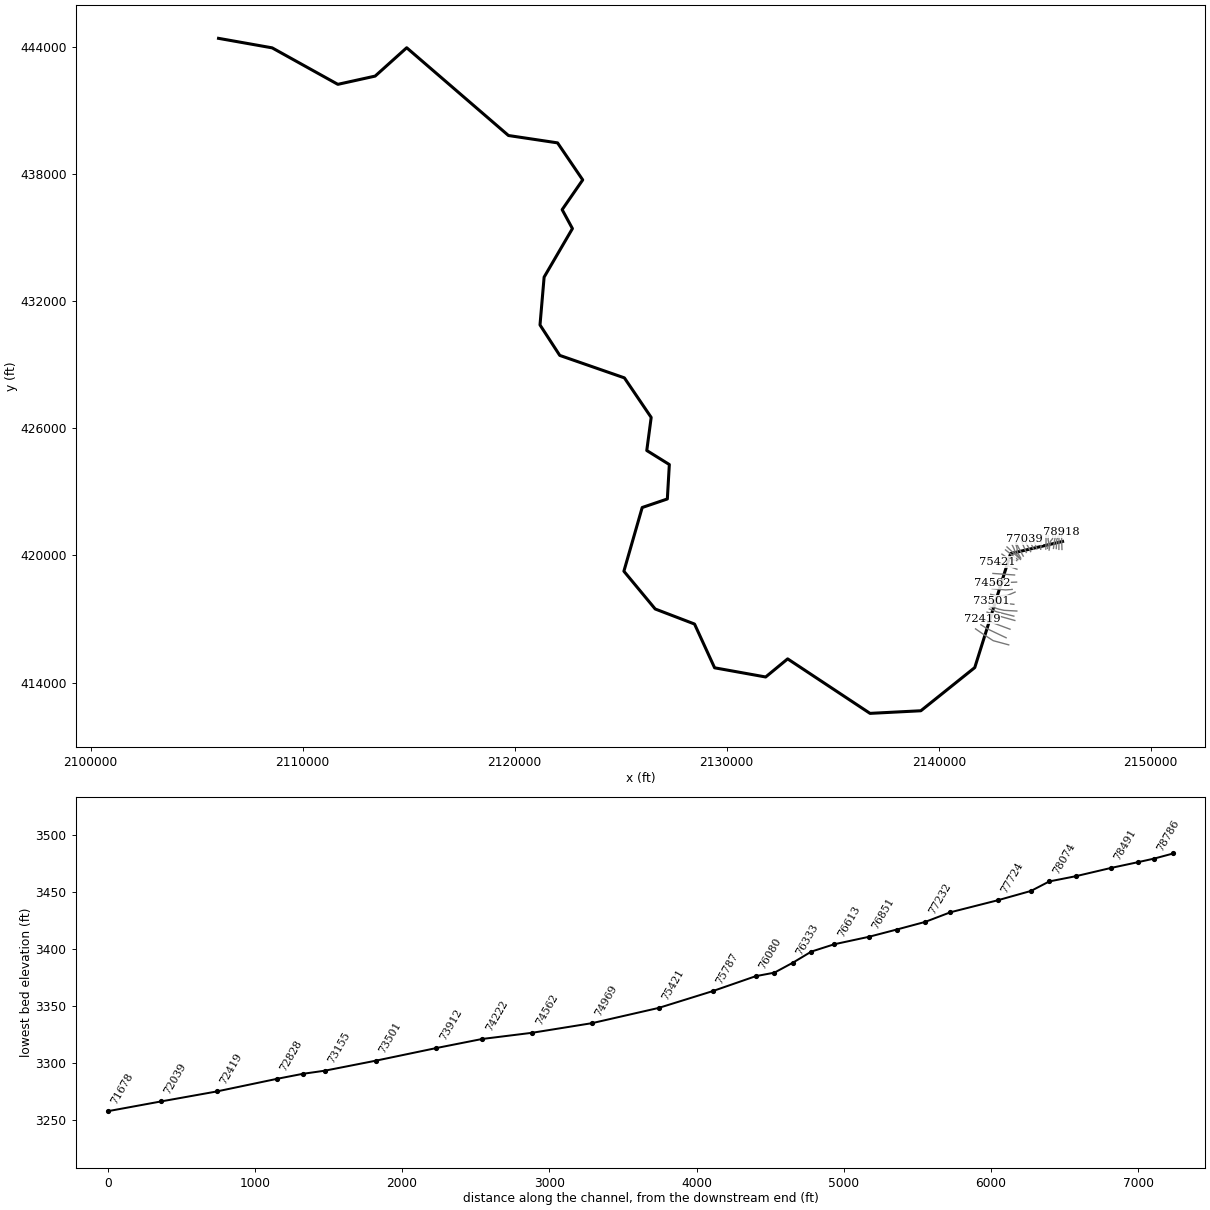
--- SFKCHERRYRV.prj (project) ---

Proj Title=SFKCHERRYRV
Current Plan=p01
Default Exp/Contr=0,0
English Units
Geom File=g01
Flow File=f01
Plan File=p01
Background Map Layer=stream
BEGIN DESCRIPTION:
Stream Name- South Fork Cherry River
Flood Zone: Zone A
Greenbrier County, WV
County-Wide Study
WVDHSEM-2018-3, Flood Risk Project
HEC-RAS Version: 5.0.7
General Notes:
For the Hydrology Regression was used.
END DESCRIPTION:
DSS Export Rating Curves= 0
DSS Export Rating Curve Sorted= 0
DSS Export Volume Flow Curves= 0
DXF Filename=..\..\..\..\Users\pratik.pathak\Desktop\DisasterStudies\ModelsCherry\SFKCHERRYRV\SFKCHERRYRV.
DXF OffsetX= 0
DXF OffsetY= 0
DXF ScaleX= 0
DXF ScaleY= 0

--- SFKCHERRYRV.p01 (plan) ---

Plan Title=Floodplain
Program Version=5.07
Short Identifier=Floodplain
Geom File=g01
Flow File=f01
Subcritical Flow
K Sum by GR= 0
Std Step Tol= 0.01
Critical Tol= 0.01
Num of Std Step Trials= 20
Max Error Tol= 0.3
Flow Tol Ratio= 0.001
Split Flow NTrial= 30
Split Flow Tol= 0.02
Split Flow Ratio= 0.02
Log Output Level= 0
Friction Slope Method= 1
Unsteady Friction Slope Method= 2
Unsteady Bridges Friction Slope Method= 1
Parabolic Critical Depth
Global Vel Dist= 0 , 0 , 0
Global Log Level= 0
CheckData=True
Encroach Param=-1 ,0,0, 0
Computation Interval=0.1SEC
Output Interval=1MIN
Instantaneous Interval=Max Profile
Mapping Interval=1HOUR
Computation Time Step Use Courant=        0
Computation Time Step Use Time Series=    0
Computation Time Step Count To Double=0
Computation Time Step Max Doubling=0
Computation Time Step Max Halving=0
Computation Time Step Residence Courant=0
Run HTab= 0
Run UNet= 0
Run Sediment= 0
Run PostProcess= 0
Run WQNet= 0
Run RASMapper= 0
UNET Theta= 0
UNET Theta Warmup= 0
UNET ZTol= 0
UNET ZSATol= 0
UNET MxIter= 0
UNET Max Iter WO Improvement= 0
UNET MaxInSteps= 0
UNET DtIC= 0
UNET DtMin= 0
UNET MaxCRTS= 0
UNET WFStab= 0
UNET SFStab= 0
UNET WFX= 1
UNET SFX= 1
UNET 1D Methodology=Finite Difference
UNET DSS MLevel= 1
UNET Pardiso=0
UNET DZMax Abort= 0
UNET Use Existing IB Tables= 0
UNET Froude Reduction=False
UNET Froude Limit= 0
UNET Froude Power= 0
UNET D1 Cores= 0
UNET D2 Coriolis=0
UNET D2 Cores= 0
UNET D2 Theta= 1
UNET D2 Theta Warmup= 1
UNET D2 Z Tol= 0.01
UNET D2 Volume Tol= 0.01
UNET D2 Max Iterations= 20
UNET D2 Equation= 0
UNET D2 RampUpFraction=0.1
UNET D2 TimeSlices= 1
UNET D2 BCVolumeCheck=0
UNET D1D2 MaxIter= 0
UNET D1D2 ZTol=0.01
UNET D1D2 QTol=0.1
UNET D1D2 MinQTol=1
DSS File=dss
Write IC File= 0
Write IC File at Fixed DateTime=0
Write IC File at Sim End=0
Echo Input=False
Echo Parameters=False
Echo Output=False
Write Detailed= 0
HDF Write Warmup=0
HDF Write Time Slices=0
HDF Flush=0
HDF Face Node Velocities=0
HDF Compression= 1
HDF Chunk Size= 1
HDF Spatial Parts= 1
HDF Use Max Rows=0
HDF Fixed Rows= 1
Calibration Method= 0
Calibration Iterations= 20
Calibration Max Change=0.05
Calibration Tolerance=0.2
Calibration Maximum=1.5
Calibration Minimum=0.5
Calibration Optimization Method= 1
WQ AD Non Conservative
WQ ULTIMATE=-1
WQ Max Comp Step=1HOUR
WQ Output Interval=15MIN
WQ Output Selected Increments= 0
WQ Output face flow=0
WQ Output face velocity=0
WQ Output face area=0
WQ Output face dispersion=0
WQ Output cell volume=0
WQ Output cell surface area=0
WQ Output cell continuity=0
WQ Output cumulative cell continuity=0
WQ Output face conc=0
WQ Output face dconc_dx=0
WQ Output face courant=0
WQ Output face peclet=0
WQ Output face adv mass=0
WQ Output face disp mass=0
WQ Output cell mass=0
WQ Output cell source sink temp=0
WQ Output nsm pathways=0
WQ Output nsm derived pathways=0
WQ Output MaxMinRange=-1
WQ Daily Max Min Mean=-1
WQ Daily Range=0
WQ Daily Time=0
WQ Create Restart=0
WQ Fixed Restart=0
WQ System Summary=0
WQ Write To DSS=0
WQ Use Fixed Temperature=0
Sorting and Armoring Iterations= 10
XS Update Threshold= 0.02
Bed Roughness Predictor= 0
Hydraulics Update Threshold= 0.02
Energy Slope Method= 1
Volume Change Method= 1
Sediment Retention Method= 0
XS Weighting Method= 0
Number of US Weighted Cross Sections= 1
Number of DS Weighted Cross Sections= 1
Upstream XS Weight=0
Main XS Weight=1
Downstream XS Weight=0
Number of DS XS's Weighted with US Boundary= 1
Upstream Boundary Weight= 1
Weight of XSs Associated with US Boundary= 0
Number of US XS's Weighted with DS Boundary= 1
Downstream Boundary Weight= 0.5
Weight of XSs Associated with DS Boundary= 0.5
Percentile Method= 0
Sediment Output Level= 3
Mass or Volume Output= 0
Output Increment Type= 1
Profile and TS Output Increment= 1
XS Output Flag= 0
XS Output Increment= 10
Write Gradation File= 0
Read Gradation Hotstart= 0
Write HDF5 File= 1
Write Binary Output= 1
Write DSS Sediment File= 0
SV Curve= 0
Specific Gage Flag= 0

--- SFKCHERRYRV.f01 (steady flow) ---

Flow Title=NFF Regression Equation
Program Version=5.07
Number of Profiles= 6
Profile Names=f1p,f10p,f4p,f2p,f02p,f1pplus
River Rch & RM=SFKCHERRYRV,Main            ,78918
     522     275     366     442     731     773
River Rch & RM=SFKCHERRYRV,Main            ,77950
     600     317     422     508     837     887
River Rch & RM=SFKCHERRYRV,Main            ,76458
     671     357     473     569     935     993
River Rch & RM=SFKCHERRYRV,Main            ,75421
     750     401     530     637    1040    1110
River Rch & RM=SFKCHERRYRV,Main            ,73155
     834     447     591     709    1160    1230
River Rch & RM=SFKCHERRYRV,Main            ,70251
    1020     551     725     868    1410    1510
River Rch & RM=SFKCHERRYRV,Main            ,68863
    1130     615     808     966    1560    1680
River Rch & RM=SFKCHERRYRV,Main            ,63626
    1380     755     988    1180    1900    2040
River Rch & RM=SFKCHERRYRV,Main            ,62089
    1530     842    1100    1310    2100    2270
River Rch & RM=SFKCHERRYRV,Main            ,58079
    1810     998    1300    1550    2470    2670
River Rch & RM=SFKCHERRYRV,Main            ,53834
    3210    1810    2340    2760    4340    4750
River Rch & RM=SFKCHERRYRV,Main            ,46931
    4030    2290    2940    3470    5420    5950
River Rch & RM=SFKCHERRYRV,Main            ,37279
    5180    2980    3810    4470    6950    7670
River Rch & RM=SFKCHERRYRV,Main            ,31911
    5860    3390    4320    5060    7840    8670
River Rch & RM=SFKCHERRYRV,Main            ,19173
    6560    3810    4840    5670    8750    9700
Boundary for River Rch & Prof#=SFKCHERRYRV,Main            , 1
Up Type= 0
Dn Type= 1
Dn Known WS=2239
Boundary for River Rch & Prof#=SFKCHERRYRV,Main            , 2
Up Type= 0
Dn Type= 1
Dn Known WS=2236
Boundary for River Rch & Prof#=SFKCHERRYRV,Main            , 3
Up Type= 0
Dn Type= 1
Dn Known WS=2237
Boundary for River Rch & Prof#=SFKCHERRYRV,Main            , 4
Up Type= 0
Dn Type= 1
Dn Known WS=2238
Boundary for River Rch & Prof#=SFKCHERRYRV,Main            , 5
Up Type= 0
Dn Type= 1
Dn Known WS=2241
Boundary for River Rch & Prof#=SFKCHERRYRV,Main            , 6
Up Type= 0
Dn Type= 1
Dn Known WS=2242.5
DSS Import GetInterval= 0
DSS Import GetPeak= 0
DSS Import FillOption= 0

--- SFKCHERRYRV.g01 (geometry) ---

Geom Title=USGS 10m DEM
Program Version=5.07

River Reach=SFKCHERRYRV     ,Main
Reach XY= 30
2145838.48200002420658.6550000012143387.57230879420086.037806675
2141698.41936006414709.8745444862139156.30250002412673.142500013
2136758.31834434412549.8237722962132873.67999999415120.391000018
2131836.71681154414266.2515992672129428.13500001414699.322999999
2128482.06199999416763.2370000032126626.20201254417473.214039296
2125150.18000004419254.3490000222126013.56000002422259.320999995
2127199.07300001422662.1050000042127293.41900003424285.692000002
2126229.05451368424947.7218344662126437.33499999426507.665999994
2125173.62900002428373.8860000072122125.03300002429433.327000022
 2121193.4787035430869.2930150182121387.75299999433125.912000015
2122722.87841745435414.660688221     2122237.936436307.703000009
2123208.09600522437710.5964638292122021.18900003439457.042000011
2119706.14300005439804.028000012    2114906.4465443943.471500024
2113418.52800001442606.1560000032111659.08300003442217.361000016
2108560.76700002443938.5470000062106032.08700004444387.307999998

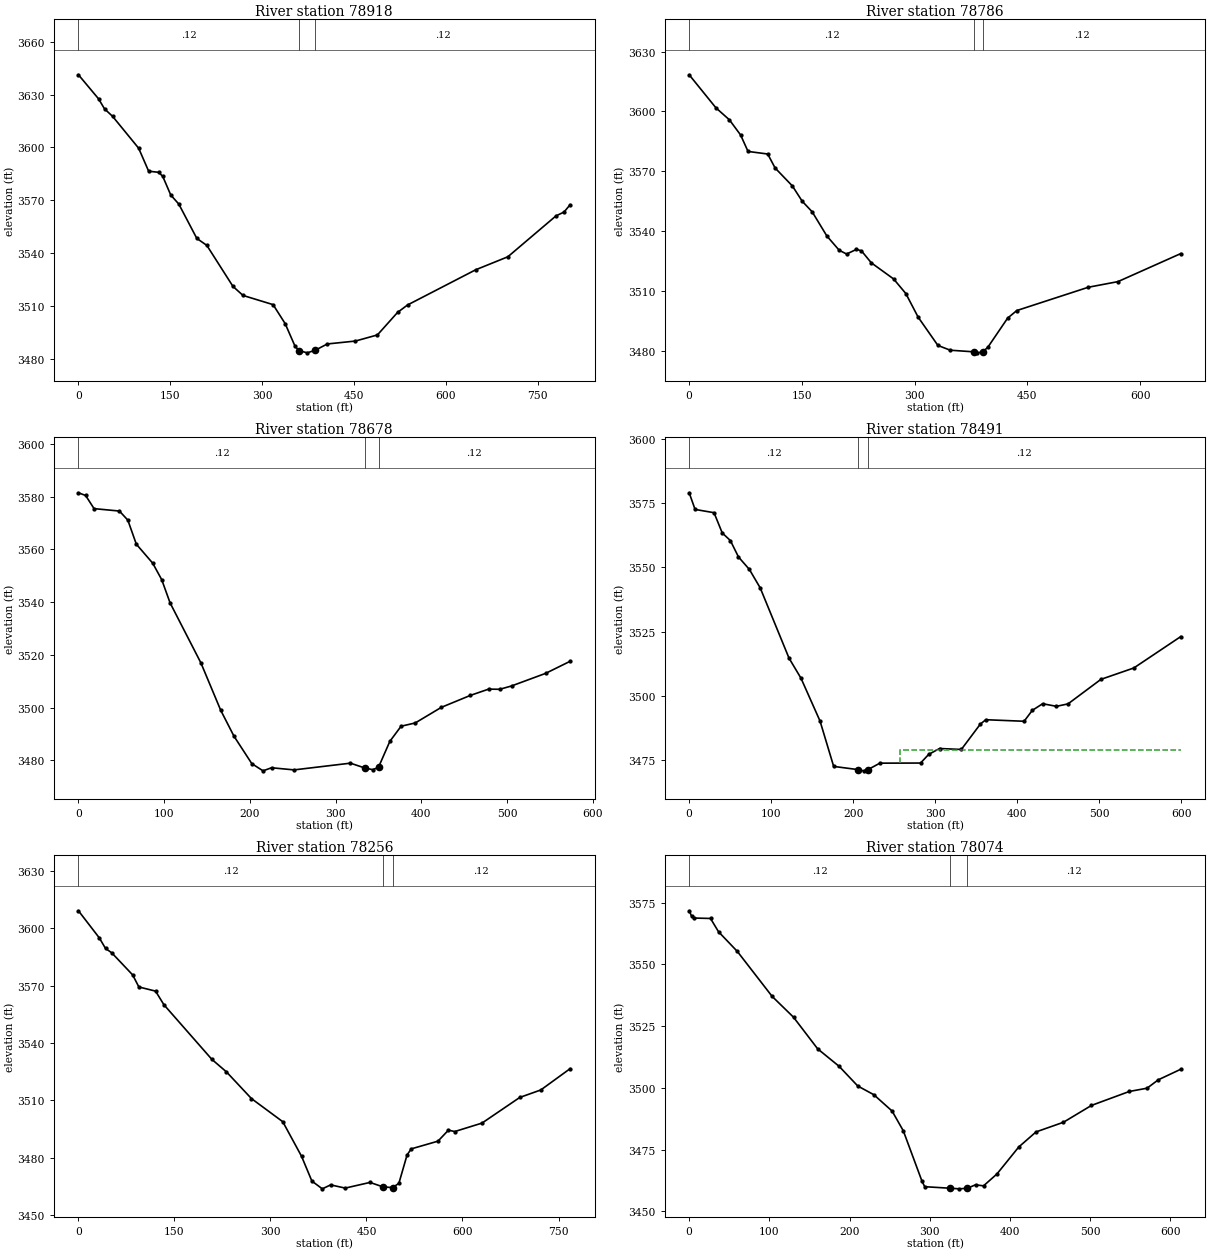
Type RM Length L Ch R = 1 ,78918   ,131.2,131.6,131.2
XS GIS Cut Line= 2
     2145811.294      420280.274     2145786.572      421082.368
#Sta/Elev= 30
       0 3641.18    32.8 3627.58    42.6 3621.86    55.7 3617.66    98.3 3599.58
   114.6 3586.57     131 3585.94   137.6 3583.65   150.7 3573.07   163.8 3567.97
   193.2 3548.52   209.6 3544.54   252.2 3521.34   268.6 3516.21   317.7    3511
   337.4 3500.26   353.7 3487.31   360.3 3484.97   373.4  3483.7   386.5 3485.16
   406.2 3488.73     452 3490.37     488 3493.84   520.8 3506.56   537.2 3510.81
   648.5 3530.75   700.9  3538.1   779.6  3561.3   792.6 3563.43   802.5 3567.57
#Mann= 3 ,-1 , 0
       0     .12       0   360.3     .04       0   386.5     .12       0
Bank Sta=360.3,386.5
XS Rating Curve= 0 ,0
Exp/Cntr=0.3,0.1

Type RM Length L Ch R = 1 ,78786   ,109.2,108.3,107.4
XS GIS Cut Line= 2
2145665.64995532420285.1273474782145670.53133075420939.231655003
#Sta/Elev= 30
       0 3618.36    35.6 3601.81    53.5 3595.81    68.4 3588.23    78.3 3579.98
   104.5 3578.69   114.3  3571.7   137.3  3562.7   150.4 3555.04   163.6 3549.77
   183.2 3537.64   199.6  3530.5   209.5 3528.61   222.6 3530.96   229.2 3530.21
   242.3 3524.21     272 3516.13   288.2 3508.85   304.6 3497.02   330.9 3482.85
   347.3 3480.46   379.5 3479.62   383.4 3479.14   390.6 3479.69   397.2 3481.86
   423.7 3496.53   435.9 3500.32     531 3511.98   570.4 3514.79   654.1 3528.85
#Mann= 3 , 0 , 0
       0     .12       0   379.5     .04       0   390.6     .12       0
Bank Sta=379.5,390.6
XS Rating Curve= 0 ,0
Exp/Cntr(USF)=0,0
Exp/Cntr=0.3,0.1

Type RM Length L Ch R = 1 ,78678   ,186.4,186.6,188.3
XS GIS Cut Line= 3
2145542.63929451 420322.225800742145563.14107131420718.593485599
2145610.97855052420888.465350539
#Sta/Elev= 30
       0 3581.49     8.4 3580.46    18.2 3575.48    47.8 3574.56    57.6 3571.12
    67.5    3562    86.6  3554.8    97.1 3548.56   106.9 3539.72   142.8 3516.99
     166 3498.96   181.4 3489.18   202.2 3478.77   215.3 3476.04   225.2 3477.21
   251.5  3476.4   317.2 3478.95   333.9 3477.13   343.4 3476.47     350 3477.43
   363.2 3487.23   376.3 3492.96   392.8  3494.2   423.2 3500.11   457.1 3504.65
   478.4 3507.03   491.4 3506.97   505.1 3508.23   544.9 3513.01   573.4 3517.58
#Mann= 3 , 0 , 0
       0     .12       0   333.9     .04       0     350     .12       0
Bank Sta=333.9,350
XS Rating Curve= 0 ,0
Exp/Cntr(USF)=0,0
Exp/Cntr=0.3,0.1

Type RM Length L Ch R = 1 ,78491   ,242,234.8,226.4
XS GIS Cut Line= 3
2145409.86588283420330.0360014272145459.65591221420693.210333367
2145503.58829107420921.658703458
#Sta/Elev= 30
       0 3578.92     7.2 3572.45    30.3 3571.18    40.3 3563.31    50.2 3560.36
    60.1 3553.98    73.4 3549.13    86.6 3541.95   121.7 3514.67   136.3 3506.86
   159.5 3490.22   176.1 3472.61   206.2 3471.35   212.5 3470.89   217.9 3471.37
   232.4 3473.87     282 3473.92     292 3477.31   305.2 3479.56   331.7  3479.2
   354.9 3489.07   361.5 3490.75   408.2 3490.15   418.2 3494.39   430.8 3496.97
   447.6 3495.95   461.7  3496.9   501.8 3506.43   541.9 3510.85   599.2 3523.07
#Mann= 3 , 0 , 0
       0     .12       0   206.2     .04       0   217.9     .12       0
#XS Ineff= 2 , 0
                          257.33         3479.08
Permanent Ineff=
       F       F
Bank Sta=206.2,217.9
XS Rating Curve= 0 ,0
Exp/Cntr(USF)=0,0
Exp/Cntr=0.3,0.1

Type RM Length L Ch R = 1 ,78256   ,167.9,182,197.9
XS GIS Cut Line= 4
      2145204.23      420252.805     2145267.408       420664.84
     2145363.549      420777.462     2145396.512      420977.986
#Sta/Elev= 30
       0 3609.14    32.6 3594.97    42.3 3589.46    52.1 3587.14    84.7 3575.61
    94.4 3569.31   120.5 3567.13   133.5 3560.03   208.4 3531.47   231.2 3524.92
   270.3 3510.95   319.2 3498.86   348.5 3480.82   364.7 3467.82     381 3463.76
     394 3465.83   416.8 3464.15   455.5 3467.11   475.7  3464.8   490.7 3464.41
   500.6 3466.62   513.4 3481.47   519.9 3484.65   561.7 3488.69     578 3494.44
   587.9 3493.72   630.5 3498.14   689.5 3511.55   722.3 3515.45   768.1 3526.58
#Mann= 3 , 0 , 0
       0     .12       0   475.7     .04       0   490.7     .12       0
Bank Sta=475.7,490.7
XS Rating Curve= 0 ,0
Exp/Cntr=0.3,0.1

Type RM Length L Ch R = 1 ,78074   ,130.1,124.2,122
XS GIS Cut Line= 4
 2145135.5325837420333.9411017712145185.32261308420598.511650038
2145156.03436051420758.6207641192145167.74966154420939.231655003
#Sta/Elev= 30
       0 3571.74     3.2 3569.43     6.6 3568.79    26.6 3568.63    36.6 3563.24
      60 3555.29   103.4 3537.08   130.1 3528.63   160.2 3515.82   186.9 3508.76
   210.2 3500.77   230.3 3497.23     253 3490.63     267 3482.61   290.3 3462.19
   293.7 3459.99   325.53459.363     337 3459.12     347 3459.38     357 3460.75
     367 3460.33   383.7 3465.13   410.9 3476.06   432.5 3482.18   466.6 3486.08
   501.6 3492.91   548.8 3498.56   570.9 3499.88   584.9 3503.28     613 3507.57
#Mann= 3 , 0 , 0
       0     .12       0   325.5     .04       0     347     .12       0
Bank Sta=325.5,347
XS Rating Curve= 0 ,0
Exp/Cntr(USF)=0,0
Exp/Cntr=0.3,0.1

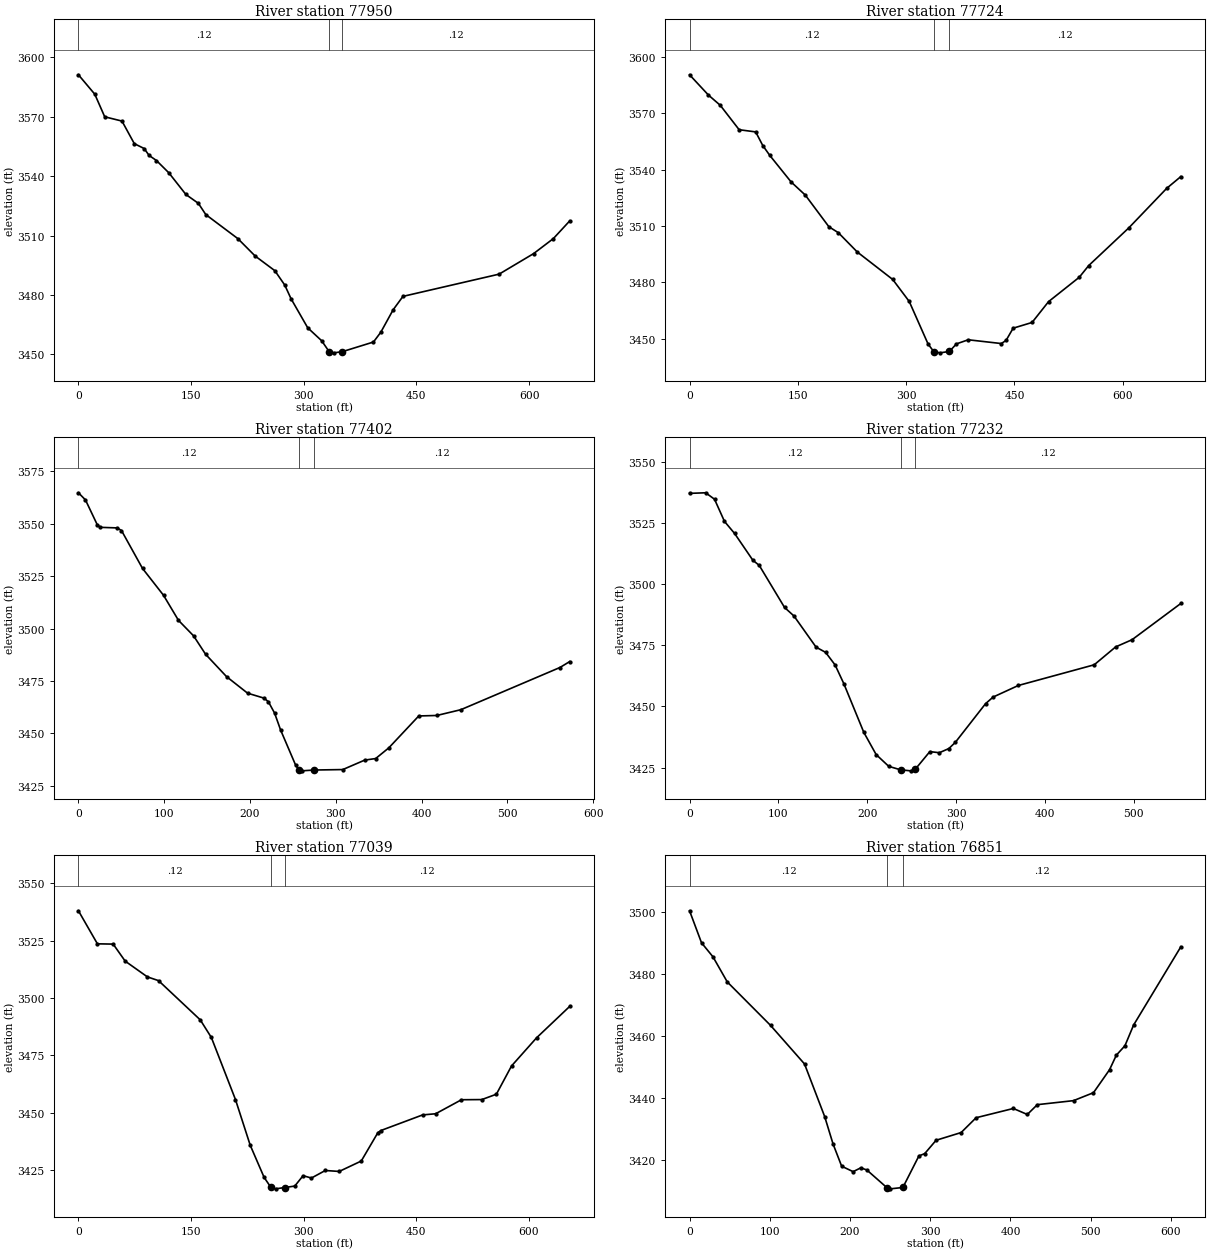
Type RM Length L Ch R = 1 ,77950   ,227.3,226.1,223.9
XS GIS Cut Line= 3
2145048.62544022420298.9055282092145059.84367466420588.977018808
2145058.24106974420952.768335746
#Sta/Elev= 30
       0 3591.15    21.8 3581.34      35 3569.94      58 3567.78    74.4 3556.39
    87.5 3553.93    94.1 3550.45   103.9 3547.87   120.3  3541.7   143.1 3530.73
   159.7 3526.26   169.6 3520.58   212.3 3508.44   235.3 3499.67   261.5 3492.27
   274.7 3485.02   283.1  3478.1   305.3 3463.43   323.9 3456.89   333.7 3451.45
   340.3  3450.8   351.5 3451.41   392.8 3456.26   402.6  3461.2     419 3472.52
   432.1  3479.3   560.1 3490.52     606 3500.88   632.3 3508.46   654.1 3517.39
#Mann= 3 , 0 , 0
       0     .12       0   333.7     .04       0   351.5     .12       0
Bank Sta=333.7,351.5
XS Rating Curve= 0 ,0
Exp/Cntr(USF)=0,0
Exp/Cntr=0.3,0.1

Type RM Length L Ch R = 1 ,77724   ,318.1,321.6,334.7
XS GIS Cut Line= 2
     2144808.676      420288.515     2144860.867      420966.998
#Sta/Elev= 30
       0 3590.37    26.2 3579.57    42.5 3574.16    68.7 3561.17    91.6 3560.01
   101.4 3552.78   111.2 3547.48   140.7  3533.4   160.3 3526.44     193 3509.61
   206.1 3506.44   232.3  3496.2   281.4 3481.59   304.3 3469.89   330.4 3447.27
   338.3 3443.23   346.8  3442.6   359.9 3443.33   369.7 3447.37     386 3449.54
   431.8 3447.54   438.4 3449.19   448.2  3455.7   474.4 3458.74   497.3 3469.83
   539.8 3482.77   552.9 3488.99   608.5 3509.04   660.9 3530.02   680.5 3536.28
#Mann= 3 ,-1 , 0
       0     .12       0   338.3     .04       0   359.9     .12       0
Bank Sta=338.3,359.9
XS Rating Curve= 0 ,0
Exp/Cntr=0.3,0.1

Type RM Length L Ch R = 1 ,77402   ,171,170.2,171.6
XS GIS Cut Line= 2
2144629.01854872420306.4931962652144429.94355405420843.239700882
#Sta/Elev= 30
       0 3564.81     8.2 3561.41    22.2 3549.34    25.7 3548.31    45.2 3548.04
    50.2 3546.78    74.7 3528.69    99.2 3515.86   116.6 3503.91   134.2 3496.51
   148.2 3487.71   172.6 3477.05   197.1 3469.15   216.2 3466.79   221.3  3465.1
   228.6 3459.64   235.6 3451.57   253.1 3434.81     257 3432.57   260.1 3432.07
   274.9 3432.46   308.1 3432.68   333.6 3437.19   346.4 3437.94   361.7 3443.04
   396.6 3458.27   417.6  3458.5   445.6 3461.25   561.1  3481.4   572.5 3484.24
#Mann= 3 , 0 , 0
       0     .12       0     257     .04       0   274.9     .12       0
Bank Sta=257,274.9
XS Rating Curve= 0 ,0
Exp/Cntr(USF)=0,0
Exp/Cntr=0.3,0.1

Type RM Length L Ch R = 1 ,77232   ,192.4,193.1,195.1
XS GIS Cut Line= 2
 2144467.6426379420294.3224981242144254.35646448420804.431929538
#Sta/Elev= 30
       0 3537.14    18.1 3537.38    28.1 3534.74    39.3 3525.67    50.7 3520.73
    71.3 3509.76    78.4  3507.7   106.9 3490.48   117.5 3486.99   142.4 3474.24
   153.1 3472.12   163.8 3466.96   173.6 3459.32   196.1  3439.4     210 3430.31
   224.2 3425.49   237.6 3424.07   248.8 3423.66   253.8 3424.22   270.4 3431.52
   281.1 3431.07   291.8 3432.77   299.1 3435.31   333.1 3451.12   341.6 3453.83
     370 3458.57   455.4 3467.03   479.5 3474.34     498 3477.29   552.9 3492.12
#Mann= 3 , 0 , 0
       0     .12       0   237.6     .04       0   253.8     .12       0
Bank Sta=237.6,253.8
XS Rating Curve= 0 ,0
Exp/Cntr(USF)=0,0
Exp/Cntr=0.3,0.1

Type RM Length L Ch R = 1 ,77039   ,189.8,188.7,187.8
XS GIS Cut Line= 2
2144333.36330407420180.2300159682144029.94157771420760.187999282
#Sta/Elev= 30
       0 3537.96    25.3 3523.58    46.3 3523.46    62.3 3516.05    91.9 3509.19
   106.7 3507.57   162.3  3490.5   177.1 3482.83   209.2 3455.84   228.9 3435.92
   247.4 3421.94   256.5 3417.57   262.7 3416.97   274.73417.543   288.2 3418.17
   299.3 3422.69   310.4 3421.67   328.9 3424.95   347.4 3424.54   376.8 3429.07
   398.8 3441.34   402.9 3442.34   458.5 3449.13   475.9 3449.64   510.3 3455.74
   537.4 3455.81   556.8 3458.14     577 3470.44   610.3 3482.67   654.5 3496.36
#Mann= 3 , 0 , 0
       0     .12       0   256.5     .04       0   274.7     .12       0
Bank Sta=256.5,274.7
XS Rating Curve= 0 ,0
Exp/Cntr(USF)=0,0
Exp/Cntr=0.3,0.1

Type RM Length L Ch R = 1 ,76851   ,235,237.1,238.2
XS GIS Cut Line= 2
2144126.38476043  420139.69002242143886.43781534420703.120997166
#Sta/Elev= 30
       0 3500.43    14.9 3490.09    29.2 3485.55      47 3477.45   100.9 3463.42
   143.3 3450.95   168.4 3433.97   178.9 3425.08   189.6 3417.92   203.9 3416.16
   213.4 3417.39   220.9 3416.72   246.7 3410.83   250.3 3410.61   265.9 3411.05
   285.9 3421.25   293.1 3421.98   307.3  3426.3   338.5 3428.79   357.2 3433.58
   403.6 3436.57     421 3434.63   433.5  3437.8   478.6  3439.1   503.5 3441.67
   523.5 3449.08     532 3453.79   542.7 3456.83   553.5 3463.52   612.4  3488.8
#Mann= 3 , 0 , 0
       0     .12       0   246.7     .04       0   265.9     .12       0
Bank Sta=246.7,265.9
XS Rating Curve= 0 ,0
Exp/Cntr(USF)=0,0
Exp/Cntr=0.3,0.1

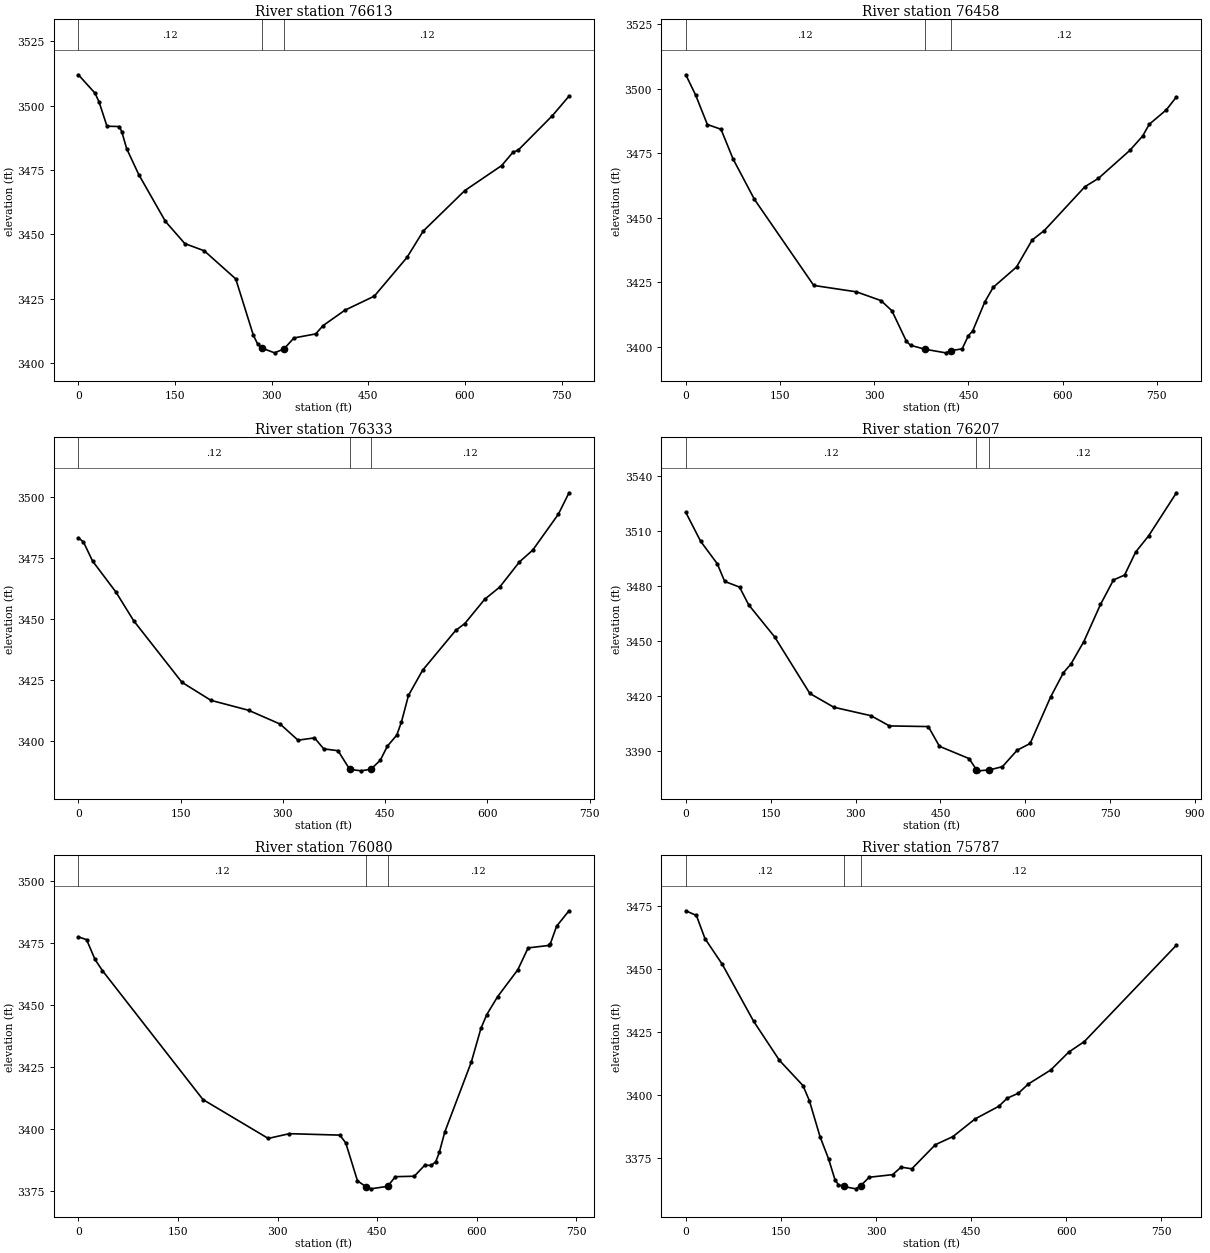
Type RM Length L Ch R = 1 ,76613   ,155.6,155.3,138.2
XS GIS Cut Line= 3
2143986.42927996419966.6585380552143749.36585312420389.249864164
2143638.04911356 420642.80465983
#Sta/Elev= 30
       03511.979  26.0353504.772  32.3273501.254  44.3763492.013  63.6553491.875
  67.4153489.811  74.9383483.287  93.7473473.215 135.1273455.028 165.222 3446.43
 195.3163443.641  244.223432.721 271.5413410.868 278.0763407.515 285.3673405.813
 304.4093404.012 319.1063405.532 334.5033409.788 368.3593411.367 379.6453414.562
 413.5013420.542 459.3043426.027 510.0363441.065 535.2163451.288 599.614 3466.99
 656.9433476.725 674.6533481.935 682.3463482.653 735.7713496.128 761.4583503.678
#Mann= 3 , 0 , 0
       0     .12       0 285.367     .04       0 319.106     .12       0
Bank Sta=285.367,319.106
XS Rating Curve= 0 ,0
Exp/Cntr=0.3,0.1

Type RM Length L Ch R = 1 ,76458   ,125.3,125.1,131.7
XS GIS Cut Line= 4
2143867.89565082419871.522583257 2143705.7510245 420155.69357784
2143692.37827181420332.8825509342143617.15653795420598.666010574
#Sta/Elev= 30
       0 3505.35    15.7 3497.46    34.3 3486.08      56 3484.24    75.2 3472.75
   109.2 3457.09   203.7 3423.71   271.7 3421.23   310.9 3417.82   328.2 3413.87
   351.2 3402.08   357.8 3400.51   380.8 3398.99   413.7 3397.59   422.8 3398.46
     440 3399.14   449.9 3404.27   456.6 3406.01   476.2  3417.4   489.4 3422.98
   526.6 3430.87   551.4 3441.32   570.7 3444.97   635.4 3461.97   656.8 3465.18
     707 3476.06   727.5 3481.66   737.7 3486.13     765 3491.75   781.1 3496.77
#Mann= 3 ,-1 , 0
       0     .12       0   380.8     .04       0   422.8     .12       0
Bank Sta=380.8,422.8
XS Rating Curve= 0 ,0
Exp/Cntr=0.3,0.1

Type RM Length L Ch R = 1 ,76333   ,123.1,125.7,140
XS GIS Cut Line= 4
2143812.26712197419884.9195105192143614.95586966420116.865184778
2143553.03372132420307.8792694622143459.62573486420500.992410021
#Sta/Elev= 30
       0 3483.22     7.5 3481.45    20.8 3473.69    55.3 3460.91    81.1 3449.28
   151.9  3424.1   194.5 3416.71   249.6 3412.66   296.2 3406.98   322.2 3400.42
   346.4 3401.36     360 3396.86   380.9 3396.12   398.1 3388.49     415 3387.88
   429.2 3388.56   442.9 3392.19   453.3 3397.95   467.1 3402.49     474 3407.89
   484.3 3418.75     505 3429.02   553.5  3445.3     567 3448.14   596.1 3458.05
     618    3463   647.1 3473.34   666.5 3478.14   704.2 3492.85   719.8 3501.61
#Mann= 3 , 0 , 0
       0     .12       0   398.1     .04       0   429.2     .12       0
Bank Sta=398.1,429.2
XS Rating Curve= 0 ,0
Exp/Cntr(USF)=0,0
Exp/Cntr=0.3,0.1

Type RM Length L Ch R = 1 ,76207   ,127.4,127.2,130.7
XS GIS Cut Line= 2
     2143855.503      419810.555     2143218.223      420398.391
#Sta/Elev= 30
       0 3520.27    26.2  3504.5    55.6 3492.23    68.7 3482.58    94.9 3479.48
   111.2 3469.75     157 3452.27   219.2 3421.38   261.7 3413.85   327.2 3409.24
   359.9 3403.66   428.6 3403.31   448.2 3392.53   500.6 3385.82   513.6 3379.77
   516.9 3379.13   536.6 3379.63   559.5 3381.41   585.6  3390.4   608.5 3394.07
   644.5 3419.34   667.4 3432.76   680.5 3437.41   703.4 3449.74   732.8 3469.98
   755.8 3483.38   775.4 3486.04     795 3498.63   817.9 3507.46     867 3530.98
#Mann= 3 , 0 , 0
       0     .12       0   513.6     .04       0   536.6     .12       0
Bank Sta=513.6,536.6
XS Rating Curve= 0 ,0
Exp/Cntr=0.3,0.1

Type RM Length L Ch R = 1 ,76080   ,293.4,293.2,309.8
XS GIS Cut Line= 2
 2143728.7812128419800.7477763642143149.08591155420259.312716156
#Sta/Elev= 30
       0 3477.36    12.4 3476.21    24.9 3468.35    36.1 3463.82   187.7 3411.92
     286  3396.3   317.8 3398.21   393.9 3397.63   402.8 3394.49   420.4 3379.27
  432.71 3376.96   440.2 3376.03   465.8 3377.03   477.5 3380.92     506  3381.1
   521.9 3385.55   531.4 3385.43   538.3 3386.91   543.7 3390.67     552  3398.9
     592 3427.06   606.4 3440.54   615.3 3446.12   631.5 3453.28     662 3464.13
   677.5 3472.91   708.8 3473.91   711.1 3474.65   720.4 3481.63   739.1 3487.84
#Mann= 3 , 0 , 0
       0     .12       0  432.71     .04       0   465.8     .12       0
Bank Sta=432.71,465.8
XS Rating Curve= 0 ,0
Exp/Cntr(USF)=0,0
Exp/Cntr=0.3,0.1

Type RM Length L Ch R = 1 ,75787   ,368.7,365.6,366.5
XS GIS Cut Line= 3
2143675.92653568419755.6162100232143285.19543003419846.483909012
2142980.13958342420060.672056628
#Sta/Elev= 30
       0 3473.04    16.7 3471.19    30.3 3461.99    57.7 3451.76   106.8 3429.34
   147.7 3413.78   184.8 3403.79   194.9 3397.83   211.7 3383.57   225.2 3374.75
   235.3  3366.5   240.8 3364.49     249 3363.82   268.1 3362.88   275.7 3364.06
   289.2 3367.47   326.2  3368.5   339.7 3371.48   356.5 3370.81   393.6 3380.36
   421.4 3383.58   456.3 3390.57   493.7 3395.58   507.1 3398.81   524.5 3400.74
   540.5 3404.45   575.6 3409.95   604.1 3417.06   628.7 3421.24   773.9 3459.41
#Mann= 3 , 0 , 0
       0     .12       0     249     .04       0   275.7     .12       0
Bank Sta=249,275.7
XS Rating Curve= 0 ,0
Exp/Cntr(USF)=0,0
Exp/Cntr=0.3,0.1

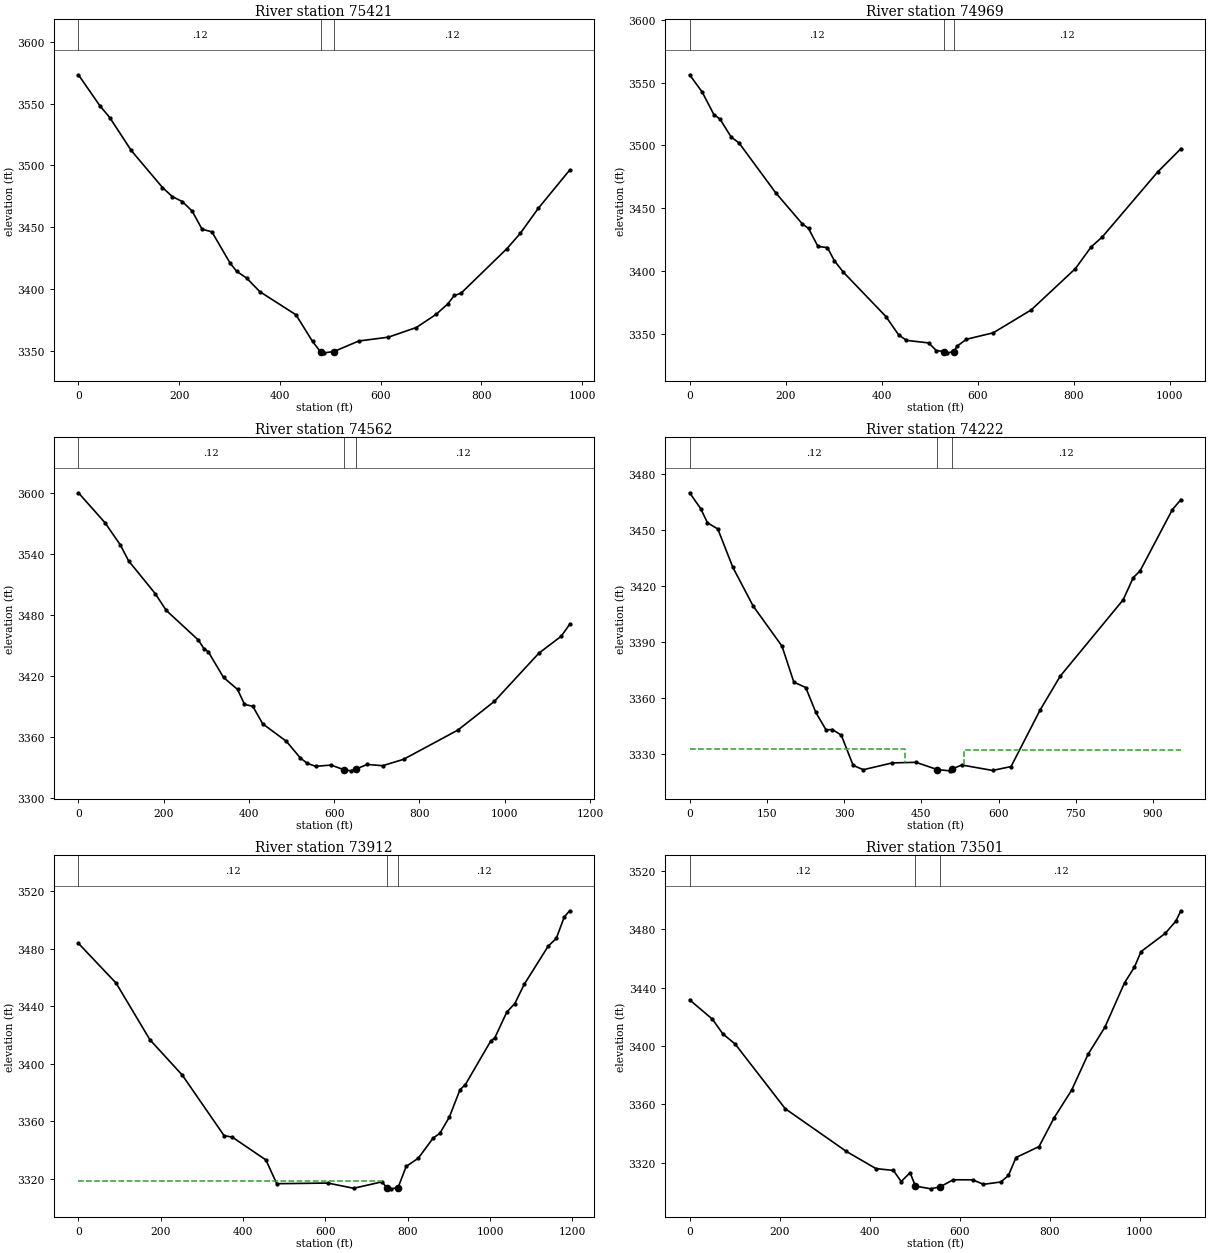
Type RM Length L Ch R = 1 ,75421   ,452.9,452.7,456.8
XS GIS Cut Line= 2
     2143687.943      419349.076     2142773.226      419686.944
#Sta/Elev= 30
       0 3573.51    42.5 3548.46    62.2 3538.86   104.7 3512.25   166.9 3482.15
   186.5 3474.77   206.2  3470.8   225.8 3463.04   245.4 3448.38     265 3446.22
     301 3420.99   314.1 3414.23   333.8  3408.8   359.9 3397.84   431.9 3378.99
   464.7 3357.44     481  3348.8   487.6  3348.2   507.2 3349.25   556.3 3357.77
   615.2 3360.89   670.8 3368.73   710.1 3379.42     733 3387.75   746.1 3394.71
   759.2 3396.39   850.8 3432.73     877 3444.95     913 3465.38   975.1 3496.27
#Mann= 3 ,-1 , 0
       0     .12       0     481     .04       0   507.2     .12       0
Bank Sta=481,507.2
XS Rating Curve= 0 ,0
Exp/Cntr=0.3,0.1

Type RM Length L Ch R = 1 ,74969   ,407.4,406.3,408.7
XS GIS Cut Line= 2
2143575.68503261419076.7641152632142555.11069285419149.842277864
#Sta/Elev= 30
       0 3556.23      26 3542.59    50.5 3524.59    63.5 3520.86    86.5 3506.67
   102.9 3501.98   179.4 3462.23   234.5 3437.62   247.7 3433.87   267.4 3419.52
   287.1 3418.62   301.6 3408.13     320 3399.15   408.8 3363.77   435.2 3349.25
   451.6 3344.78   497.7 3342.74     514 3336.66   530.5  3335.9   537.1 3334.84
   550.3 3335.85   556.9  3340.1   576.6 3345.65   632.5  3350.8   711.5 3369.01
   803.6 3401.91   836.4 3419.21   859.5 3427.07   974.6 3478.74  1023.2 3497.34
#Mann= 3 , 0 , 0
       0     .12       0   530.5     .04       0   550.3     .12       0
Bank Sta=530.5,550.3
XS Rating Curve= 0 ,0
Exp/Cntr(USF)=0,0
Exp/Cntr=0.3,0.1

Type RM Length L Ch R = 1 ,74562   ,343.3,339.9,339.7
XS GIS Cut Line= 2
     2143671.461      418742.012     2142520.512      418687.074
#Sta/Elev= 30
       0 3600.65    62.2  3571.2    98.2 3549.31   117.8 3533.44     180  3501.3
   206.2 3484.55   281.5 3455.35   294.6 3446.77   304.4 3444.02   340.4 3418.48
   373.2 3406.76   389.5 3392.04   409.2 3389.99   432.1 3372.86   487.8 3355.53
   520.5 3339.12   536.8  3333.8   556.5 3330.87   592.5  3332.1     622 3327.64
   638.3 3326.41   651.4 3328.23   677.6 3332.73   713.6 3331.48   762.7 3337.77
   890.4 3366.68   975.5 3394.83  1080.2 3442.51  1132.6 3459.17  1152.3 3470.96
#Mann= 3 ,-1 , 0
       0     .12       0     622     .04       0   651.4     .12       0
Bank Sta=622,651.4
XS Rating Curve= 0 ,0
Exp/Cntr=0.3,0.1

Type RM Length L Ch R = 1 ,74222   ,311.8,310.6,313.5
XS GIS Cut Line= 4
2143464.80782039418396.3812220862143147.29580358418371.181855672
2142751.66575088418411.5008419342142514.79170659418434.180271707
#Sta/Elev= 30
       0 3469.71    21.6  3461.2    34.6 3453.68    54.8 3450.34    83.9 3429.86
   123.4 3409.13   179.4 3387.68   202.4 3368.45   225.5 3365.53   245.2  3352.2
   264.9 3342.89   277.4 3343.06   294.6 3340.04   317.6 3323.89   337.4 3321.57
   393.5 3325.21   439.6 3325.53   481.43321.619   505.6 3320.97   508.83321.872
   528.7 3324.09   588.4 3321.18   624.3 3323.26   680.5 3353.39   719.9 3371.66
   841.9  3412.4   861.7 3424.33   874.8 3427.89   937.5 3460.65   954.1 3466.04
#Mann= 3 , 0 , 0
       0     .12       0   481.4     .04       0   508.8     .12       0
#XS Ineff= 2 , 0
          417.66 3332.65  533.11         3332.04
Permanent Ineff=
       F       F
Bank Sta=481.4,508.8
XS Rating Curve= 0 ,0
Exp/Cntr(USF)=0,0
Exp/Cntr=0.3,0.1

Type RM Length L Ch R = 1 ,73912   ,413.4,410.8,396
XS GIS Cut Line= 4
     2143600.042      418269.546     2143223.717      418107.479
     2142729.276      418093.745     2142449.093      418165.164
#Sta/Elev= 30
       0 3483.83    91.8 3456.06   173.7 3416.75   252.4 3392.14     354 3350.02
   373.7 3349.03   455.6 3333.11   481.8 3316.61   606.3 3317.04   668.5 3313.42
   737.3 3317.89   750.4 3313.51   760.2 3313.03   776.6 3313.91   796.3 3328.62
   825.8 3334.35   861.8 3348.34   878.2 3351.67   901.1 3362.88   927.1 3382.01
   940.1 3385.53  1001.8 3415.88  1011.6 3418.05  1040.8    3436  1060.3 3441.92
    1083 3455.23  1141.5  3481.9    1161 3487.22  1180.5 3502.22  1193.5 3506.46
#Mann= 3 ,-1 , 0
       0     .12       0   750.4     .04       0   776.6     .12       0
#XS Ineff= 2 , 0
           736.6 3318.58
Permanent Ineff=
       F       F
Bank Sta=750.4,776.6
XS Rating Curve= 0 ,0
Exp/Cntr=0.3,0.1

Type RM Length L Ch R = 1 ,73501   ,348.5,345.9,347.9
XS GIS Cut Line= 3
2143542.92585628417693.3188991372142880.18251959417768.916998378
2142464.39297376417852.074907544
#Sta/Elev= 30
       0 3431.57    50.6 3418.35    73.7  3408.3   101.2 3401.26   212.4 3356.92
   348.4 3327.58   413.8 3315.86   452.8 3314.56   469.9 3306.94   489.7 3313.06
   501.4 3303.87     536 3301.96   557.1 3303.47   585.5 3308.18   628.8 3308.14
   652.5 3305.06   691.5 3306.66   708.2 3311.17     725 3323.45   776.1 3330.95
   809.5 3350.62   848.6 3369.69   884.8 3394.15   922.4 3412.84   966.1 3443.33
     988    3454  1002.7  3464.7  1056.2 3477.11    1080 3485.59  1091.1 3492.68
#Mann= 3 , 0 , 0
       0     .12       0   501.4     .04       0   557.1     .12       0
Bank Sta=501.4,557.1
XS Rating Curve= 0 ,0
Exp/Cntr(USF)=0,0
Exp/Cntr=0.3,0.1

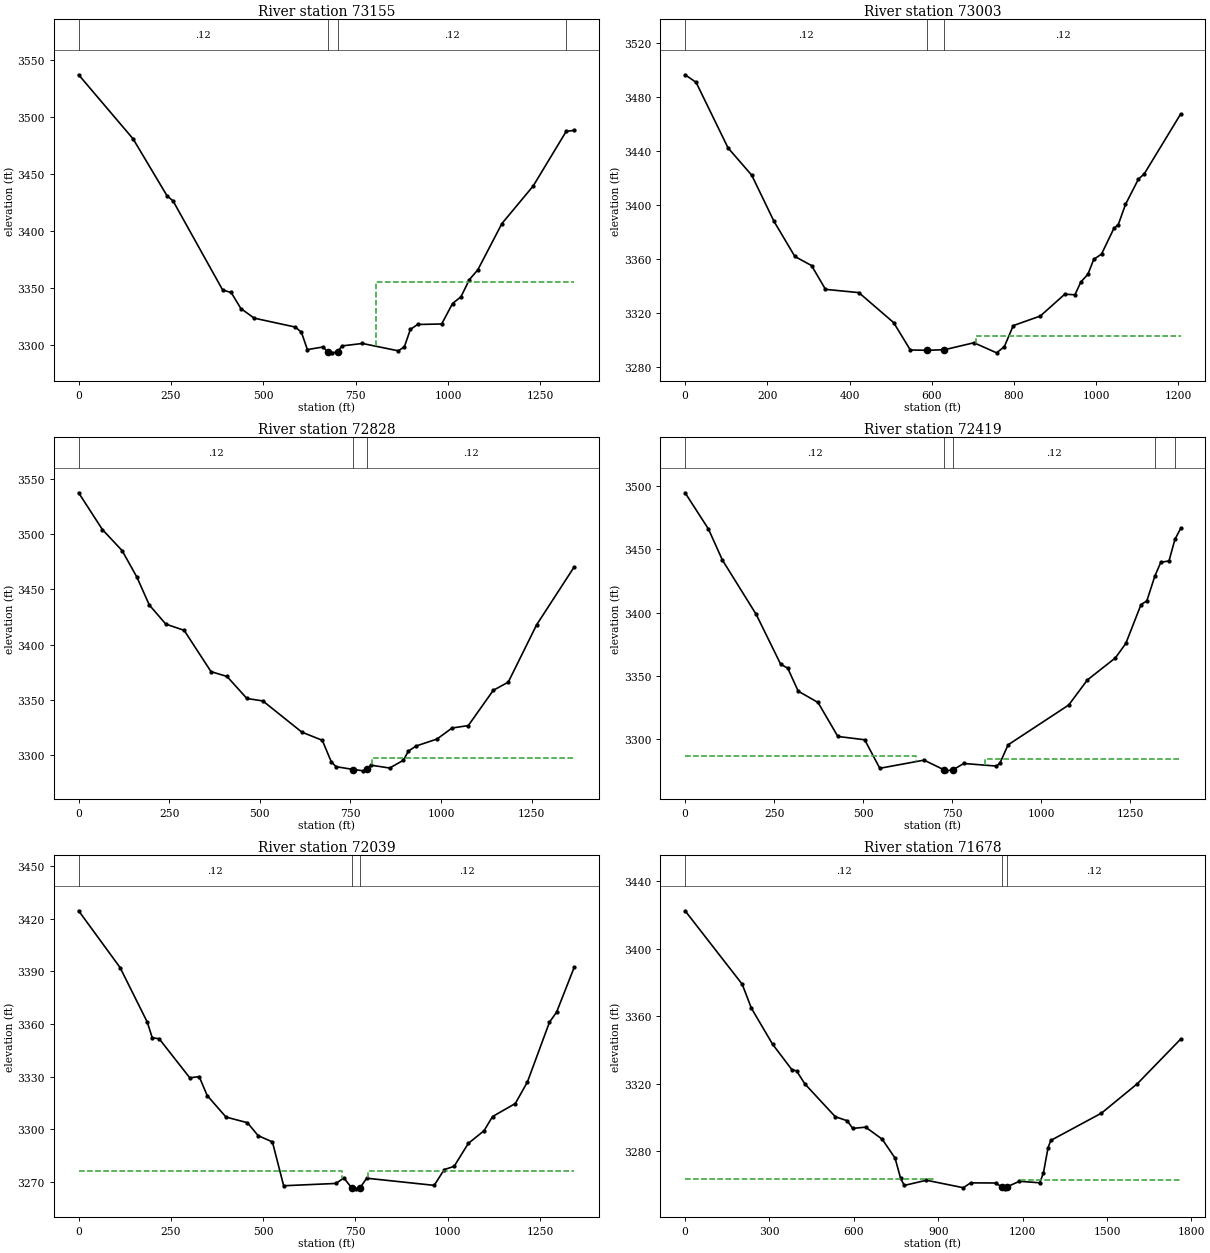
Type RM Length L Ch R = 1 ,73155   ,150.8,151.7,151.1
XS GIS Cut Line= 4
     2143682.449      417376.805     2143083.626      417409.767
     2142833.658      417464.705     2142369.433      417607.544
#Sta/Elev= 30
       0 3536.65   147.5  3480.5   239.2 3430.75   255.6  3426.2     390 3348.13
   412.9 3346.04   439.2 3331.97   475.2 3323.57   586.6 3315.75     603 3311.25
   619.2 3296.01   661.3 3298.32   674.2 3294.09   687.2 3293.19  701.16 3294.27
   713.1 3299.26   768.2  3301.4   865.4 3294.94   881.7 3298.44     898 3313.69
   917.6 3318.02   982.8 3318.45  1012.1 3336.36    1035  3342.3  1057.8 3357.34
  1080.6 3365.89  1145.8 3406.39  1230.5  3439.3 1319.93 3487.16  1341.4 3487.92
#Mann= 4 ,-1 , 0
       0     .12       0   674.2     .04       0  701.16     .12       0
 1319.93     .08       0
#XS Ineff= 2 , 0
                          805.77         3355.23
Permanent Ineff=
       F       F
Bank Sta=674.2,701.16
XS Rating Curve= 0 ,0
Exp/Cntr=0.3,0.1

Type RM Length L Ch R = 1 ,73003   ,175.8,175.9,175.8
XS GIS Cut Line= 3
2143541.53673403417136.5115996742142745.66332769417337.948541231
2142386.23662805417474.214707579
#Sta/Elev= 30
       0 3496.44    26.7 3490.86   104.5 3442.24   162.1 3422.02   216.2 3387.85
     267  3361.8   307.6 3355.07   341.5 3337.44   422.7 3335.01   507.3 3312.79
   547.9  3292.5   588.5 3292.29   630.73292.689   702.7 3297.86   757.7 3290.39
   776.4 3294.91   798.3 3310.57   864.2 3317.69   923.6 3333.85   948.4 3333.41
   962.4 3342.76   979.9 3348.66     994 3359.61    1013 3363.61  1043.1 3382.66
  1053.7 3385.39  1071.2 3400.32  1102.7 3419.13  1116.8 3422.96  1205.4 3467.34
#Mann= 3 , 0 , 0
       0     .12       0   588.5     .04       0   630.7     .12       0
#XS Ineff= 2 , 0
                           708.4          3302.7
Permanent Ineff=
       F       F
Bank Sta=588.5,630.7
XS Rating Curve= 0 ,0
Exp/Cntr(USF)=0,0
Exp/Cntr=0.3,0.1

Type RM Length L Ch R = 1 ,72828   ,412.2,408.9,410.3
XS GIS Cut Line= 3
2143588.60577885416931.4863761762142992.60577796417097.584737081
2142279.35987525417324.748671847
#Sta/Elev= 30
       0 3537.11    65.5 3503.92     120 3484.87   160.9 3460.85   194.9 3435.81
   240.5 3418.52   291.1 3412.88   365.2 3375.61   409.5 3371.19   464.2 3351.34
   508.3 3349.11     616 3320.92   672.3 3313.55     697 3294.21   710.2 3289.74
   758.4 3287.17     786 3285.98   796.3 3287.41   806.6  3291.1   858.3 3288.51
   896.1 3295.56   909.9 3303.75   930.6 3308.33   989.1 3314.74  1030.4 3324.66
  1075.2 3326.87  1144.1 3358.71  1185.4 3366.06  1263.7 3417.85  1367.3 3470.13
#Mann= 3 , 0 , 0
       0     .12       0   758.4     .04       0   796.3     .12       0
#XS Ineff= 2 , 0
                          809.44         3297.69
Permanent Ineff=
       F       F
Bank Sta=758.4,796.3
XS Rating Curve= 0 ,0
Exp/Cntr(USF)=0,0
Exp/Cntr=0.3,0.1

Type RM Length L Ch R = 1 ,72419   ,381.3,379.7,379
XS GIS Cut Line= 2
     2143361.062      416519.773     2142056.286      417005.974
#Sta/Elev= 30
       0 3494.75    65.5 3466.15   104.8 3441.56   199.8 3398.59   268.7 3359.13
   288.3 3356.15   317.8 3337.92   373.5 3328.95   429.2  3302.1   504.6 3299.49
   547.1 3276.94   671.6 3283.38   727.3 3275.74   733.9 3274.92   753.5 3275.84
     783 3280.73   874.8 3278.69   884.6 3280.98   907.5 3295.46  1077.9 3326.96
  1130.3 3346.76    1209 3364.19  1238.4 3375.67    1281 3406.32  1297.4 3409.25
 1320.05    3429  1336.7  3439.8  1359.7 3440.86 1376.41 3457.98  1392.4 3466.54
#Mann= 5 ,-1 , 0
       0     .12       0   727.3     .04       0   753.5     .12       0
 1320.05     .08       0 1376.41     .12       0
#XS Ineff= 2 , 0
          649.17 3287.01  842.88          3284.5
Permanent Ineff=
       F       F
Bank Sta=727.3,753.5
XS Rating Curve= 0 ,0
Exp/Cntr=0.3,0.1

Type RM Length L Ch R = 1 ,72039   ,362.2,360.4,358.4
XS GIS Cut Line= 3
2143177.53504327416115.8385616222142328.31639512416519.028424246
2141985.60501189416730.703102123
#Sta/Elev= 30
       0 3424.57   112.4  3392.2   186.2 3361.04   199.5  3352.2   218.2 3351.67
   301.2  3329.4   326.7 3330.07   348.4  3319.3   399.3 3307.04   457.4 3303.82
   486.5 3296.45   525.2 3292.86   555.6  3267.9   697.1 3269.21   718.9 3272.32
   740.83266.446   751.6 3266.14   761.83266.479   780.6 3272.19   963.6 3268.12
   990.6 3277.09  1017.6 3278.97  1056.1 3292.06  1098.6 3299.23  1121.7 3307.33
  1183.4 3314.75  1216.3 3327.09  1275.9 3361.07  1295.2  3366.8  1342.9 3392.31
#Mann= 3 , 0 , 0
       0     .12       0   740.8     .04       0   761.8     .12       0
#XS Ineff= 2 , 0
          714.81 3276.26  782.85         3276.04
Permanent Ineff=
       F       F
Bank Sta=740.8,761.8
XS Rating Curve= 0 ,0
Exp/Cntr(USF)=0,0
Exp/Cntr=0.3,0.1

Type RM Length L Ch R = 1 ,71678   ,468,468,470.8
XS GIS Cut Line= 4
      2143300.63      415780.858     2142567.209      415978.634
     2142081.008      416294.528     2141734.899      416536.254
#Sta/Elev= 30
       0 3422.49     203 3378.94   235.7  3364.7     311 3343.37   379.8 3328.21
   396.2 3327.56   425.6 3319.86   533.7  3300.4   576.3 3297.97   595.9 3293.43
   641.8 3294.18   700.7 3287.04   746.5 3275.79   766.2 3263.76   779.3 3259.63
   857.9  3262.7   988.9 3258.26  1015.1 3261.14  1103.6 3261.07  1126.5 3258.66
  1136.3  3257.6  1142.9  3258.7  1188.7 3262.09  1260.8 3261.18  1273.9 3267.07
  1290.3 3282.04  1300.1 3286.32  1480.2  3302.5  1607.8 3319.96  1761.6 3346.38
#Mann= 3 ,-1 , 0
       0     .12       0  1126.5     .04       0  1142.9     .12       0
#XS Ineff= 2 , 0
          880.85 3263.31 1193.62         3262.97
Permanent Ineff=
       F       F
Bank Sta=1126.5,1142.9
XS Rating Curve= 0 ,0
Exp/Cntr=0.3,0.1