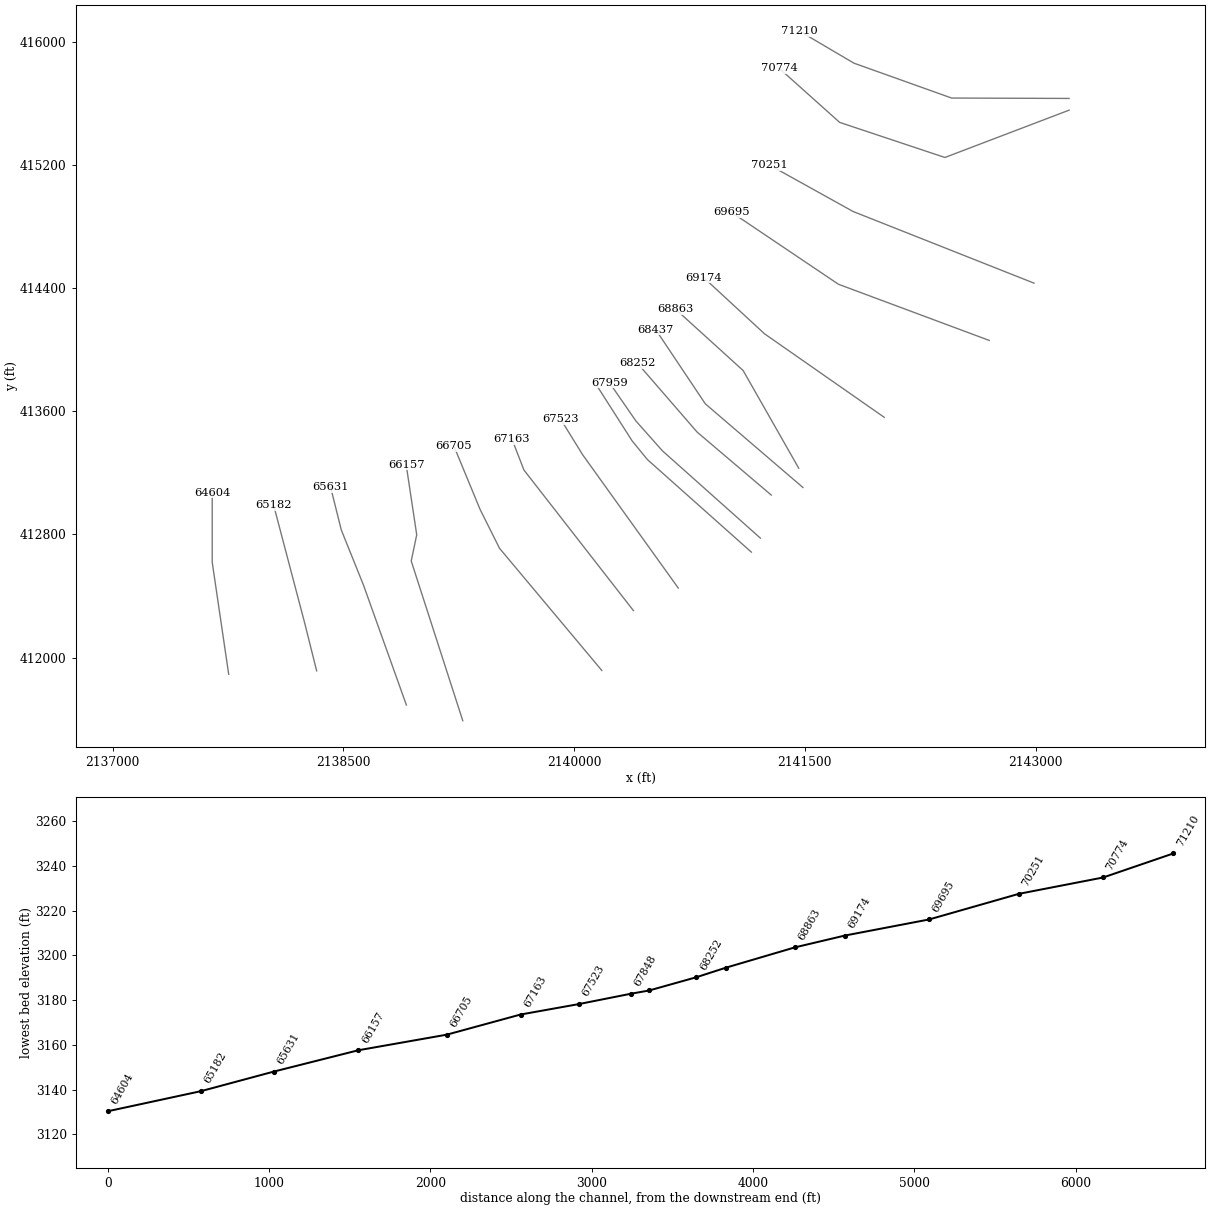
HEC-RAS study SFKCHERRYRV.prj: SFKCHERRYRV

--- SFKCHERRYRV.g01 (geometry) --- (continued)

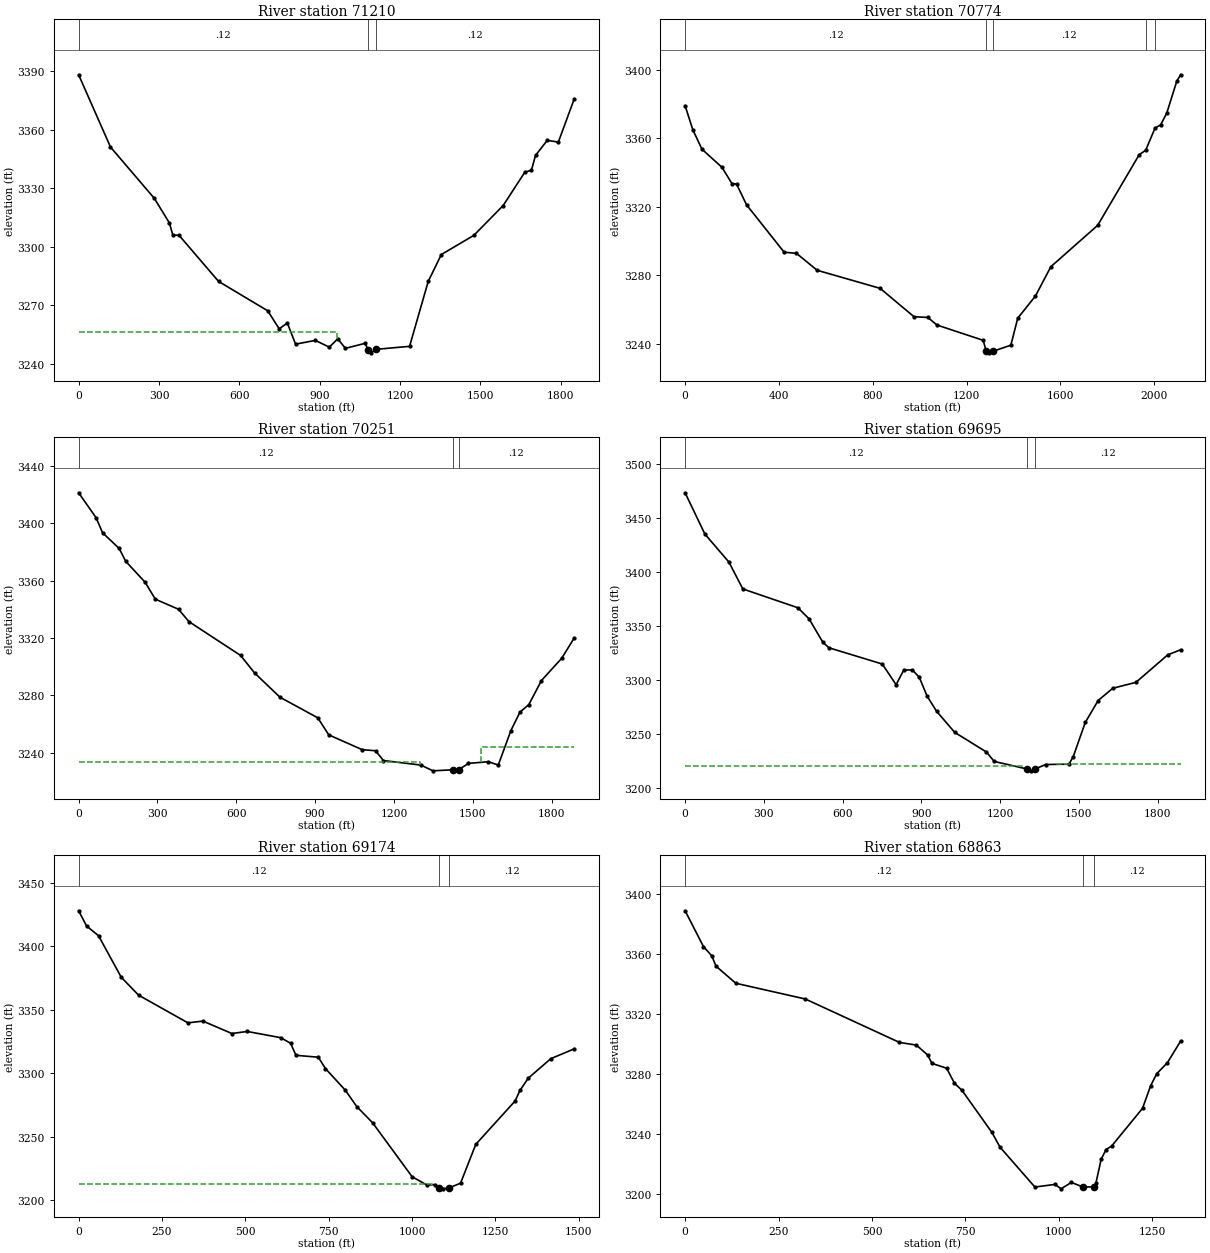
Type RM Length L Ch R = 1 ,71210   ,428.3,436.2,436.9
XS GIS Cut Line= 4
2143217.85402954415634.5306631162142454.31322719415637.050599757
2141819.28919356415863.8448974832141463.97812712416072.999638719
#Sta/Elev= 30
       0 3388.12   118.9 3351.08   282.7 3324.75   338.7 3312.19   351.8 3305.94
   374.8 3305.84   522.4 3282.19   706.1 3267.11   748.8 3257.89   779.3 3260.86
     810    3250   883.7 3251.94     936 3248.47   967.4 3252.76   996.1 3247.87
  1069.3 3250.42 1081.13  3247.2  1091.2 3245.56 1109.68 3247.35  1235.6 3248.89
  1305.4 3282.23  1354.2 3295.96  1475.7  3305.8    1585 3321.07  1666.1 3338.21
  1690.5 3339.14    1706 3346.82  1749.8  3354.5  1791.1 3353.61  1850.2 3375.65
#Mann= 3 , 0 , 0
       0     .12       0 1081.13     .04       0 1109.68     .12       0
#XS Ineff= 2 , 0
          964.35 3256.33
Permanent Ineff=
       F       F
Bank Sta=1081.13,1109.68
XS Rating Curve= 0 ,0
Exp/Cntr(USF)=0,0
Exp/Cntr=0.3,0.1

Type RM Length L Ch R = 1 ,70774   ,529.8,523.1,523.1
XS GIS Cut Line= 4
     2143218.223      415558.359     2142410.636      415250.707
     2141726.659      415478.699     2141333.853      415830.302
#Sta/Elev= 30
       0 3379.07    32.7 3365.05      72 3353.61   157.1 3343.07   199.7 3333.56
   219.3 3333.32   261.9 3321.19   422.3  3293.5   474.7 3292.86     563 3282.97
   831.5 3272.42   975.6 3255.87  1034.6 3255.45  1073.9 3251.01  1270.6  3242.1
  1283.7 3235.77  1293.5 3234.79  1313.2 3235.73  1388.6 3239.26    1418 3255.01
  1493.4 3267.93    1559 3285.04  1758.7  3309.2  1935.5 3350.37 1963.48 3353.04
 2003.12 3365.94  2027.2 3367.84  2053.4  3374.8    2096 3393.34  2112.4 3397.07
#Mann= 5 ,-1 , 0
       0     .12       0  1283.7     .04       0  1313.2     .12       0
 1963.48     .06       0 2003.12     .12       0
Bank Sta=1283.7,1313.2
XS Rating Curve= 0 ,0
Exp/Cntr=0.3,0.1

Type RM Length L Ch R = 1 ,70251   ,558.7,555.8,554
XS GIS Cut Line= 3
 2142989.9018044414433.7921584882141813.82408558414899.532337737
2141271.01898458415201.090727179
#Sta/Elev= 30
       0 3421.16    66.2 3403.85    91.2 3393.28   154.4 3382.36   179.1 3373.46
   253.2  3358.8     292 3347.04   380.2 3340.02   419.8 3331.41   616.6 3307.83
   669.6 3295.64   766.1 3278.77   910.2 3264.39   951.9 3252.53  1078.9 3242.24
    1130 3241.45  1160.1 3234.63  1302.7 3231.48  1348.6 3227.47  1423.4 3228.21
  1446.1 3228.24  1483.7 3232.66  1558.5  3233.8  1597.1 3231.54  1645.1 3255.52
  1679.6 3268.36  1713.4 3273.62  1761.4 3290.39  1838.3 3305.84  1885.9 3319.95
#Mann= 3 , 0 , 0
       0     .12       0  1423.4     .04       0  1446.1     .12       0
#XS Ineff= 2 , 0
         1298.25 3233.61 1531.41         3244.32
Permanent Ineff=
       F       F
Bank Sta=1423.4,1446.1
XS Rating Curve= 0 ,0
Exp/Cntr(USF)=0,0
Exp/Cntr=0.3,0.1

Type RM Length L Ch R = 1 ,69695   ,527.3,521.8,521.9
XS GIS Cut Line= 3
      2142699.06      414061.301     2141718.418      414426.638
     2141020.706      414896.357
#Sta/Elev= 30
       0 3473.24    75.4 3435.04   167.3    3409   219.8  3384.3   429.8 3366.86
   472.4 3356.57   524.9 3334.89   547.8 3329.86   751.2 3314.83   803.7 3295.68
   833.2 3309.36   866.1 3309.32   892.3 3302.46   921.8 3285.13   957.9 3271.14
  1026.8 3251.65  1147.9 3233.43  1177.4 3224.73  1301.8 3217.79  1318.1 3216.03
  1334.5 3217.92  1373.8 3221.89  1462.1 3222.21  1478.5 3229.14  1524.3 3260.78
  1573.4 3281.09    1629  3292.4  1717.4  3297.9  1838.5 3323.33  1887.6 3328.02
#Mann= 3 , 0 , 0
       0     .12       0  1301.8     .04       0  1334.5     .12       0
#XS Ineff= 2 , 0
         1285.11 3220.78 1412.77          3222.8
Permanent Ineff=
       F       F
Bank Sta=1301.8,1334.5
XS Rating Curve= 0 ,0
Exp/Cntr=0.3,0.1

Type RM Length L Ch R = 1 ,69174   ,315.7,311.1,315.5
XS GIS Cut Line= 3
2142016.12482912413561.6530613572141238.10418436414104.458162353
2140843.06269419414469.343813577
#Sta/Elev= 30
       0 3427.86    23.8 3415.88    59.8 3408.16   127.8 3375.49   179.8 3361.41
   327.8 3339.59   372.6 3340.97   459.7 3331.19   505.6  3332.8   605.9 3327.92
   635.8 3323.51   651.8 3314.03     719 3312.51   740.2 3303.61   799.9 3286.55
   834.4  3273.6   881.6 3260.93  1000.5 3218.32  1045.1 3211.78  1068.2 3212.19
  1081.8 3209.74  1092.4 3208.84  1111.7 3209.62  1145.6  3213.3  1191.3 3243.89
  1309.5 3278.12  1323.7 3286.34  1348.7    3296  1416.3 3311.37  1486.4 3319.08
#Mann= 3 , 0 , 0
       0     .12       0  1081.8     .04       0  1111.7     .12       0
#XS Ineff= 2 , 0
         1060.54 3212.57
Permanent Ineff=
       F       F
Bank Sta=1081.8,1111.7
XS Rating Curve= 0 ,0
Exp/Cntr(USF)=0,0
Exp/Cntr=0.3,0.1

Type RM Length L Ch R = 1 ,68863   ,426.3,425.9,412.8
XS GIS Cut Line= 3
2141460.18171589413231.1024723232141098.89839961413865.899711663
2140658.01028483414265.964852854
#Sta/Elev= 30
       0  3388.6    49.1 3364.79    71.4  3358.6    82.8 3351.72   135.7 3340.35
   321.6 3329.89   573.5 3300.98   618.8  3299.2     649 3292.59   660.3 3287.06
   699.7 3283.79   720.7 3273.82   740.9 3269.06   820.7 3241.14   842.8 3231.21
   935.8 3204.73   990.1 3206.49  1005.9 3203.53  1033.3 3207.79  1064.3 3204.78
  1094.6 3204.83  1099.3 3207.56  1113.2 3223.21  1126.3 3229.68  1141.1 3231.98
  1223.8  3257.1  1245.6 3272.17  1261.8 3280.15  1290.3 3287.45  1325.8 3301.86
#Mann= 3 , 0 , 0
       0     .12       0  1064.3     .04       0  1094.6     .12       0
Bank Sta=1064.3,1094.6
XS Rating Curve= 0 ,0
Exp/Cntr(USF)=0,0
Exp/Cntr=0.3,0.1

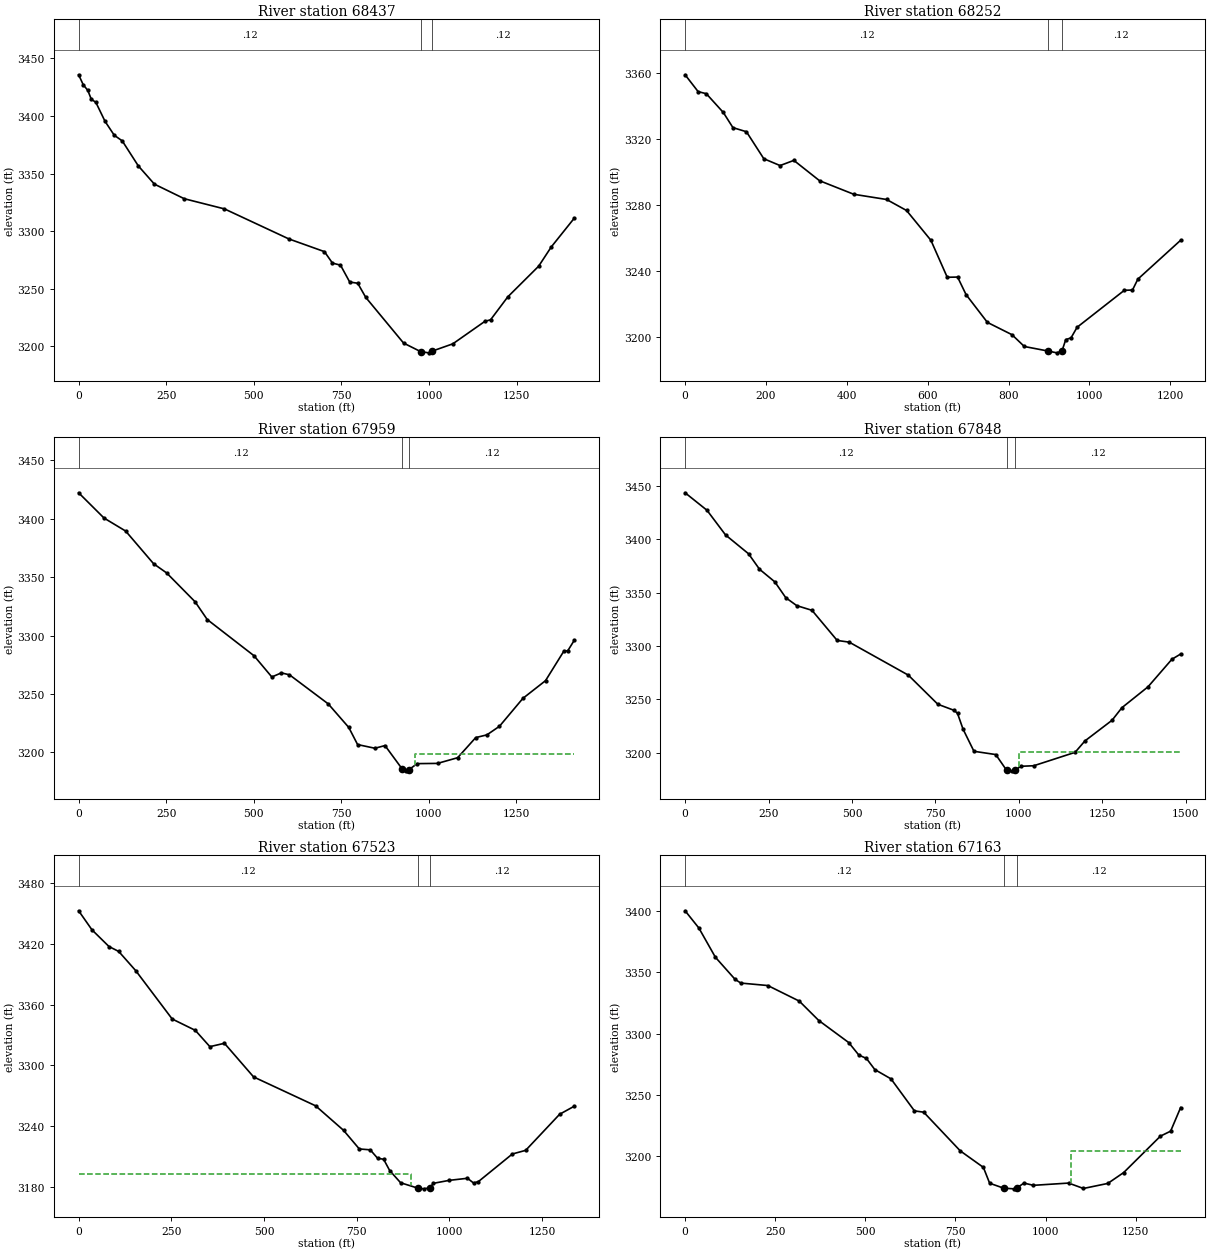
Type RM Length L Ch R = 1 ,68437   ,180.1,184.5,186
XS GIS Cut Line= 3
     2141487.679      413105.381     2140853.146      413649.266
     2140531.759      414129.973
#Sta/Elev= 30
       0 3435.79    13.1 3427.16    26.2 3422.23      36 3414.65    49.2 3411.83
    75.4 3395.36   101.6 3383.33   124.5 3378.41   170.4 3356.67   216.3 3340.87
   301.5 3328.23   416.2 3319.39   599.8 3293.35   701.4 3282.31   724.3 3272.36
   747.2 3270.59   773.5 3255.95   796.4 3254.87   819.3 3242.61   927.2 3202.97
   976.2 3195.51   999.1 3194.49  1008.9 3195.99  1067.7  3202.3  1159.2 3221.81
  1175.5 3223.18  1224.5 3243.04  1312.7  3269.7  1348.6 3286.38    1414 3311.24
#Mann= 3 , 0 , 0
       0     .12       0   976.2     .04       0  1008.9     .12       0
Bank Sta=976.2,1008.9
XS Rating Curve= 0 ,0
Exp/Cntr=0.3,0.1

Type RM Length L Ch R = 1 ,68252   ,283.3,292.8,288
XS GIS Cut Line= 3
2141282.17107105413055.8060195952140799.93963532413465.489363218
2140411.59396585413913.580520306
#Sta/Elev= 30
       0 3359.02    32.2 3348.81    52.5 3347.52    94.5 3336.14   118.3 3326.93
   151.7 3324.44   194.7 3308.05   234.9  3303.9     269 3307.04   332.5 3294.71
   417.3 3286.46   498.4  3283.3   547.7 3276.63     608 3258.52   648.4 3236.07
     674  3236.2   694.9 3225.57   747.7 3208.68   808.5 3201.21   839.1 3194.04
  898.19 3191.26   919.5 3190.19   932.2 3191.29   941.5 3198.21   954.6  3199.3
   969.6 3205.71  1086.4 3228.16  1106.6 3228.33  1119.9 3234.94  1225.7 3258.55
#Mann= 3 , 0 , 0
       0     .12       0  898.19     .04       0   932.2     .12       0
Bank Sta=898.19,932.2
XS Rating Curve= 0 ,0
Exp/Cntr(USF)=0,0
Exp/Cntr=0.5,0.3

Type RM Length L Ch R = 1 ,67959   ,116,111.5,116.1
XS GIS Cut Line= 4
2141211.14114354412776.0753421652140574.05622455413343.911900393
2140401.92458495 413537.807310522140229.79294535413787.101409254
#Sta/Elev= 30
       0 3422.25    72.5 3400.63   134.4 3389.47   214.2 3361.51   251.4 3353.65
   332.8 3328.93   367.3 3313.79     501 3282.78   551.9  3264.6   579.1  3268.1
   602.3 3266.47   713.1 3241.56   771.7 3221.41   796.9 3206.76   846.4  3203.6
   875.2  3205.9   924.63185.736   934.7 3184.27   943.9 3185.34   967.1 3190.44
  1025.2 3190.64  1082.7  3195.5  1134.4 3212.73  1166.3 3215.05  1202.2 3222.41
  1269.2 3246.31  1333.7 3261.43  1385.6 3286.47  1397.5 3287.14  1415.6 3295.86
#Mann= 3 , 0 , 0
       0     .12       0   924.6     .04       0   943.9     .12       0
#XS Ineff= 2 , 0
                          959.64         3198.33
Permanent Ineff=
       F       F
Bank Sta=924.6,943.9
XS Rating Curve= 0 ,0
Exp/Cntr(USF)=0,0
Exp/Cntr=0.5,0.3

Type RM Length L Ch R = 1 ,67848   ,325.9,325.3,325
XS GIS Cut Line= 4
     2141152.557      412685.106     2140476.821      413286.676
     2140377.933       413407.54      2140149.94      413764.636
#Sta/Elev= 30
       0 3443.48    65.6 3427.08   121.3 3403.91   190.1 3386.31   222.9 3371.82
   268.8 3359.98   301.6 3345.13   334.4 3337.71   380.2 3333.29   455.6 3305.07
   491.7 3303.47   668.7 3272.56   757.2 3245.25   806.4 3239.49   816.2 3236.65
   832.6    3222   865.4 3201.16   930.7  3198.1   963.3 3183.34   979.5 3182.84
   989.3 3183.48  1005.6  3187.1  1044.6 3187.62  1168.4 3200.18  1197.8 3210.86
  1279.2 3230.26  1308.6 3242.01  1386.8 3261.58  1458.5 3287.44  1484.6 3292.33
#Mann= 3 , 0 , 0
       0     .12       0   963.3     .04       0   989.3     .12       0
#XS Ineff= 2 , 0
                          1000.9         3200.84
Permanent Ineff=
       F       F
Bank Sta=963.3,989.3
XS Rating Curve= 0 ,0
Exp/Cntr=0.5,0.3

Type RM Length L Ch R = 1 ,67523   ,360.5,359.8,361.5
XS GIS Cut Line= 3
     2140677.344       412451.62     2140056.546      413316.892
     2139913.707      413547.631
#Sta/Elev= 30
       0 3452.48      36 3433.67    81.9  3417.2   108.1 3412.37     154  3393.4
   252.3 3345.72   314.6 3334.53   353.9 3318.44   393.2 3321.76   471.8 3288.59
     639 3260.09   714.3 3235.93   756.9 3217.52   786.4 3216.66   806.1 3208.38
   822.5 3207.34   838.8 3196.22   868.3 3184.17   914.2 3178.94   930.6 3178.18
     947  3179.2   956.8 3183.64   999.4 3186.55  1048.6  3188.6  1064.9 3183.94
    1078 3185.31  1169.6 3212.56  1205.5 3216.15  1297.1 3251.75  1336.3 3259.64
#Mann= 3 ,-1 , 0
       0     .12       0   914.2     .04       0     947     .12       0
#XS Ineff= 2 , 0
          896.19 3192.47
Permanent Ineff=
       F       F
Bank Sta=914.2,947
XS Rating Curve= 0 ,0
Exp/Cntr=0.3,0.1

Type RM Length L Ch R = 1 ,67163   ,457,457.8,446.7
XS GIS Cut Line= 3
2140385.72968453412305.0377920282139674.05188544413218.759712039
2139595.64670419413420.803832966
#Sta/Elev= 30
       0 3400.16    38.2 3386.11      84 3362.32   138.8 3344.23   154.7 3341.24
   229.6 3339.22   316.8 3326.54   370.9 3310.73     454 3292.75     482 3282.56
   503.1 3279.83   526.4 3270.73   571.3 3263.15   636.3 3237.08     662    3236
   763.5 3204.46   827.6 3191.02     845  3178.1   884.1 3174.06     913 3173.53
     9213174.392   940.2 3178.22   966.4 3176.39  1064.1 3178.23  1105.2 3173.83
  1172.8 3177.94  1216.9 3186.81  1318.9  3216.5  1347.1 3220.54  1374.9 3239.79
#Mann= 3 , 0 , 0
       0     .12       0   884.1     .04       0     921     .12       0
#XS Ineff= 2 , 0
                         1071.99         3204.72
Permanent Ineff=
       F       F
Bank Sta=884.1,921
XS Rating Curve= 0 ,0
Exp/Cntr(USF)=0,0
Exp/Cntr=0.3,0.1

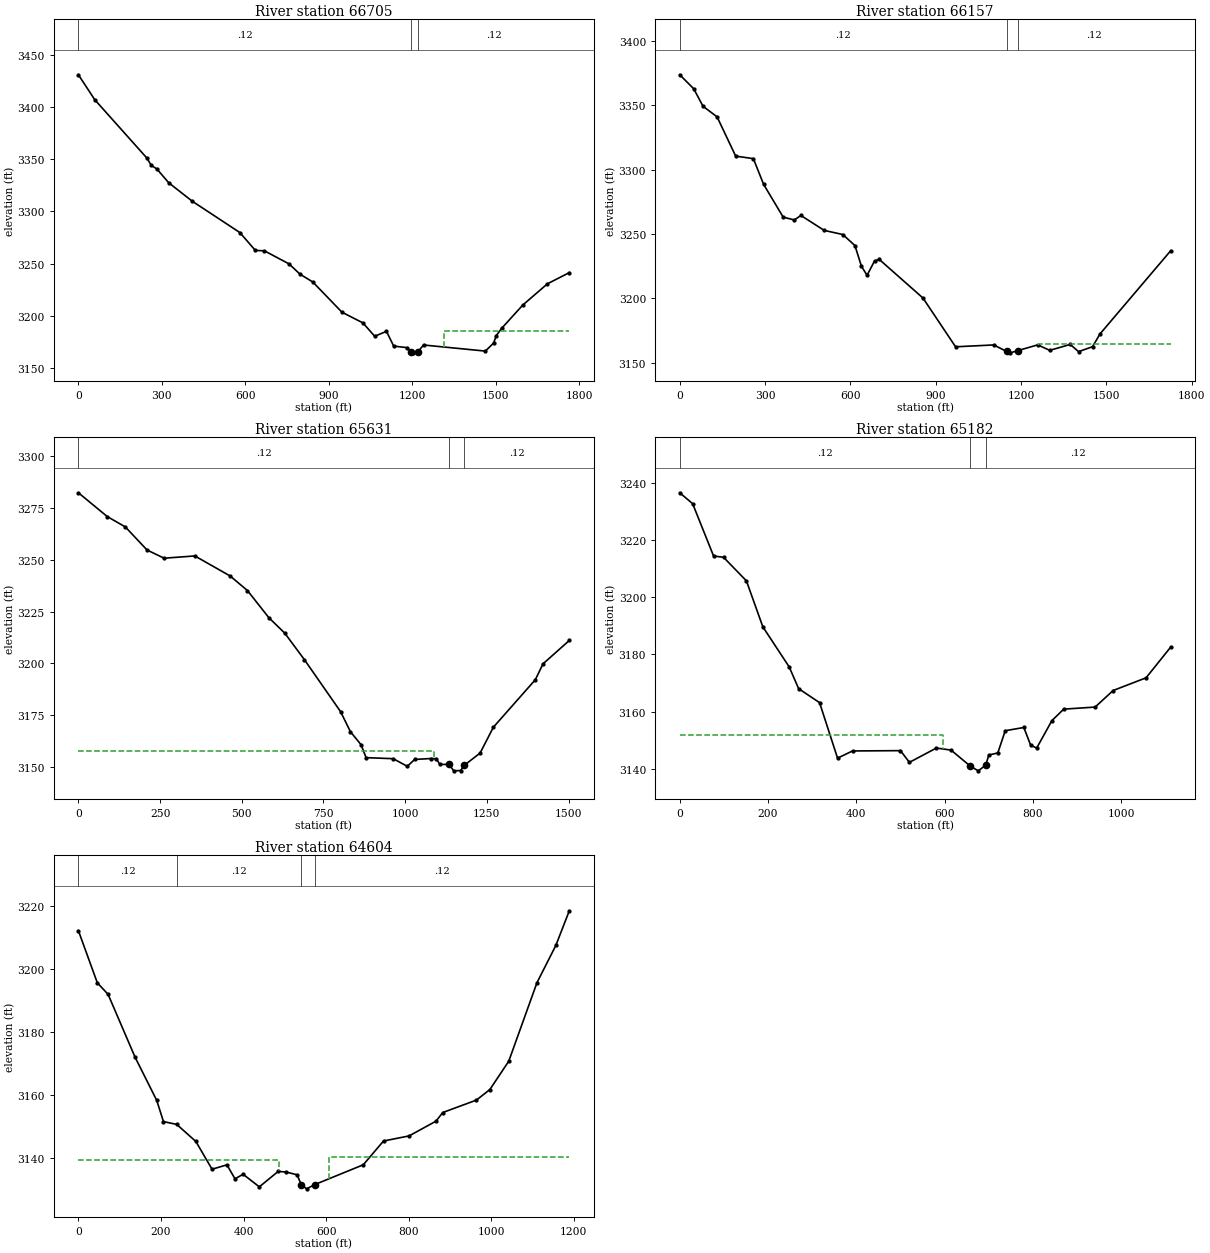
Type RM Length L Ch R = 1 ,66705   ,565.9,547.8,531.3
XS GIS Cut Line= 4
     2140180.156      411915.975     2139515.407      412709.828
      2139389.05      412962.542     2139218.742      413374.577
#Sta/Elev= 30
       0 3430.95      59 3406.99   245.8 3351.23   262.1 3344.08   281.8 3340.77
   324.4 3327.51   409.6  3309.7     580  3279.8   635.7 3262.68   668.4 3262.26
   756.9 3249.73   796.2 3239.88   842.1 3232.44     947 3203.43  1022.3 3193.21
  1064.6 3180.42  1106.9  3185.1  1132.8 3170.99  1181.6 3169.48  1194.6 3165.42
    1201 3164.52  1220.5 3165.76    1240 3172.04  1462.2 3166.19  1491.7 3173.86
  1501.6  3181.1  1521.2 3188.13  1596.6  3210.3  1685.1 3230.65  1763.8 3241.38
#Mann= 3 , 0 , 0
       0     .12       0  1194.6     .04       0  1220.5     .12       0
#XS Ineff= 2 , 0
                         1314.09          3185.2
Permanent Ineff=
       F       F
Bank Sta=1194.6,1220.5
XS Rating Curve= 0 ,0
Exp/Cntr=0.3,0.1

Type RM Length L Ch R = 1 ,66157   ,513.3,526,541
XS GIS Cut Line= 4
     2139276.427      411589.094     2138941.306      412627.421
     2138977.016      412797.729     2138908.343      413253.713
#Sta/Elev= 30
       0 3373.75    49.2 3362.84    81.9 3349.22   131.1 3341.09   196.6 3310.51
   258.8 3308.56   294.9 3288.54   363.7 3263.06     403 3260.87   425.9 3264.39
   507.8 3252.76   573.4 3249.55     616 3240.94   638.9 3224.84   658.6 3217.84
   684.8 3228.94   701.2 3230.26   855.2 3200.18   969.8 3162.26    1104  3163.7
  1149.1 3158.69    1162 3157.56  1187.7 3159.22  1258.6 3163.76    1301 3159.49
    1373 3164.09  1402.4 3158.48  1451.5 3162.35  1477.7 3172.26  1726.2 3236.92
#Mann= 3 ,-1 , 0
       0     .12       0  1149.1     .04       0  1187.7     .12       0
#XS Ineff= 2 , 0
         1091.49 3163.51    1260         3164.36
Permanent Ineff=
       F       F
Bank Sta=1149.1,1187.7
XS Rating Curve= 0 ,0
Exp/Cntr=0.3,0.1

Type RM Length L Ch R = 1 ,65631   ,446.4,449.4,442.9
XS GIS Cut Line= 4
2138909.79265652 411691.305277762138630.43733073412471.856923374
2138486.65150127412829.2674137342138416.81266982413108.622739533
#Sta/Elev= 30
       0 3282.42    88.2 3270.94   143.8 3265.89     210 3254.76   262.2 3250.79
   356.3 3251.88   464.3  3242.2   517.3 3235.15   582.8 3222.04   631.6 3214.54
   691.3  3201.8   802.3 3176.61   832.4 3166.91   865.2 3160.57   880.3 3154.37
   963.5 3153.86  1006.4 3150.18  1029.1  3153.5  1079.5 3153.95  1095.5 3153.83
  1106.1 3151.07  1134.4 3151.12  1148.5 3147.99  1169.7 3148.15  1180.3 3150.61
  1229.2 3156.57  1269.9 3169.09  1398.3 3192.06  1421.9 3199.74  1502.2 3211.02
#Mann= 3 , 0 , 0
       0     .12       0  1134.4     .04       0  1180.3     .12       0
#XS Ineff= 2 , 0
            1087 3157.41
Permanent Ineff=
       F       F
Bank Sta=1134.4,1180.3
XS Rating Curve= 0 ,0
Exp/Cntr(USF)=0,0
Exp/Cntr=0.3,0.1

Type RM Length L Ch R = 1 ,65182   ,573.1,577.9,567.5
XS GIS Cut Line= 3
2138326.43300559411913.1462717762138248.37784103412225.366930022
2138047.07767979412989.485909413
#Sta/Elev= 30
       0 3236.47    29.2 3232.65    76.6 3214.36    99.1 3213.93     151 3205.68
   188.2 3189.61   247.9  3175.6   269.3    3168   316.7 3163.12   357.4 3143.72
   391.3 3146.23   499.9 3146.34   520.2 3142.25   581.3 3147.25   614.5 3146.53
   658.53140.878   676.3 3139.28   693.2  3141.3     700 3144.81   720.4 3145.53
   737.3 3153.31   779.4 3154.43     795 3148.18   808.6 3147.26   842.8 3156.79
   869.6 3160.84   940.9 3161.57   981.6 3167.35  1056.3  3171.8    1112 3182.52
#Mann= 3 , 0 , 0
       0     .12       0   658.5     .04       0   693.2     .12       0
#XS Ineff= 2 , 0
          595.96 3151.88
Permanent Ineff=
       F       F
Bank Sta=658.5,693.2
XS Rating Curve= 0 ,0
Exp/Cntr(USF)=0,0
Exp/Cntr=0.3,0.1

Type RM Length L Ch R = 1 ,64604   ,151.1,150.1,147.8
XS GIS Cut Line= 3
     2137754.647      411891.253     2137647.518       412619.18
     2137647.518      413072.418
#Sta/Elev= 30
       0 3212.05    45.8 3195.54    71.9 3191.89   137.3 3171.97   189.7 3158.31
     206 3151.59  238.18 3150.69   284.5 3145.29   323.7  3136.5   359.7 3137.89
   379.3 3133.47     399  3134.9   438.2 3130.92     484 3135.82   503.6  3135.6
   529.8 3134.73   539.6 3131.65   552.6 3130.29   572.3 3131.63     690 3137.91
     739 3145.44     801 3147.05   866.2 3151.73   882.5 3154.46     964 3158.39
   996.6 3161.74  1042.3  3170.7  1110.8 3195.62  1156.4 3207.37    1189 3218.35
#Mann= 4 ,-1 , 0
       0     .12       0  238.18     .12       0   539.6     .04       0
   572.3     .12       0
#XS Ineff= 2 , 0
          485.11 3139.46  607.13         3140.41
Permanent Ineff=
       F       F
Bank Sta=539.6,572.3
XS Rating Curve= 0 ,0
Exp/Cntr=0.3,0.1