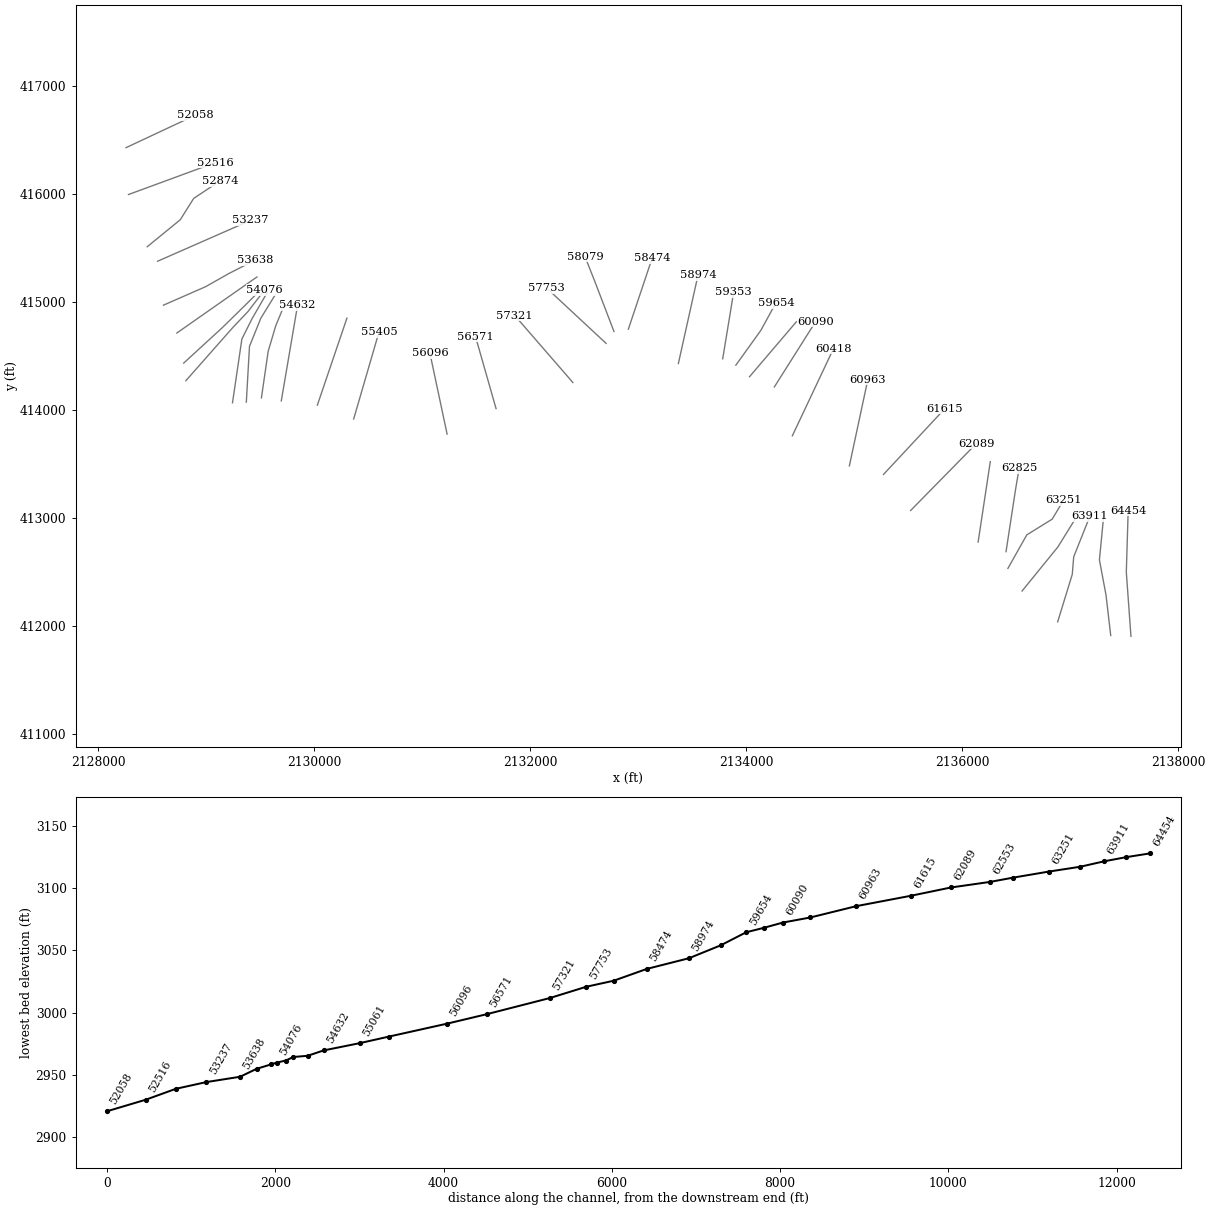
HEC-RAS study SFKCHERRYRV.prj: SFKCHERRYRV

--- SFKCHERRYRV.g01 (geometry) --- (continued)

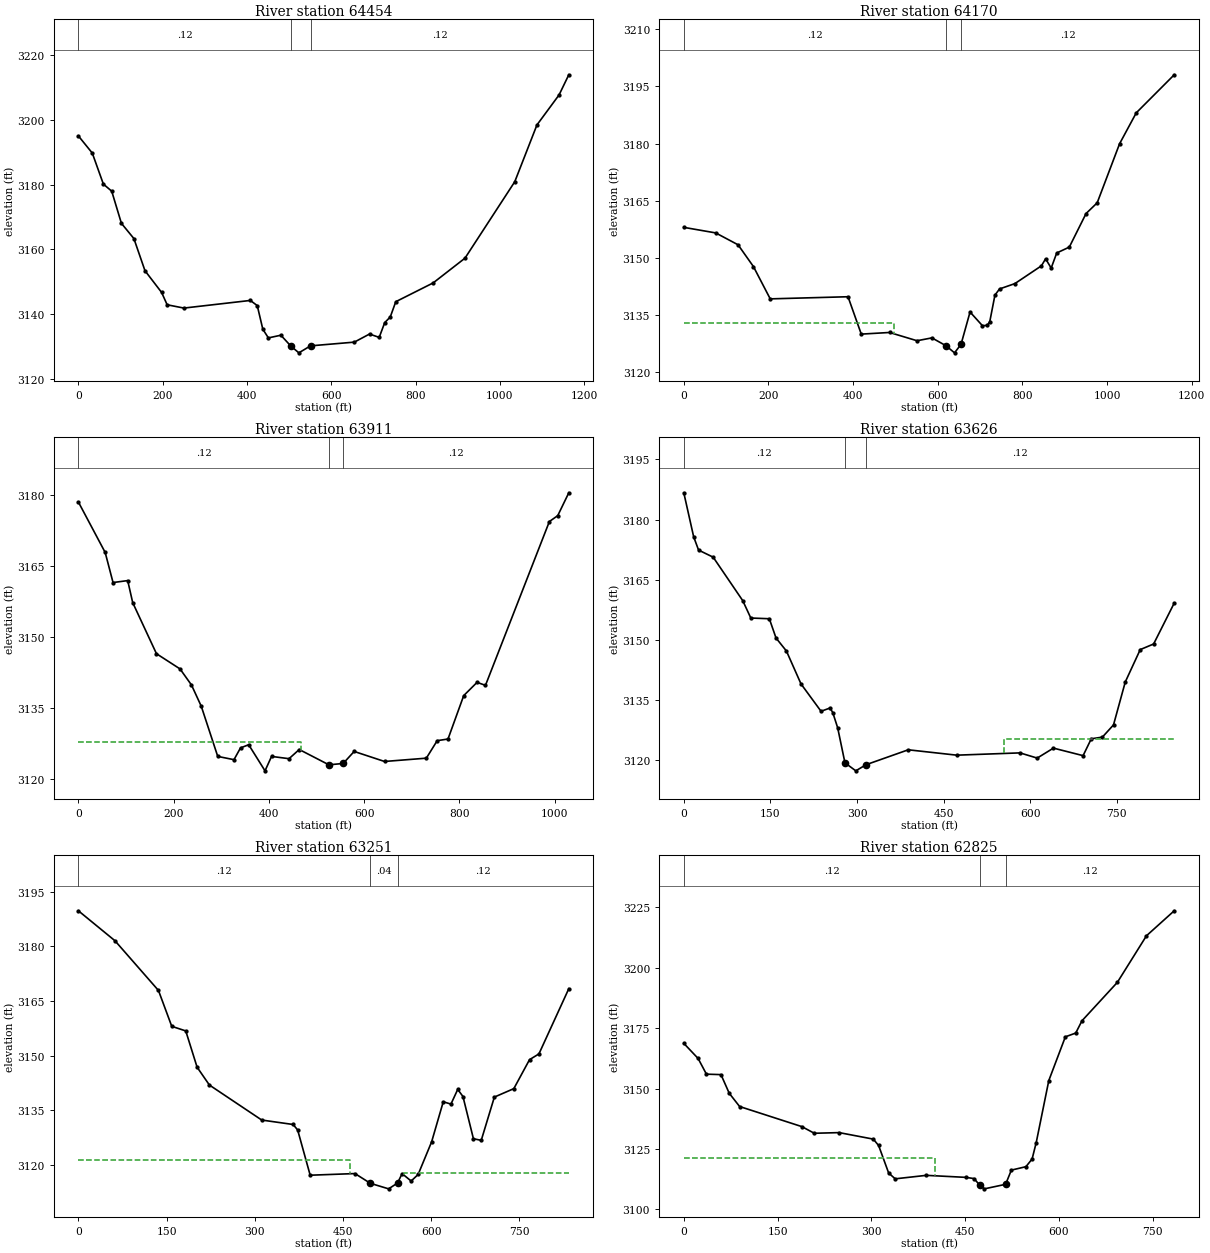
Type RM Length L Ch R = 1 ,64454   ,281.1,284.1,282.1
XS GIS Cut Line= 3
2137562.84311961 411905.280704372137519.87024642412499.738783513
 2137537.0593957413066.980709636
#Sta/Elev= 30
       0 3195.11      33  3189.8    59.3 3180.21    79.1 3178.02   102.1 3168.08
   131.7 3163.37     158 3153.43   197.5 3146.71   210.6  3142.9   250.4 3141.88
     408 3144.24   424.4 3142.64   437.6 3135.33   450.8 3132.66   480.4 3133.49
  503.86 3130.16   523.1 3128.04   550.73130.201   654.6 3131.35   690.7 3133.85
   713.7 3132.82   726.8 3137.39   739.9 3139.12     753 3143.85   841.7 3149.66
   917.2 3157.31  1035.3 3180.95  1087.9  3198.5  1140.4 3207.78  1163.5 3214.01
#Mann= 3 , 0 , 0
       0     .12       0  503.86     .04       0   550.7     .12       0
Bank Sta=503.86,550.7
XS Rating Curve= 0 ,0
Exp/Cntr(USF)=0,0
Exp/Cntr=0.3,0.1

Type RM Length L Ch R = 1 ,64170   ,261.8,258.4,250.6
XS GIS Cut Line= 4
2137375.53462009 411912.556160482137331.86965724 412288.07484101
2137270.73870925 412613.37881426 2137314.4036721413060.944683496
#Sta/Elev= 30
       0 3157.97    75.4 3156.51   128.2 3153.39   164.5 3147.67   204.2 3139.18
     388 3139.74   419.3 3129.92   486.1 3130.35     551 3128.18   586.2 3128.93
   619.6 3126.86   639.6    3125     655 3127.23   676.3 3135.73   705.5 3132.14
     717 3132.21   722.9 3133.19   735.1 3140.17     746 3141.79   782.2 3143.19
   844.9 3147.86   854.8  3149.7     868 3147.28   881.1 3151.24   910.8 3152.78
   950.4  3161.6   976.7 3164.42  1029.6 3179.94    1069 3188.06  1158.7 3198.06
#Mann= 3 , 0 , 0
       0     .12       0   619.6     .04       0     655     .12       0
#XS Ineff= 2 , 0
          497.76 3132.72
Permanent Ineff=
       F       F
Bank Sta=619.6,655
XS Rating Curve= 0 ,0
Exp/Cntr(USF)=0,0
Exp/Cntr=0.3,0.1

Type RM Length L Ch R = 1 ,63911   ,295.9,285.5,270.2
XS GIS Cut Line= 4
  2136884.303788412039.1845527522137019.66517285 412480.20067756
 2137032.7646617412641.7610401142137183.40878354413019.462968786
#Sta/Elev= 30
       0 3178.55    56.3 3167.88    72.8 3161.52   103.6 3161.93   114.1 3157.27
     164 3146.47   213.5 3143.25   237.5 3139.86   258.1 3135.36   292.7 3124.75
   326.8 3124.06   340.5 3126.55   357.7 3127.22     392  3121.7   405.7 3124.75
   442.4 3124.27   463.9 3126.21   526.23122.973   556.1 3123.26   579.2  3125.8
     643 3123.68   730.8 3124.38   753.6 3128.08   776.3 3128.43   809.3 3137.61
   837.3 3140.41     855 3139.78   989.2 3174.42  1006.8 3175.67    1030  3180.5
#Mann= 3 , 0 , 0
       0     .12       0   526.2     .04       0   556.1     .12       0
#XS Ineff= 2 , 0
          468.57 3127.73
Permanent Ineff=
       F       F
Bank Sta=526.2,556.1
XS Rating Curve= 0 ,0
Exp/Cntr(USF)=0,0
Exp/Cntr=0.3,0.1

Type RM Length L Ch R = 1 ,63626   ,378.8,374.3,362.9
XS GIS Cut Line= 3
2136554.63331847412325.1900594342136886.48703615412733.457462103
2137056.78039127413008.546728073
#Sta/Elev= 30
       0 3186.69    17.1  3175.7    25.6 3172.39    50.9 3170.62   102.1 3159.78
   116.1 3155.44   148.2 3155.26   159.8 3150.45   177.8 3147.21   203.1 3138.99
   237.8 3132.17   253.4 3132.99   258.1 3131.85   266.6 3128.05   279.2 3119.32
     298 3117.31   315.8 3118.84   388.9 3122.56   472.9 3121.22   582.5 3121.79
   612.3 3120.49   640.4 3122.98   691.8  3121.1     706 3125.31   725.2 3125.72
   744.5 3128.77   764.9 3139.49   790.8 3147.56     814 3148.96   849.7 3159.17
#Mann= 3 , 0 , 0
       0     .12       0   279.2     .04       0   315.8     .12       0
#XS Ineff= 2 , 0
                          554.98         3125.14
Permanent Ineff=
       F       F
Bank Sta=279.2,315.8
XS Rating Curve= 0 ,0
Exp/Cntr(USF)=0,0
Exp/Cntr=0.3,0.1

Type RM Length L Ch R = 1 ,63251   ,404.6,426.9,445.1
XS GIS Cut Line= 4
2136423.63842991412534.7818811252136598.29828132412844.803117377
2136834.08908072412991.0807429322136936.70174343413163.557346199
#Sta/Elev= 30
       0 3189.72    62.2  3181.5   136.2 3167.85   158.8 3158.01   182.6 3156.75
   201.9 3146.79   222.8  3141.9   311.8 3132.29   365.2 3131.07   372.9 3129.57
   394.2 3117.15   470.4  3117.6   496.6 3114.92   527.6 3113.41   542.8 3115.01
   550.5 3117.59   565.9 3115.55   577.8 3117.36   600.7  3126.3   620.5  3137.3
   633.6 3136.67   645.1  3140.7     654 3138.75   671.8 3127.16   685.1 3126.72
   707.4 3138.59   740.5 3140.91   767.2 3148.86   783.2 3150.44     834 3168.34
#Mann= 3 , 0 , 0
       0     .12       0   496.6     .04       0   542.8     .12       0
#XS Ineff= 2 , 0
          461.88 3121.34  553.25         3117.79
Permanent Ineff=
       F       F
Bank Sta=496.6,542.8
XS Rating Curve= 0 ,0
Exp/Cntr(USF)=0,0
Exp/Cntr=0.3,0.1

Type RM Length L Ch R = 1 ,62825   ,271.7,271.8,271.5
XS GIS Cut Line= 3
2136406.17244477412689.7924992512136495.68561862413274.903001472
2136528.43434076413464.845589879
#Sta/Elev= 30
       0 3168.67    22.9 3162.42    36.2 3155.93    59.5 3155.74    72.7 3148.03
    89.3 3142.55   188.9 3134.24   208.8 3131.49   248.6 3131.76   303.2 3129.07
   311.7 3126.44   327.8 3115.04   338.3 3112.65     388 3114.09   451.6 3113.25
   464.4 3112.75   473.9 3109.92     481 3108.51   514.9 3110.38   524.1 3116.25
   547.4 3117.67   557.3 3120.84   563.9 3127.65     584 3153.28   610.5 3171.37
   627.1 3172.93   637.1    3178   693.7 3193.89   740.3 3213.16   784.7 3223.49
#Mann= 3 , 0 , 0
       0     .12       0   473.9     .04       0   514.9     .12       0
#XS Ineff= 2 , 0
          402.69 3121.38
Permanent Ineff=
       F       F
Bank Sta=473.9,514.9
XS Rating Curve= 0 ,0
Exp/Cntr(USF)=0,0
Exp/Cntr=0.3,0.1

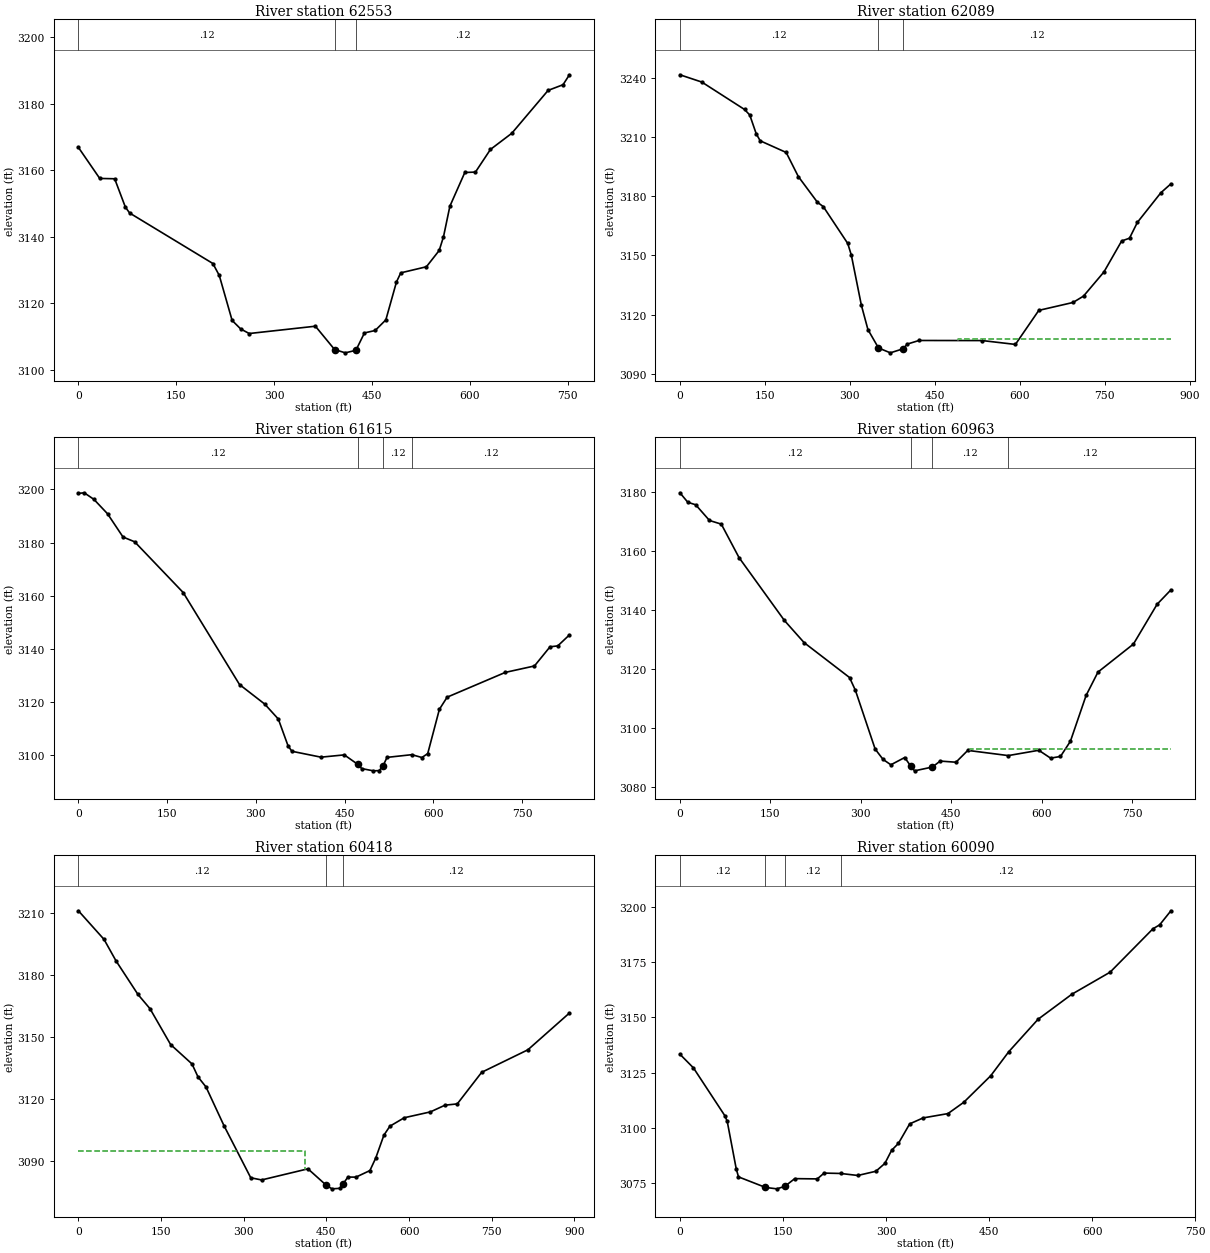
Type RM Length L Ch R = 1 ,62553   ,485.9,463.9,450.2
XS GIS Cut Line= 2
     2136147.712        412778.5     2136260.335      413522.909
#Sta/Elev= 30
       0 3166.89    32.7 3157.56    55.6 3157.46      72 3148.94    78.6 3147.15
   206.2 3131.97     216 3128.38   235.7 3114.85   248.8 3112.29   261.9 3110.91
   363.4 3113.11   392.8  3106.1   409.2  3105.1   425.5 3105.86   438.6 3111.09
     455 3111.82   471.4 3115.01   487.7 3126.42   494.3 3129.16   533.6 3130.99
   553.2 3135.89   559.8 3140.01   569.6 3149.21   592.5 3159.35   608.8 3159.47
   631.8 3166.28   664.5 3171.14   720.2 3184.04   743.1 3185.75   752.9 3188.74
#Mann= 3 , 0 , 0
       0     .12       0   392.8     .04       0   425.5     .12       0
Bank Sta=392.8,425.5
XS Rating Curve= 0 ,0
Exp/Cntr=0.3,0.1

Type RM Length L Ch R = 1 ,62089   ,471.6,474.2,474.1
XS GIS Cut Line= 2
2135522.67678309413070.7037876182136129.83256652413689.208277286
#Sta/Elev= 30
       0 3241.41    38.7 3237.72   114.1 3223.84   123.3 3221.05   134.7 3211.55
   141.7 3207.99   187.6 3202.08     209  3189.9   242.8 3176.84   253.1 3174.67
   296.3 3155.99   302.6 3150.09   320.3 3124.74   331.9  3112.4   350.5 3103.11
   371.4 3100.63   393.83102.663   401.5 3105.08   422.1 3106.89   533.8 3106.84
   592.2 3104.89   633.5 3122.13   693.9 3126.13   712.4 3129.35   748.5 3141.59
   779.7 3157.25   793.6 3158.68   807.5 3166.68   848.9 3181.67   866.7  3186.2
#Mann= 3 , 0 , 0
       0     .12       0   350.5     .04       0   393.8     .12       0
#XS Ineff= 2 , 0
                           491.3         3107.67
Permanent Ineff=
       F       F
Bank Sta=350.5,393.8
XS Rating Curve= 0 ,0
Exp/Cntr(USF)=0,0
Exp/Cntr=0.3,0.1

Type RM Length L Ch R = 1 ,61615   ,628.5,651.8,663.2
XS GIS Cut Line= 2
     2135271.453      413404.793     2135837.313      414011.857
#Sta/Elev= 30
       0  3198.5     9.8 3198.74    26.2 3196.26    49.2 3190.84    75.4 3182.08
    95.1 3180.27   177.1 3161.16   272.3  3126.5   314.9 3119.14   337.9  3113.5
   354.3 3103.43   360.8 3101.36     410 3099.14   449.4    3100   472.4  3096.4
   478.9 3094.83   498.6 3093.99   508.4 3094.08     515 3095.93   521.6 3099.06
  563.55 3100.08   580.6 3099.01   590.4 3100.49   610.1 3117.16   623.2 3121.74
   721.6 3131.08   770.8  3133.5   797.1 3140.72   810.2 3141.06   829.9  3145.2
#Mann= 4 ,-1 , 0
       0     .12       0   472.4     .04       0     515     .12       0
  563.55     .12       0
Bank Sta=472.4,515
XS Rating Curve= 0 ,0
Exp/Cntr=0.3,0.1

Type RM Length L Ch R = 1 ,60963   ,549.3,544.6,535.1
XS GIS Cut Line= 2
     2134955.559      413484.453     2135125.867      414281.053
#Sta/Elev= 30
       0 3179.85    13.1 3176.64    26.2 3175.78    49.1 3170.46    68.7 3169.22
    98.1 3157.88   173.4 3136.56   206.1 3129.05   281.4 3117.23   291.2 3112.87
   323.9 3092.99     337 3089.48     350 3087.65     373 3090.12   382.8 3087.23
   389.3  3085.6   418.8 3086.89   431.8 3088.91     458 3088.52   477.6 3092.53
  544.78 3090.77   595.4 3092.57     615  3089.9   631.4 3090.48   647.8  3095.6
   673.9 3111.16   693.6 3119.08   752.4 3128.57   791.7 3142.07   814.6 3146.94
#Mann= 4 ,-1 , 0
       0     .12       0   382.8     .04       0   418.8     .12       0
  544.78     .12       0
#XS Ineff= 2 , 0
                          481.91         3092.84
Permanent Ineff=
       F       F
Bank Sta=382.8,418.8
XS Rating Curve= 0 ,0
Exp/Cntr=0.3,0.1

Type RM Length L Ch R = 1 ,60418   ,331.4,328.5,325.7
XS GIS Cut Line= 2
2134427.52663166413762.9748677962134807.70829045414568.733010299
#Sta/Elev= 30
       0 3211.29    46.5 3197.42    68.2 3187.03   108.1 3170.72   129.9 3163.83
   167.3 3146.45   206.1 3137.05     217 3130.77   231.5  3125.9   264.1 3107.15
   312.7 3081.87   332.4 3080.82   416.5 3086.21   449.43078.321     460 3076.51
   474.5 3076.75   480.3 3078.98     489 3082.21   503.6 3082.19   528.9 3085.37
   539.5 3091.45   554.3 3102.54   565.2 3106.88   591.2 3110.97   638.7 3113.81
   665.2 3117.07   687.4 3117.68   731.7    3133   815.5  3143.9   890.9 3161.73
#Mann= 3 , 0 , 0
       0     .12       0   449.4     .04       0   480.3     .12       0
#XS Ineff= 2 , 0
          410.87 3094.69
Permanent Ineff=
       F       F
Bank Sta=449.4,480.3
XS Rating Curve= 0 ,0
Exp/Cntr(USF)=0,0
Exp/Cntr=0.3,0.1

Type RM Length L Ch R = 1 ,60090   ,231,228.4,224.8
XS GIS Cut Line= 2
     2134260.595      414215.127     2134642.413      414819.444
#Sta/Elev= 30
       0 3133.34    19.7 3127.15    65.6 3105.41    68.9 3102.94      82 3081.45
    85.3  3077.8   124.6 3073.03     141 3072.39   152.6 3073.48   167.2 3077.01
     200 3076.89   209.9 3079.52  234.11 3079.35     259 3078.44   285.3 3080.35
   298.4 3083.91   308.2 3089.83   318.1 3092.96   334.5  3101.8   354.1  3104.5
   390.2 3106.45   413.2 3111.56   452.5 3123.59   478.7 3134.45   521.4 3149.16
   570.6 3160.49   626.3 3170.48   688.6 3190.11   698.4  3191.9   714.8 3198.27
#Mann= 4 ,-1 , 0
       0     .12       0   124.6     .04       0   152.6     .12       0
  234.11     .12       0
Bank Sta=124.6,152.6
XS Rating Curve= 0 ,0
Exp/Cntr=0.3,0.1

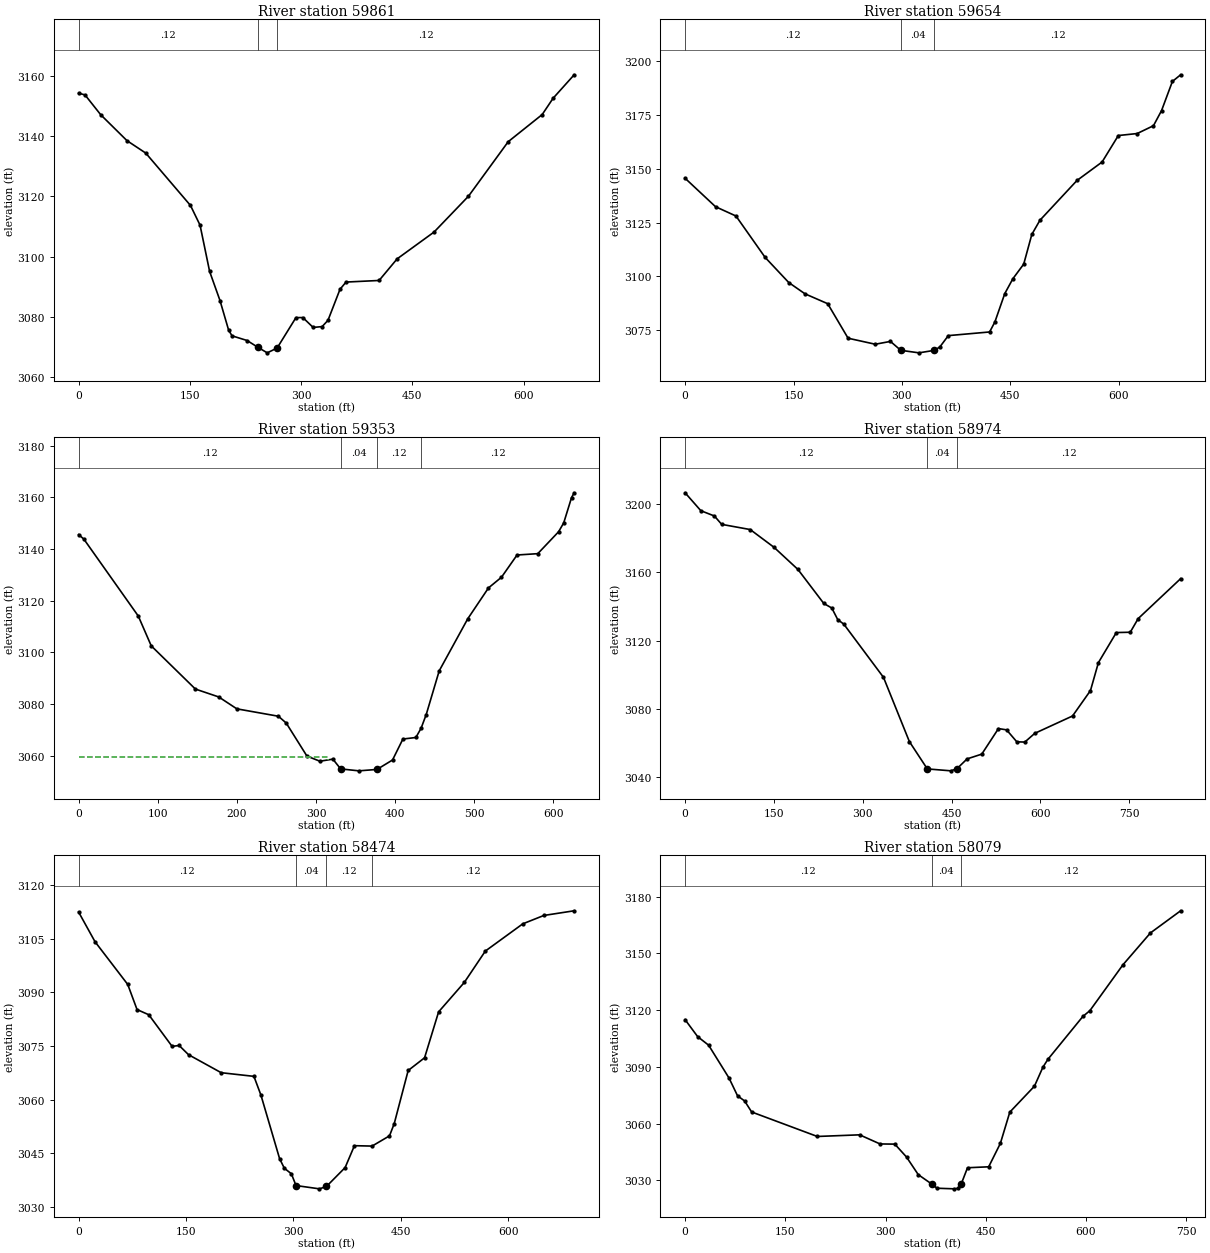
Type RM Length L Ch R = 1 ,59861   ,199.3,206.9,213.1
XS GIS Cut Line= 2
2134031.09719552414310.2821945692134464.39408142414818.763015004
#Sta/Elev= 30
       0 3154.17     8.6 3153.61    29.8 3147.03    65.2 3138.44    90.5 3134.32
   150.8 3116.96   163.7 3110.43   176.6 3095.09   190.6 3085.44   202.2 3075.66
   206.8 3073.75   227.1  3072.2   241.8 3069.93   254.3 3068.11   267.6  3069.7
     293 3079.79   302.3  3079.8   316.2 3076.53   328.3 3076.81   336.2  3078.9
   352.4 3089.18   360.5 3091.57   405.1  3092.1   429.4 3099.26   479.2 3108.15
   525.6 3120.03   579.2 3138.11     625  3147.1   639.7  3152.5   668.1 3160.28
#Mann= 3 , 0 , 0
       0     .12       0   241.8     .04       0   267.6     .12       0
Bank Sta=241.8,267.6
XS Rating Curve= 0 ,0
Exp/Cntr(USF)=0,0
Exp/Cntr=0.3,0.1

Type RM Length L Ch R = 1 ,59654   ,292.2,301.5,321.4
XS GIS Cut Line= 3
2133904.47162156414417.1225225982134135.95899895414739.622031278
2134274.45572047414992.873179199
#Sta/Elev= 30
       0 3145.56    42.1 3132.37    70.4 3128.05   110.7 3108.87   143.4  3097.2
   165.9 3091.96   197.3 3087.38   225.5 3071.37   263.1 3068.58   284.1 3069.89
   298.4 3065.76   323.5 3064.59     345 3065.75   352.5 3067.34   364.2 3072.58
   421.3 3074.27   428.6 3078.91   442.3 3092.08   453.5 3098.96   468.5 3105.75
   479.7 3119.51   490.9 3126.07   542.2 3144.54   576.9 3153.09   599.4 3165.38
   625.5 3166.31     648 3169.94   659.2 3176.95   674.2 3190.47   685.6 3193.56
#Mann= 3 , 0 , 0
       0     .12       0   298.4     .04       0     345     .12       0
Bank Sta=298.4,345
XS Rating Curve= 0 ,0
Exp/Cntr(USF)=0,0
Exp/Cntr=0.3,0.1

Type RM Length L Ch R = 1 ,59353   ,381.6,379.3,377.5
XS GIS Cut Line= 2
     2133782.635      414476.082      2133884.27      415094.134
#Sta/Elev= 30
       0  3145.6     6.6 3143.84    75.4 3114.06    91.8 3102.51   147.6 3085.79
   177.1 3082.74     200 3078.13   252.5 3075.27   262.4 3072.64   288.6 3059.84
     305 3057.85   321.4 3058.66   331.2 3054.88   354.2 3054.13   377.1 3054.67
   396.8 3058.33   409.9 3066.44   426.3 3067.04  432.92 3070.64   439.4 3075.94
   455.8 3092.85   491.9 3113.01   518.1 3124.96   534.5 3129.08   554.2 3137.69
   580.4 3138.21   606.7 3146.69   613.2 3150.14   623.1 3159.93   626.4 3161.78
#Mann= 4 ,-1 , 0
       0     .12       0   331.2     .04       0   377.1     .12       0
  432.92     .12       0
#XS Ineff= 2 , 0
          315.74 3059.39
Permanent Ineff=
       F       F
Bank Sta=331.2,377.1
XS Rating Curve= 0 ,0
Exp/Cntr=0.3,0.1

Type RM Length L Ch R = 1 ,58974   ,506.9,500.2,499.7
XS GIS Cut Line= 2
2133372.09695205 414432.548535512133553.67625176415249.655384244
#Sta/Elev= 30
       0 3206.72    26.6 3196.21    49.5  3193.1    61.8  3188.2     110 3185.16
   150.3 3174.72   190.6 3161.77   234.3 3141.81   247.8 3139.15   257.8 3132.37
   268.1 3129.69   335.1  3098.5   378.8 3060.86   409.1 3044.82   449.2 3043.69
   459.5 3045.05   476.3 3050.69   501.1 3053.49   529.3 3068.47     543 3067.72
   560.3  3060.7   573.8 3060.56   590.6 3065.67   654.4 3075.85   684.7 3090.75
   698.1 3107.14   728.4 3124.77   751.9 3124.95   765.3 3132.96     837 3156.37
#Mann= 3 , 0 , 0
       0     .12       0   409.1     .04       0   459.5     .12       0
Bank Sta=409.1,459.5
XS Rating Curve= 0 ,0
Exp/Cntr(USF)=0,0
Exp/Cntr=0.3,0.1

Type RM Length L Ch R = 1 ,58474   ,374.9,394.9,415.3
XS GIS Cut Line= 2
     2132909.122      414750.772     2133128.873       415407.28
#Sta/Elev= 30
       0 3112.47    22.9 3104.19    68.6 3092.25    81.6 3085.23      98 3083.78
   130.6 3074.94   140.4 3075.19   153.5 3072.62   199.2 3067.58   244.9 3066.56
   254.7 3061.31   280.8 3043.53   287.4 3040.88   297.2 3039.33   303.7 3036.04
   336.4 3035.12   346.2 3035.78   372.3 3041.06   385.3 3047.18  409.98 3047.07
   434.3 3049.93   440.9 3053.34   460.4  3068.2   483.3 3071.75   502.9 3084.58
   538.8 3092.81   568.2 3101.58   620.5 3109.19   649.9 3111.53   692.3 3112.84
#Mann= 4 ,-1 , 0
       0     .12       0   303.7     .04       0   346.2     .12       0
  409.98     .12       0
Bank Sta=303.7,346.2
XS Rating Curve= 0 ,0
Exp/Cntr=0.3,0.1

Type RM Length L Ch R = 1 ,58079   ,318,325.2,345.6
XS GIS Cut Line= 3
2132775.82591708414729.0226373782132598.92636485415191.683004739
2132508.20864576415420.745245442
#Sta/Elev= 30
       0 3114.95    18.8 3105.98    35.2 3101.47    65.7 3084.15    78.5 3074.73
    89.1    3072    99.6 3066.19   197.9 3053.25   261.2 3054.12   291.8  3049.3
   313.9 3049.21   331.4 3042.39     349 3033.08   368.9 3028.19   377.1 3025.91
     403 3025.59   408.7 3025.81   413.13027.976   422.7 3036.73   454.4 3037.23
   471.9 3049.61     486  3066.1   522.9 3079.82   535.5 3089.81   543.1 3094.03
   595.3 3116.62   605.9 3119.72   655.3 3143.91   696.5 3160.76   741.7 3172.46
#Mann= 3 , 0 , 0
       0     .12       0   368.9     .04       0   413.1     .12       0
Bank Sta=368.9,413.1
XS Rating Curve= 0 ,0
Exp/Cntr(USF)=0,0
Exp/Cntr=0.3,0.1

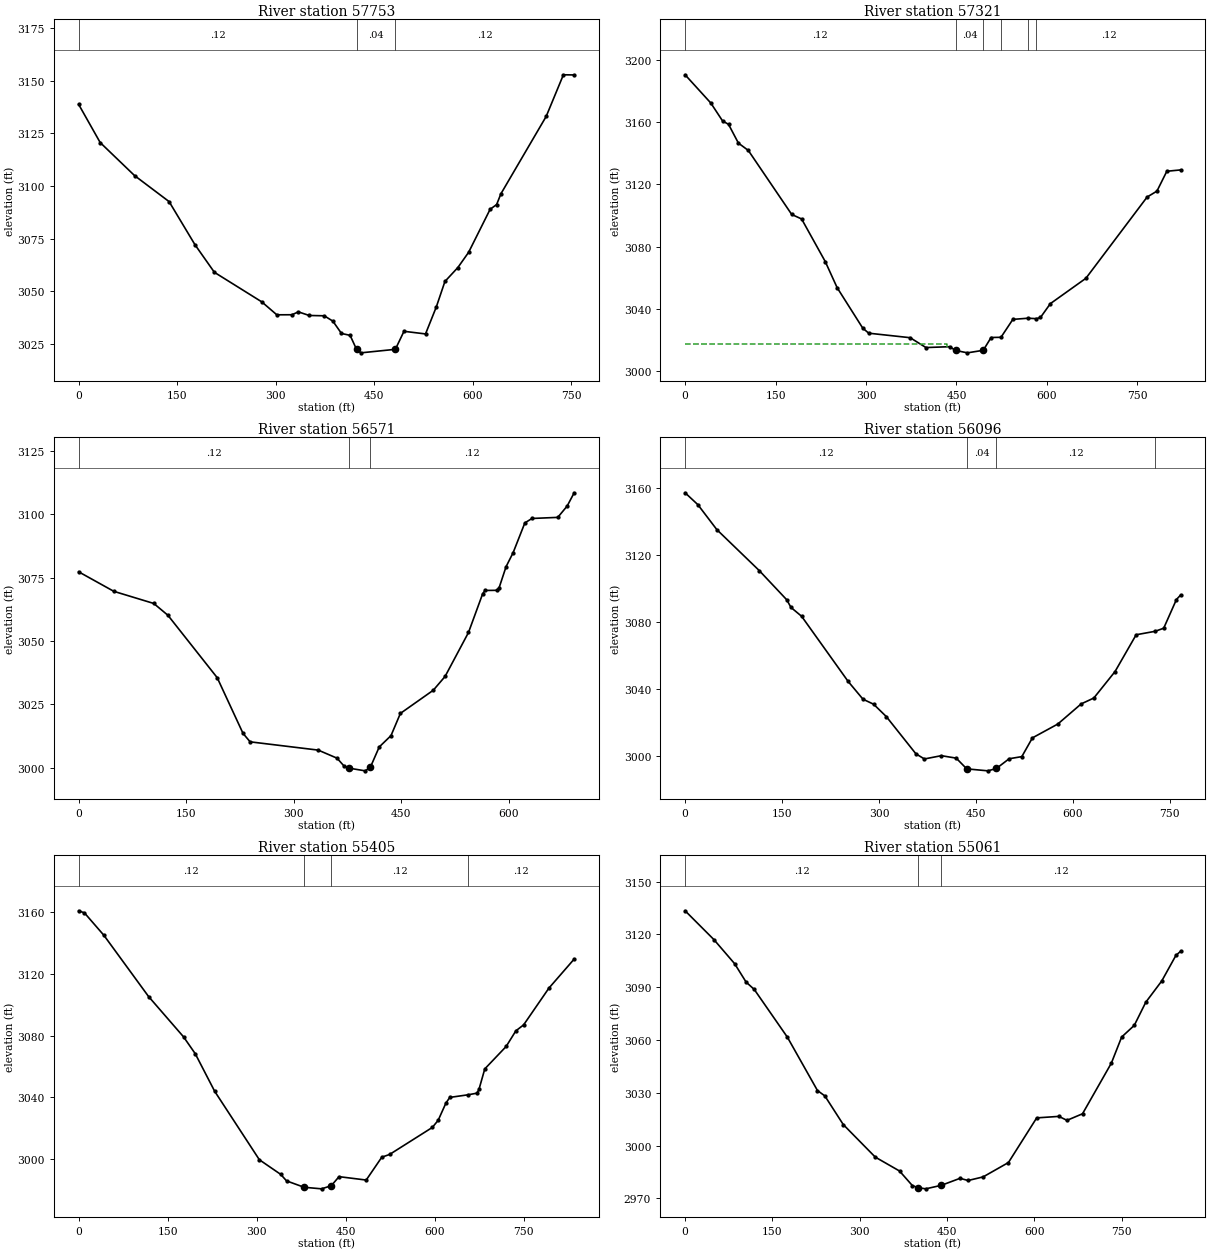
Type RM Length L Ch R = 1 ,57753   ,438.2,432.6,431.4
XS GIS Cut Line= 2
     2132703.104      414618.921     2132150.978       415132.59
#Sta/Elev= 30
       0 3138.76    32.8 3120.62    85.2 3104.91   137.7 3092.57     177 3072.12
   206.6 3058.99   278.7 3044.96   301.6 3038.81   324.6 3038.84   334.4 3040.21
   350.8  3038.5   373.8 3038.34   386.9  3035.8     400 3029.95   413.1 3029.06
     423 3022.35   429.5 3020.75     482 3022.42   495.1 3030.98   527.9 3029.73
   544.3 3042.54   557.4 3054.64   577.1 3061.26   593.5 3068.51   626.2 3088.93
   636.1 3091.18   642.6 3096.28   711.5 3133.03   737.7 3152.81   754.1 3152.73
#Mann= 3 , 0 , 0
       0     .12       0     423     .04       0     482     .12       0
Bank Sta=423,482
XS Rating Curve= 0 ,0
Exp/Cntr=0.3,0.1

Type RM Length L Ch R = 1 ,57321   ,756.8,749.9,732.2
XS GIS Cut Line= 2
     2132395.452       414256.33      2131857.06      414877.129
#Sta/Elev= 30
       0 3190.43    42.6 3172.29    62.2 3160.72      72 3158.59    88.4  3146.5
   104.8  3141.8   176.8 3100.64   193.2 3097.74   232.4 3070.36   252.1 3053.58
   294.6 3027.55   304.5 3024.31   373.2 3021.41   399.4 3015.08   438.7 3015.63
   448.5 3013.21   468.2 3011.68   494.4 3013.31   507.4 3021.54  523.78 3021.67
   543.5 3033.19  568.86 3033.94  582.65 3033.64   589.3 3034.42   605.7 3043.31
   664.6  3059.6   766.1 3111.83   782.4 3115.64   798.8 3128.41   821.7 3129.27
#Mann= 6 ,-1 , 0
       0     .12       0   448.5     .04       0   494.4     .12       0
  523.78     .12       0  568.86     .06       0  582.65     .12       0
#XS Ineff= 2 , 0
          434.04 3017.23
Permanent Ineff=
       F       F
Bank Sta=448.5,494.4
XS Rating Curve= 0 ,0
Exp/Cntr=0.3,0.1

Type RM Length L Ch R = 1 ,56571   ,477.2,474.4,472
XS GIS Cut Line= 2
     2131684.006      414014.604      2131494.47      414679.352
#Sta/Elev= 30
       0 3077.33    49.1 3069.61   104.8 3064.82   124.5 3060.16   193.3 3035.49
   229.3 3013.49   239.2 3010.15   334.2 3006.88   360.4  3003.7   370.2 3000.59
   376.7 2999.77   399.7 2998.69  406.86 3000.06   419.3 3008.13   435.7  3012.6
   448.8 3021.38   494.7 3030.54   511.1 3035.97   543.8 3053.36   563.5  3068.6
   566.8 3069.96   583.1 3070.01   586.4 3070.94   596.2 3079.34   606.1 3084.92
   622.4 3096.64   632.3  3098.4   668.3 3098.83   681.4  3103.3   691.2 3108.55
#Mann= 3 , 0 , 0
       0     .12       0   376.7     .04       0  406.86     .12       0
Bank Sta=376.7,406.86
XS Rating Curve= 0 ,0
Exp/Cntr=0.3,0.1

Type RM Length L Ch R = 1 ,56096   ,705.6,691,676
XS GIS Cut Line= 2
     2131230.768      413778.371     2131071.448      414528.273
#Sta/Elev= 30
       0 3157.07    19.7 3149.99    49.1 3135.07   114.7 3110.62   157.3 3093.15
   163.8  3088.6   180.2 3083.34   252.3 3044.38   275.2  3033.8   291.6 3030.82
   311.2 3023.46   357.1 3001.18   370.2 2998.12   396.4 3000.08   419.4 2998.62
   435.7 2992.21   468.5 2991.03   481.6 2992.45   501.3 2998.25   520.9 2999.52
   537.3 3010.71   576.6 3018.98   612.7 3030.99   632.3 3034.51   665.1 3050.31
   697.8 3072.29  727.25 3074.36   740.4  3076.2   760.1 3093.34   766.6 3096.02
#Mann= 4 ,-1 , 0
       0     .12       0   435.7     .04       0   481.6     .12       0
  727.25     .12       0
Bank Sta=435.7,481.6
XS Rating Curve= 0 ,0
Exp/Cntr=0.3,0.1

Type RM Length L Ch R = 1 ,55405   ,347.3,344.2,344.4
XS GIS Cut Line= 2
     2130365.496      413918.462     2130598.982      414720.556
#Sta/Elev= 30
       0 3160.97     9.8 3159.61    42.6 3145.06   117.9 3105.36   176.9 3079.19
   196.6 3068.27   229.3 3043.93   304.7 2999.49   340.7    2990   350.5 2985.79
     380 2981.66   409.5 2980.63   425.9 2982.65     439 2988.53   484.8 2986.33
   511.1 3001.16   524.2 3002.92   596.2 3020.43   606.1 3025.06   619.2 3036.26
   625.7 3039.93  656.52 3041.62   671.6 3042.69   674.9 3045.12   684.7 3058.41
   720.7 3072.95   737.1  3083.1   750.2 3086.98   792.8  3110.8   835.4 3129.65
#Mann= 4 ,-1 , 0
       0     .12       0     380     .04       0   425.9     .12       0
  656.52     .12       0
Bank Sta=380,425.9
XS Rating Curve= 0 ,0
Exp/Cntr=0.3,0.1

Type RM Length L Ch R = 1 ,55061   ,428.5,429.4,434
XS GIS Cut Line= 2
 2130029.3390212 414046.938354882130303.10991558414852.695873549
#Sta/Elev= 30
       0 3133.39    49.4 3117.04    85.1 3103.31   104.8 3092.85   118.7 3088.72
   175.6 3061.59   227.3 3031.26     240 3028.19   271.6 3011.93   326.6 2993.42
   368.2 2985.53   390.3 2977.24   399.82976.089   413.2 2975.39   440.12977.396
   472.1 2981.36     486 2980.13   511.8 2982.17   555.3 2990.34   603.8 3015.71
   641.9 3016.56   655.8 3014.31   682.5 3018.04     732  3046.8   749.7 3061.65
   771.4 3068.28   791.1  3081.4   818.6 3093.52   842.9 3108.04     851 3110.38
#Mann= 3 , 0 , 0
       0     .12       0   399.8     .04       0   440.1     .12       0
Bank Sta=399.8,440.1
XS Rating Curve= 0 ,0
Exp/Cntr(USF)=0,0
Exp/Cntr=0.3,0.1

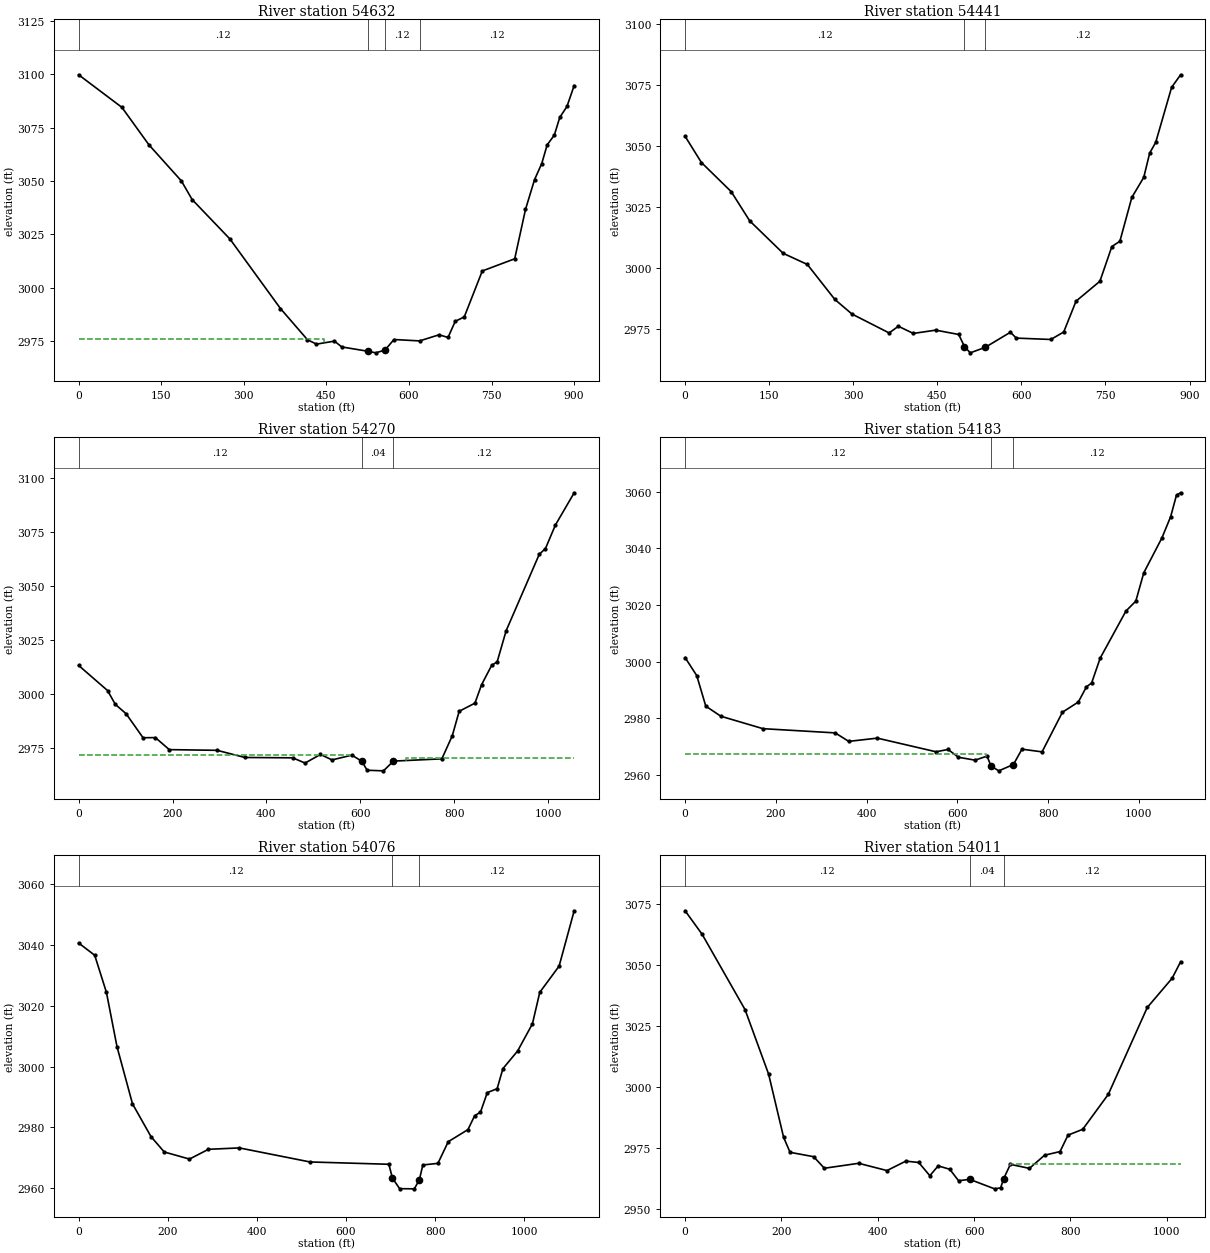
Type RM Length L Ch R = 1 ,54632   ,190.4,190.4,190.4
XS GIS Cut Line= 2
     2129695.253      414086.023     2129846.332       414973.27
#Sta/Elev= 30
       0 3099.81    78.6 3084.54   127.6 3067.02   186.6 3050.08   206.2 3041.34
   274.9 3022.84   366.6 2990.28   415.6 2975.68     432 2973.62   464.7 2975.03
   477.8 2972.31   524.8  2970.3   539.8 2969.54   556.4 2970.84   572.7 2975.78
  619.25 2975.13   654.6 2977.99   670.9 2976.76     684 2984.31   700.4 2986.37
   733.1 3007.89     792  3013.6   811.6 3036.73     828 3050.66   841.1 3058.21
   850.9 3066.92     864 3071.58   873.8 3079.81   886.9 3084.96     900 3094.77
#Mann= 4 ,-1 , 0
       0     .12       0   524.8     .04       0   556.4     .12       0
  619.25     .12       0
#XS Ineff= 2 , 0
          445.74 2975.84
Permanent Ineff=
       F       F
Bank Sta=524.8,556.4
XS Rating Curve= 0 ,0
Exp/Cntr=0.3,0.1

Type RM Length L Ch R = 1 ,54441   ,171.2,171.2,171.2
XS GIS Cut Line= 4
2129511.33587921414114.0958323252129574.06020126414545.928664887
2129644.02194508 414782.351109532129721.22111068414968.111601749
#Sta/Elev= 30
       0 3053.99    29.1 3043.25    82.2 3031.32   115.3 3019.32     175 3006.01
   218.1 3001.45   267.2 2987.09   297.7 2981.12     364 2973.37   380.5 2976.11
   407.1 2973.17   447.2 2974.51   488.2 2972.74   498.4 2967.77   508.8 2965.21
   535.6 2967.48   580.4 2973.65   590.9 2971.25   652.5 2970.69   675.5 2973.76
   697.5  2986.4   740.1 2994.57   761.4  3008.8   775.7 3010.96     797 3028.92
   818.3 3037.16   828.9 3047.13   839.6 3051.48     868 3074.08   884.1 3079.22
#Mann= 3 , 0 , 0
       0     .12       0   498.4     .04       0   535.6     .12       0
Bank Sta=498.4,535.6
XS Rating Curve= 0 ,0
Exp/Cntr(USF)=0,0
Exp/Cntr=0.3,0.1

Type RM Length L Ch R = 1 ,54270   ,87.1,87.1,87.1
XS GIS Cut Line= 4
2129371.53858012414074.8291983392129400.96141164414591.830380772
2129506.04295279414852.4326028122129640.54732545415071.002208394
#Sta/Elev= 30
       0 3013.15    61.6 3001.51    78.1  2995.1   101.1 2990.74   137.2  2979.6
   163.5 2979.66   193.1 2974.08     295 2973.76   354.1 2970.44     456 2970.28
   482.3 2967.85   515.1 2971.85   539.7 2969.31   582.1 2971.53   603.3 2968.66
   614.5 2964.51   649.3 2964.24   670.6 2968.75   773.7 2969.81     796  2980.6
   810.5 2991.86   844.1 2995.65   858.2 3004.17   879.6 3013.13   891.5 3014.87
   910.6 3029.26   981.2 3064.76   994.3 3067.38  1015.5  3078.3  1055.5 3093.28
#Mann= 3 , 0 , 0
       0     .12       0   603.3     .04       0   670.6     .12       0
#XS Ineff= 2 , 0
          578.62  2971.7  697.55         2970.13
Permanent Ineff=
       F       F
Bank Sta=603.3,670.6
XS Rating Curve= 0 ,0
Exp/Cntr(USF)=0,0
Exp/Cntr=0.3,0.1

Type RM Length L Ch R = 1 ,54183   ,107.2,107.2,107.2
XS GIS Cut Line= 4
2129243.55127354414068.2588277522129330.40033484414659.314939359
2129424.48681791414847.4879055032129566.82277948415093.560245846
#Sta/Elev= 30
       0 3001.41    25.7 2995.03    45.6 2984.25    78.8 2980.69   171.6  2976.3
   330.8 2974.81   360.6 2971.81   423.6 2972.96     553 2968.14   579.5 2968.96
   602.3 2966.21     639 2965.18   665.6 2966.62   673.9 2963.14   691.3 2961.41
   723.62963.646   742.4 2969.06   786.7 2968.11   831.5 2982.09   866.7 2985.72
   884.5 2991.08   895.9 2992.42   914.8 3001.21   971.7 3017.87   993.3 3021.33
  1010.9 3031.35  1050.9 3043.67  1070.1 3051.16    1083 3058.79  1092.1 3059.59
#Mann= 3 , 0 , 0
       0     .12       0   673.9     .04       0   723.6     .12       0
#XS Ineff= 2 , 0
          662.81 2967.23
Permanent Ineff=
       F       F
Bank Sta=673.9,723.6
XS Rating Curve= 0 ,0
Exp/Cntr(USF)=0,0
Exp/Cntr=0.3,0.1

Type RM Length L Ch R = 1 ,54076   ,65.2,65.2,65.2
XS GIS Cut Line= 4
2128811.71844098 414273.319111372129248.37622139 414767.87626598
2129385.88723511414912.6247014762129540.28556631415112.860037245
#Sta/Elev= 30
       0 3040.63    36.1  3036.6    62.4 3024.39    86.1 3006.54   120.9 2987.74
   162.4 2976.96   192.2  2971.9   248.8 2969.57   291.3 2972.78   360.7 2973.24
   519.3 2968.62   696.3 2967.86   704.3 2963.31   720.5 2959.83   753.5 2959.78
   764.92962.837   772.5 2967.63   806.4 2968.16   829.6 2975.29   873.8 2979.26
   888.9 2983.85   901.9 2984.98   917.2 2991.43   939.3 2992.71   952.2  2999.3
   985.3 3005.13  1018.5 3014.05    1035 3024.41  1078.4 3033.03  1112.2 3051.23
#Mann= 3 , 0 , 0
       0     .12       0   704.3     .04       0   764.9     .12       0
Bank Sta=704.3,764.9
XS Rating Curve= 0 ,0
Exp/Cntr(USF)=0,0
Exp/Cntr=0.3,0.1

Type RM Length L Ch R = 1 ,54011   ,176.7,176.7,176.7
XS GIS Cut Line= 4
  2128791.488473414436.309699878 2129148.7657129 414764.16410825
2129371.53858012414982.7337138322129535.46578431415146.660918018
#Sta/Elev= 30
       0 3072.37    35.3 3062.75   124.4 3031.87   173.4 3005.39   204.5 2979.51
   217.9 2973.35   266.9 2971.56   289.1 2966.82   360.4 2968.85   419.1 2965.87
   458.3 2969.74   485.1 2969.18   508.1 2963.76   525.4 2967.79   549.4 2966.41
   567.8  2961.7   590.8 2962.28   642.5 2958.38   655.1 2958.78   661.3 2962.52
   675.3 2968.42   714.9 2966.77   746.3 2972.16   778.4 2973.66     795  2980.4
   825.5 2982.78   878.6 2997.11   959.5 3032.72  1011.1  3044.7  1028.8 3051.48
#Mann= 3 , 0 , 0
       0     .12       0   590.8     .04       0   661.3     .12       0
#XS Ineff= 2 , 0
          529.18 2967.23   673.5         2968.36
Permanent Ineff=
       F       F
Bank Sta=590.8,661.3
XS Rating Curve= 0 ,0
Exp/Cntr(USF)=0,0
Exp/Cntr=0.3,0.1

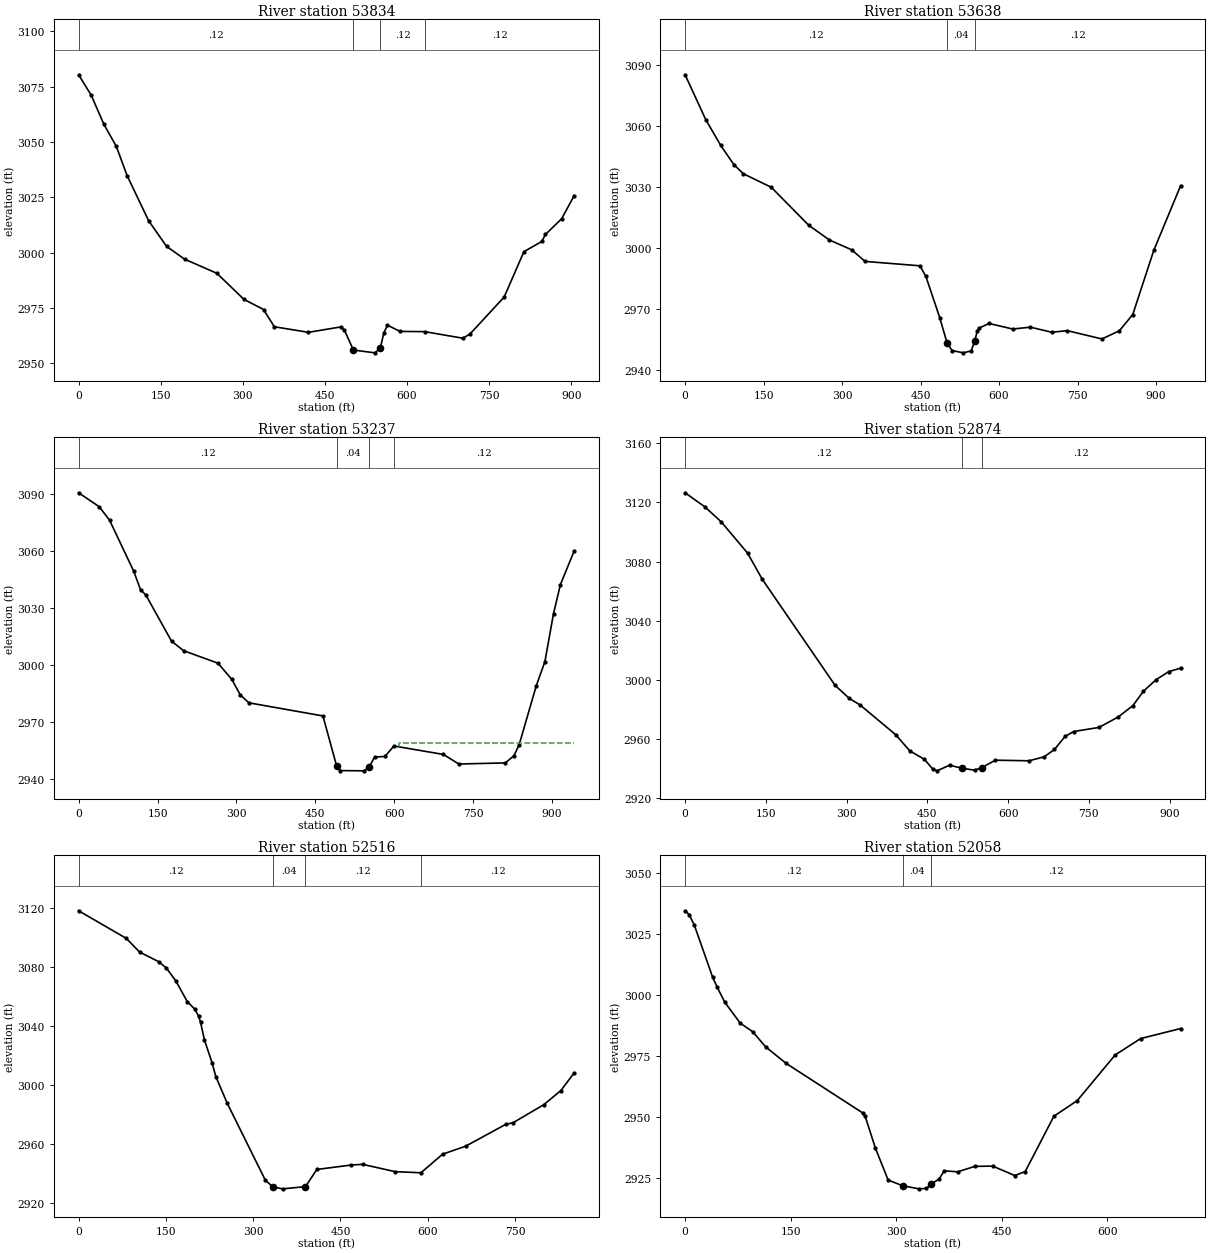
Type RM Length L Ch R = 1 ,53834   ,196,196,196
XS GIS Cut Line= 2
     2128728.346      414715.062     2129470.008      415234.226
#Sta/Elev= 30
       0 3080.38      23 3071.14    45.9 3058.12    68.9 3047.99    88.6  3034.8
   127.9  3014.4   160.7 3002.82   193.5 2997.06   252.6 2990.65   301.8 2978.92
   337.8 2974.29   357.5  2966.5   419.9 2963.98   478.9 2966.42   485.5 2965.03
   501.9 2955.98   541.2 2954.71   551.1 2956.81   557.6 2963.73   564.2 2967.21
   587.1 2964.39  632.29 2964.29     702 2961.31   715.1 2963.26   777.4 2979.92
   813.5 3000.45   846.3 3005.05   852.8 3008.21   882.4 3015.31   905.3 3025.77
#Mann= 4 ,-1 , 0
       0     .12       0   501.9     .04       0   551.1     .12       0
  632.29     .12       0
Bank Sta=501.9,551.1
XS Rating Curve= 0 ,0
Exp/Cntr=0.3,0.1

Type RM Length L Ch R = 1 ,53638   ,401.4,401.4,401.4
XS GIS Cut Line= 4
2128604.24568344414972.9365495992128995.06645927415144.222198269
2129212.18911252 415267.258368442129453.43650501415390.294538612
#Sta/Elev= 30
       0 3085.05    39.4 3063.05    68.1  3050.3    93.2  3040.9   111.1 3036.43
   164.8 3029.72   236.4 3011.04   275.8 3003.83   318.8 2998.94   343.9 2993.29
   448.9 2991.13   460.2 2985.92   486.6 2965.71   500.6 2953.26   510.2 2949.48
   531.8 2948.34   546.9 2949.32   553.5  2954.2   558.3 2958.88     562  2960.5
   580.9 2962.78   626.1 2960.05   660.1 2960.96   700.7 2958.47   730.4 2959.24
   796.7 2955.17   829.9 2959.17   855.6 2967.16   895.8 2998.73   947.1 3030.55
#Mann= 3 , 0 , 0
       0     .12       0   500.6     .04       0   553.5     .12       0
Bank Sta=500.6,553.5
XS Rating Curve= 0 ,0
Exp/Cntr(USF)=0,0
Exp/Cntr=0.3,0.1

Type RM Length L Ch R = 1 ,53237   ,344.4,362.7,382.4
XS GIS Cut Line= 2
     2128549.797      415379.811     2129412.323      415758.883
#Sta/Elev= 30
       0 3090.55    39.3 3083.18    58.9 3076.06   104.7 3049.26   117.8  3039.4
   127.6 3036.79   176.6  3012.4   199.6 3007.35     265 3000.76   291.2 2992.27
   307.5 2983.99   323.9 2979.89   464.5 2972.98   490.7 2946.47   497.2  2944.2
     543 2944.06   552.9 2946.32   562.7 2951.33   582.3 2951.62  599.52 2957.15
   693.5  2952.7     723 2947.65   811.3 2948.24   827.6 2951.98   837.5 2957.73
   870.2 2988.94   886.5 3001.56   902.9 3026.87     916 3042.15   942.2 3059.92
#Mann= 4 ,-1 , 0
       0     .12       0   490.7     .04       0   552.9     .12       0
  599.52     .12       0
#XS Ineff= 2 , 0
                          609.57         2958.92
Permanent Ineff=
       F       F
Bank Sta=490.7,552.9
XS Rating Curve= 0 ,0
Exp/Cntr=0.3,0.1

Type RM Length L Ch R = 1 ,52874   ,378.2,357.7,336.3
XS GIS Cut Line= 4
2128453.98647677415514.2564768852128759.37676867415763.667278716
2128884.02381803415961.5197380292129127.38234299416123.758754666
#Sta/Elev= 30
       0 3126.44    36.4 3117.02    67.2 3106.79   116.2 3085.62   143.2  3068.1
   278.7 2996.36     305 2987.55   325.3 2983.07   391.3 2963.01   417.5 2952.09
   444.7 2946.38   460.2 2939.75     468 2938.63   491.2 2942.41   514.9 2940.36
   537.7 2939.07  551.16 2940.81   576.5 2945.83   638.9 2945.41     667  2948.1
   686.2 2953.05   705.9 2961.87   721.7 2965.17   768.7 2967.94   804.5 2974.98
   832.1 2982.74   851.5 2992.41   875.2 3000.26   898.4 3005.63   920.6 3007.98
#Mann= 3 , 0 , 0
       0     .12       0   514.9     .04       0  551.16     .12       0
Bank Sta=514.9,551.16
XS Rating Curve= 0 ,0
Exp/Cntr(USF)=0,0
Exp/Cntr=0.3,0.1

Type RM Length L Ch R = 1 ,52516   ,461.6,458.8,462.3
XS GIS Cut Line= 2
     2128280.601      415997.863     2129079.948      416291.781
#Sta/Elev= 30
       0 3118.18    81.9 3099.49   104.8 3090.22   137.6 3083.71   150.7 3079.44
   167.1 3070.67   186.7 3056.67   199.8 3051.51   206.4 3046.59   209.6 3042.62
   216.2 3030.74   229.3  3015.3   235.8 3005.88   255.5 2987.75     321 2935.62
   334.1  2931.1   350.5 2929.86   389.8 2931.33   409.5 2942.99   468.4 2945.99
   488.1 2946.45   543.8 2941.51  588.37 2940.74   625.6 2953.35     665 2958.71
   733.8 2973.47   746.8 2974.66   799.3 2986.81   828.7 2996.36   851.7 3008.39
#Mann= 4 ,-1 , 0
       0     .12       0   334.1     .04       0   389.8     .12       0
  588.37     .12       0
Bank Sta=334.1,389.8
XS Rating Curve= 0 ,0
Exp/Cntr=0.3,0.1

Type RM Length L Ch R = 1 ,52058   ,201.2,206.2,219.8
XS GIS Cut Line= 2
2128257.77238419416431.9701252972128895.29697531416730.947174925
#Sta/Elev= 30
       0 3034.67     5.8  3033.1    13.1 3028.78    39.2 3007.38    45.7 3003.24
    56.5 2997.13    78.3 2988.58      96 2985.08   114.5 2978.85   143.5 2972.08
   252.2 2951.78   255.9 2950.32   270.4  2937.3   288.5 2924.21   309.2 2921.89
     332 2920.61   342.8 2920.78     350 2922.63     361 2924.66   368.2 2928.02
   387.1 2927.58   411.7 2929.82   437.1 2929.94   468.5 2926.06   483.3 2927.72
     524 2950.38   557.3 2956.83     611 2975.51   647.2 2982.25   704.1 2986.37
#Mann= 3 , 0 , 0
       0     .12       0   309.2     .04       0     350     .12       0
Bank Sta=309.2,350
XS Rating Curve= 0 ,0
Exp/Cntr(USF)=0,0
Exp/Cntr=0.3,0.1