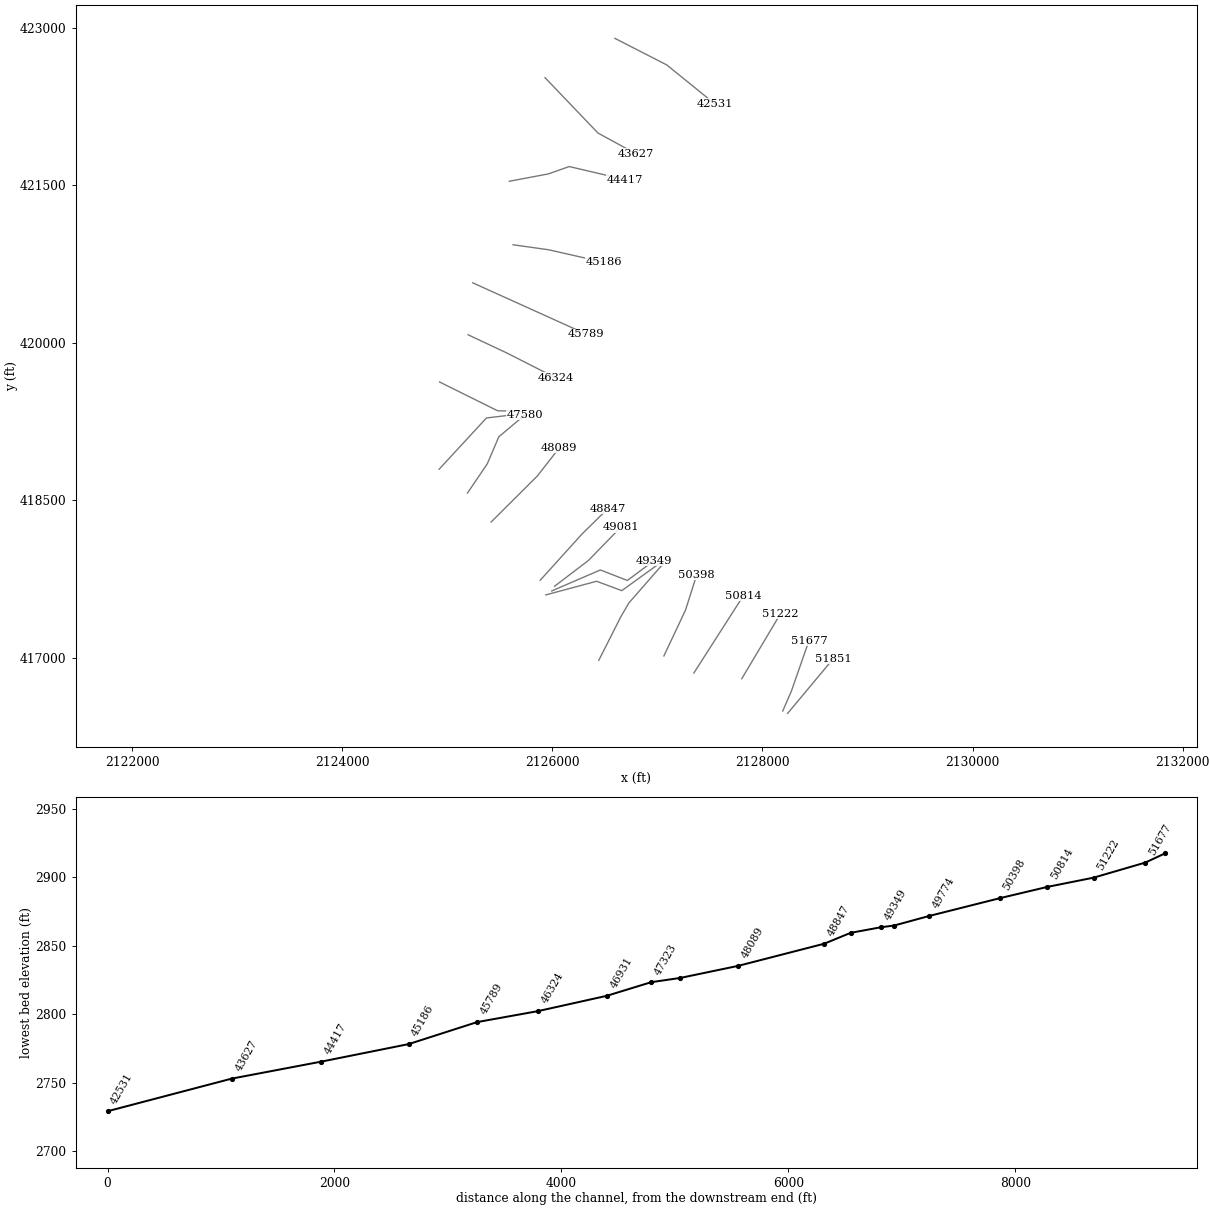
HEC-RAS study SFKCHERRYRV.prj: SFKCHERRYRV

--- SFKCHERRYRV.g01 (geometry) --- (continued)

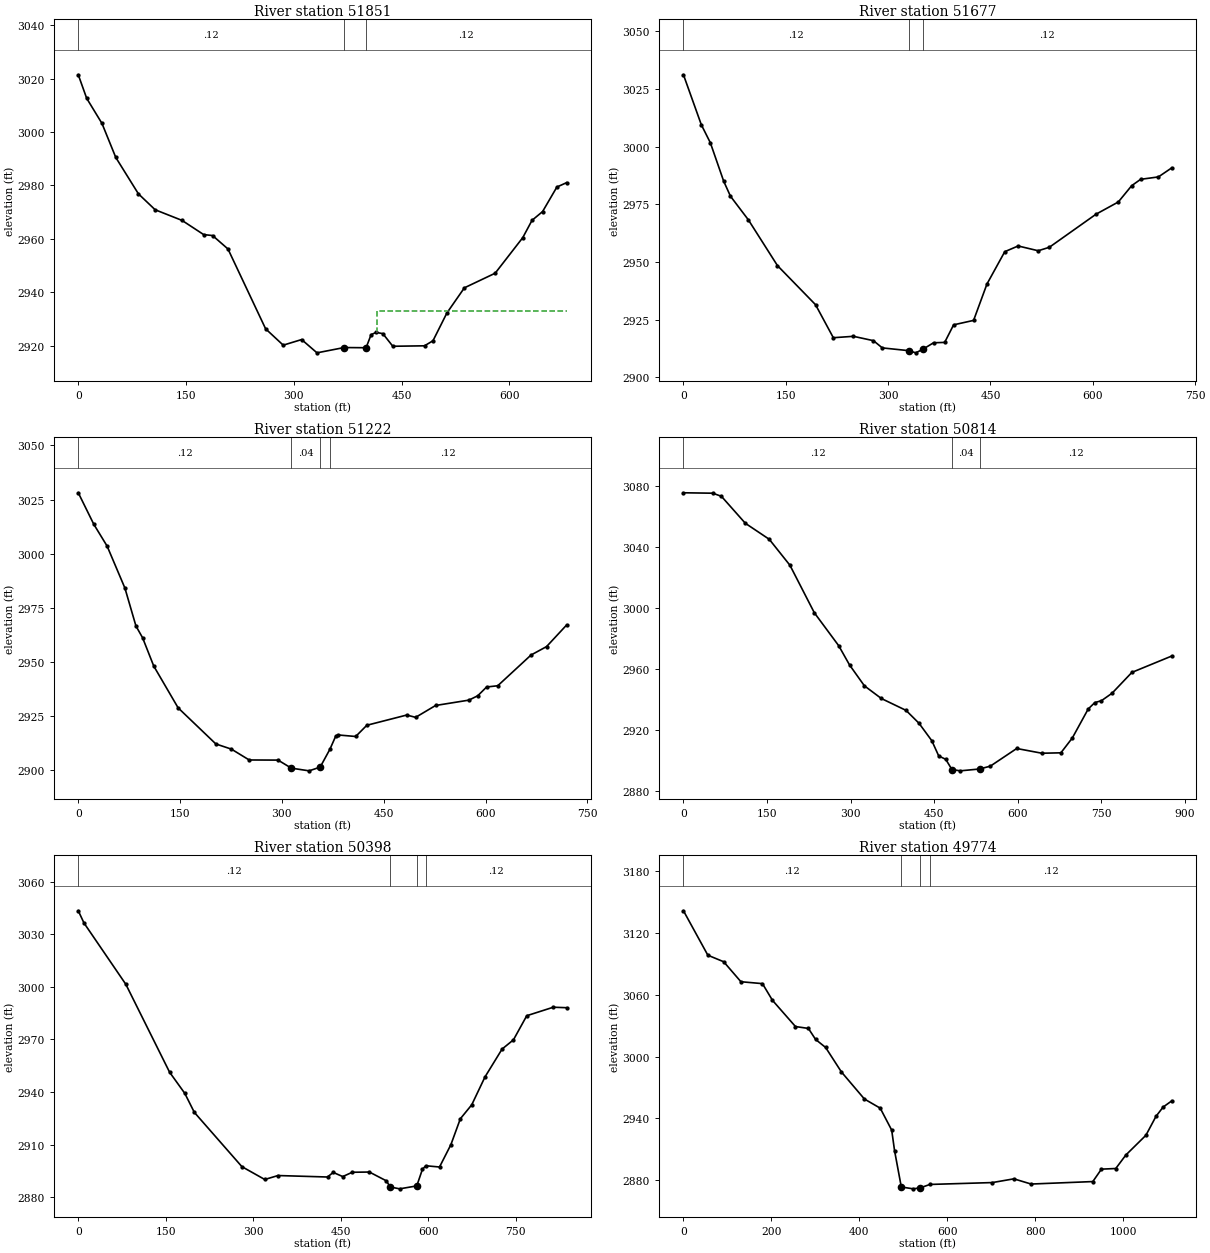
Type RM Length L Ch R = 1 ,51851   ,167,174.2,186.1
XS GIS Cut Line= 2
2128239.44342766416469.9211426452128674.88847929416991.548027419
#Sta/Elev= 30
       0 3021.44    11.7 3012.63      33 3003.22    52.2 2990.49    83.7 2976.87
     107 2970.91   144.4 2966.93   174.5 2961.62   186.9 2961.26   208.3 2956.24
   260.7 2926.35   285.2 2920.23   310.8 2922.33   332.2 2917.36   369.92919.341
   400.5 2919.27   407.5 2924.17   414.4 2925.01   423.8 2924.55   437.7 2919.82
   481.8 2919.99   493.6 2921.89     513  2932.3   537.3  2941.7   580.1 2947.16
   618.5 2960.47   631.4 2966.95   646.1 2970.24     666 2979.42   679.5 2981.06
#Mann= 3 , 0 , 0
       0     .12       0   369.9     .04       0   400.5     .12       0
#XS Ineff= 2 , 0
                          415.96         2933.04
Permanent Ineff=
       F       F
Bank Sta=369.9,400.5
XS Rating Curve= 0 ,0
Exp/Cntr(USF)=0,0
Exp/Cntr=0.3,0.1

Type RM Length L Ch R = 1 ,51677   ,457.2,455.1,454.1
XS GIS Cut Line= 3
     2128192.701      416492.304     2128275.108       416681.84
     2128442.668      417162.547
#Sta/Elev= 30
       0 3031.12    26.2 3009.46    39.4 3001.68      59 2984.99    68.9 2978.51
    95.1 2968.29   137.8 2948.44   193.6 2931.51   219.7  2917.2   249.1 2917.81
   278.5 2915.92   291.5 2912.79   330.7 2911.58   340.5 2910.65   350.5 2912.13
   366.6 2915.01   382.9 2915.17     396 2922.78   425.3 2924.71   444.9 2940.47
     471 2954.48   490.6 2956.95     520 2954.88   536.3 2956.38   604.8 2970.72
   637.4    2976     657 2983.06   670.1 2985.82   696.2 2986.87   715.8  2990.8
#Mann= 3 , 0 , 0
       0     .12       0   330.7     .04       0   350.5     .12       0
Bank Sta=330.7,350.5
XS Rating Curve= 0 ,0
Exp/Cntr=0.3,0.1

Type RM Length L Ch R = 1 ,51222   ,415.3,407.5,408.8
XS GIS Cut Line= 2
     2127802.641      416799.956     2128170.726      417418.008
#Sta/Elev= 30
       0 3028.13    22.9 3013.56    42.5 3003.49    68.7 2984.11      85 2966.56
    94.8 2961.12   111.2 2948.07   147.1 2928.77   202.7 2912.09   225.6  2909.7
   251.8 2904.69   294.3 2904.63   313.9 2900.91   340.1 2899.67   356.4  2901.4
   370.7 2909.63   379.3 2915.71   382.6 2916.25   408.7 2915.54   425.1 2920.72
   483.9 2925.45     497 2924.38   526.4 2929.86   575.5 2932.34   588.6 2934.37
   601.6 2938.41     618 2938.98     667 2953.17   689.9 2957.07   719.4 2967.03
#Mann= 4 ,-1 , 0
       0     .12       0   313.9     .04       0   356.4     .12       0
   370.7     .12       0
Bank Sta=313.9,356.4
XS Rating Curve= 0 ,0
Exp/Cntr=0.3,0.1

Type RM Length L Ch R = 1 ,50814   ,412.3,416.1,427.1
XS GIS Cut Line= 2
2127346.33865413416854.4788156392127819.20603188417592.468488877
#Sta/Elev= 30
       0 3075.74    52.7 3075.46    68.2 3073.39   111.1 3055.68     154 3045.16
   191.1  3028.1   234.9 2996.86   278.7 2975.18   298.1 2962.56   324.8 2948.81
   355.2 2940.49   399.5 2932.68   422.8 2924.21   445.8 2912.73   458.2 2902.71
   470.8  2900.5   481.9 2893.78   496.9 2892.93   531.6 2894.15   550.8 2896.01
   598.2 2907.62   643.4  2904.5   677.5 2904.78     698 2914.54   726.5 2933.59
   738.4 2937.81   750.3 2939.05   769.3 2943.95   804.9 2957.65   876.5 2968.42
#Mann= 3 , 0 , 0
       0     .12       0   481.9     .04       0   531.6     .12       0
Bank Sta=481.9,531.6
XS Rating Curve= 0 ,0
Exp/Cntr(USF)=0,0
Exp/Cntr=0.3,0.1

Type RM Length L Ch R = 1 ,50398   ,649.6,624.1,635.8
XS GIS Cut Line= 3
     2127060.979      417016.961     2127266.997      417453.718
     2127374.126      417791.586
#Sta/Elev= 30
       0 3043.42     9.8 3036.45    81.6 3001.45   156.6 2951.31   182.7 2939.23
     199 2928.41   280.6 2897.42   319.8  2890.1   342.6 2892.35   427.4 2891.51
   437.2 2894.14   453.5 2891.76   469.9 2894.22   499.2 2894.35   528.4 2889.31
   534.9 2885.82   551.2 2884.76   580.5 2886.44   590.2 2895.93  595.97 2897.93
   619.5 2897.22     639 2909.97   655.2 2924.74   674.8 2932.73   697.5 2948.63
   726.8 2964.52   746.3 2969.79   769.1 2983.54   814.6 2988.39   837.4 2988.11
#Mann= 4 ,-1 , 0
       0     .12       0   534.9     .04       0   580.5     .12       0
  595.97     .12       0
Bank Sta=534.9,580.5
XS Rating Curve= 0 ,0
Exp/Cntr=0.3,0.1

Type RM Length L Ch R = 1 ,49774   ,354.4,310.5,261.3
XS GIS Cut Line= 4
     2126441.125      416975.477     2126651.986      417392.334
     2126728.221      417522.096     2127052.624      417893.537
#Sta/Elev= 30
       0 3141.45    55.5 3098.35    91.5 3092.02   130.7 3072.64   179.7 3070.79
   202.5 3054.58   254.8 3029.17   284.2 3027.34   300.6 3016.66   323.4 3008.87
   359.4 2985.08   411.6 2958.89   447.6    2950   473.7  2928.7   480.2 2908.78
  495.56 2873.55   522.8 2871.76   539.1 2872.78  560.57 2876.02   702.6 2877.84
   751.6 2881.46   790.8 2876.41   931.2 2878.81   950.8 2890.86   983.4 2891.48
  1006.3 2904.54    1052 2923.72  1074.9 2942.07  1091.2  2951.1  1110.8 2957.07
#Mann= 4 ,-1 , 0
       0     .12       0  495.56     .04       0   539.1     .12       0
  560.57     .12       0
Bank Sta=495.56,539.1
XS Rating Curve= 0 ,0
Exp/Cntr=0.5,0.3

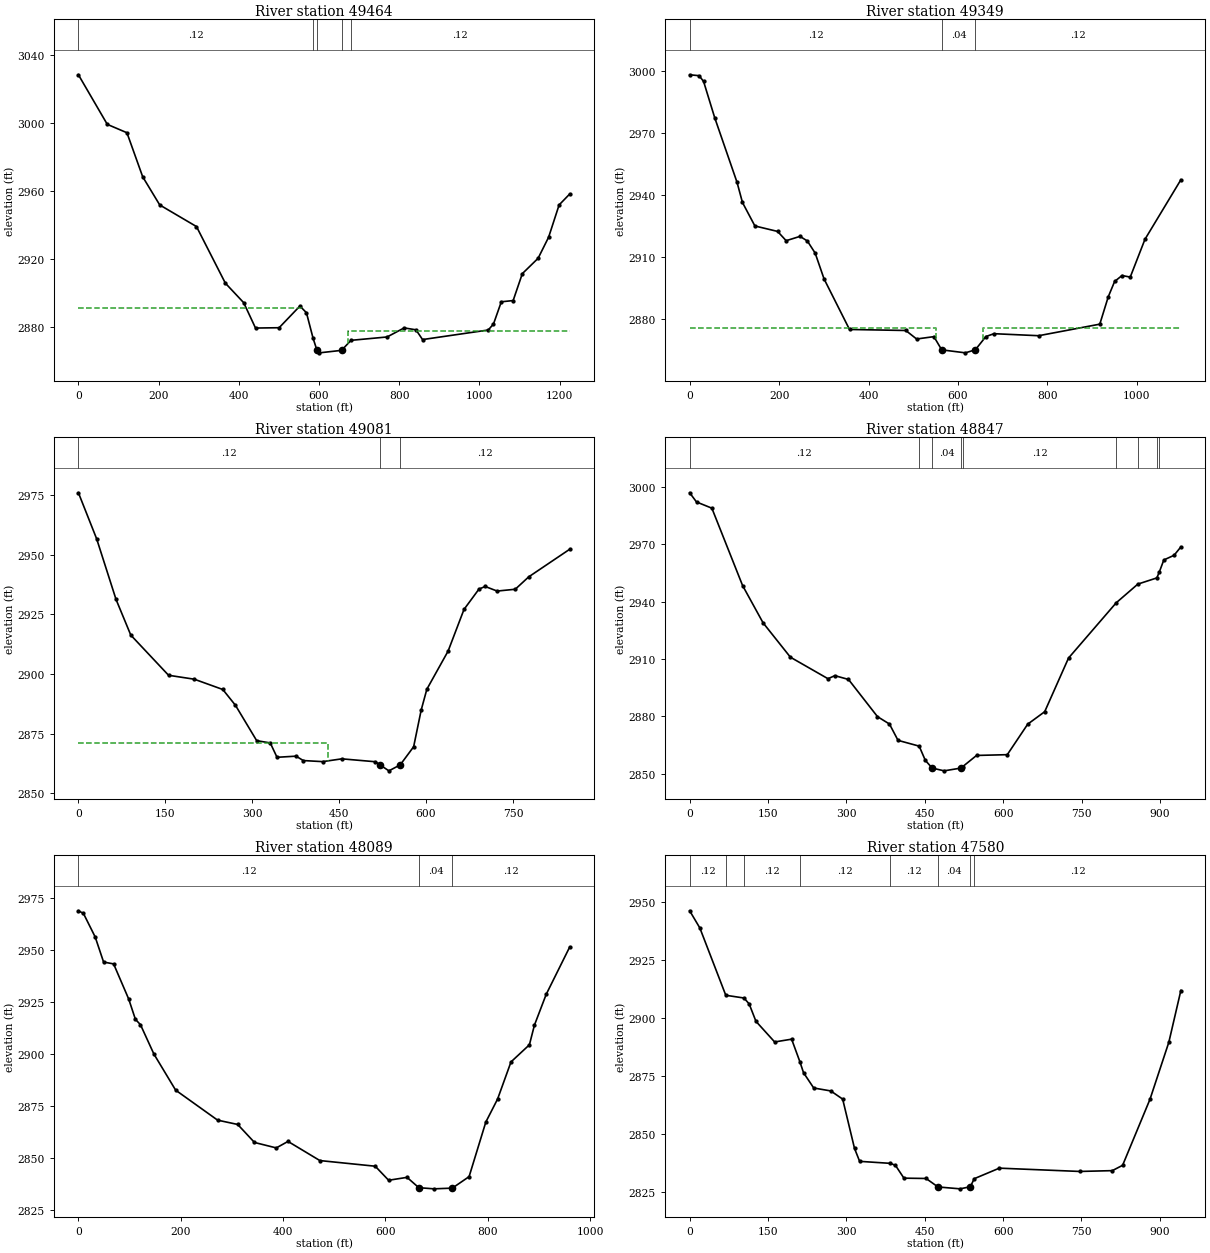
Type RM Length L Ch R = 1 ,49464   ,119,115.1,115.1
XS GIS Cut Line= 4
     2125936.678       417598.33     2126420.038      417728.092
     2126660.097      417638.881     2127039.648      417913.001
#Sta/Elev= 30
       0 3028.39      72 2999.21     121 2994.28   160.3 2968.35   202.8 2951.78
   294.4 2939.07   366.4 2905.76   412.2 2894.25   441.6 2879.35   500.5 2879.54
   552.3  2892.3   568.6 2888.35  585.19  2873.3   594.5 2866.51     601 2864.76
   656.1 2866.22  679.72 2872.12   769.7  2874.1   812.2 2879.43   841.7 2878.31
   858.1 2872.57  1021.8 2878.19  1034.9 2881.67  1054.5  2894.8    1084 2895.52
  1106.9 2911.37  1146.2 2920.39  1172.4 2932.78  1198.6  2951.8  1224.8 2958.17
#Mann= 5 ,-1 , 0
       0     .12       0  585.19     .08       0   594.5     .04       0
   656.1     .12       0  679.72     .12       0
#XS Ineff= 2 , 0
          558.12 2891.26     671         2877.32
Permanent Ineff=
       F       F
Bank Sta=594.5,656.1
XS Rating Curve= 0 ,0
Exp/Cntr=0.5,0.3

Type RM Length L Ch R = 1 ,49349   ,220.3,267.6,307.7
XS GIS Cut Line= 4
2125992.55176664417635.6955352962126455.89251689 417835.72810589
2126713.07725052417735.7118205932126968.22083546 417925.53864779
#Sta/Elev= 30
       0 2998.28    21.1 2997.84    31.1 2995.08      56 2977.49     106 2946.14
   118.1 2936.39   145.9 2925.01   196.7 2922.36   215.8 2917.87   246.8 2919.96
   263.2 2917.74   280.7 2911.86   300.6 2899.34   357.5 2874.85   483.4 2874.35
   507.6 2870.23   546.3 2871.37   563.7 2864.97   616.7 2863.52     6392865.005
   662.5 2871.41   680.6  2872.8   780.6 2871.82   917.3 2877.42   936.2 2890.66
   950.5 2898.12     967 2900.99   985.4 2900.23  1018.3 2918.54  1098.6 2947.38
#Mann= 3 , 0 , 0
       0     .12       0   563.7     .04       0     639     .12       0
#XS Ineff= 2 , 0
          550.95 2875.52  657.11         2875.52
Permanent Ineff=
       F       F
Bank Sta=563.7,639
XS Rating Curve= 0 ,0
Exp/Cntr(USF)=0,0
Exp/Cntr=0.5,0.3

Type RM Length L Ch R = 1 ,49081   ,244.4,234.4,233.9
XS GIS Cut Line= 3
2126019.84123329417680.6389796292126343.00025017417926.855373441
2126650.77074243418243.419308342
#Sta/Elev= 30
       0    2976    31.5 2956.68    64.9 2931.32    90.4 2916.34   155.6  2899.5
     200 2897.85   249.2 2893.54   271.1  2886.9   307.7 2872.09   331.1 2871.14
   342.8 2865.12   375.6 2865.59   388.2 2863.75   421.5  2863.3   454.7 2864.47
   512.7 2863.25  520.54 2861.94   535.9 2859.44   555.42861.938   578.6 2869.54
   591.6  2884.9   601.4 2893.65   638.1 2909.65   665.5  2927.1   691.4 2935.64
   702.1 2936.72   722.7  2934.8     754 2935.56   777.2 2940.75   847.8  2952.3
#Mann= 3 , 0 , 0
       0     .12       0  520.54     .04       0   555.4     .12       0
#XS Ineff= 2 , 0
          431.24 2871.25
Permanent Ineff=
       F       F
Bank Sta=520.54,555.4
XS Rating Curve= 0 ,0
Exp/Cntr(USF)=0,0
Exp/Cntr=0.3,0.1

Type RM Length L Ch R = 1 ,48847   ,773.1,757.6,779.7
XS GIS Cut Line= 3
     2125883.151      417737.824     2126282.167      418179.012
     2126528.713      418420.692
#Sta/Elev= 30
       0    2997    13.1 2992.19    42.5 2988.94   101.3 2948.45   140.5 2928.94
   192.8 2910.95   264.8 2899.68   277.8 2901.29     304  2899.3   359.5 2879.83
   382.4 2875.97   398.8 2867.42  439.26  2864.4     451 2856.98   464.1 2852.92
     487 2851.47   519.7 2852.94  522.49 2853.66   549.1 2859.53   607.9 2859.93
     647  2875.9   679.5 2882.42   725.1 2910.49   816.4 2939.43  857.76  2949.2
  894.13 2952.44  899.12 2955.72   907.5 2961.84   927.1 2964.28   940.1 2968.66
#Mann= 9 ,-1 , 0
       0     .12       0  439.26     .12       0   464.1     .04       0
   519.7     .12       0  522.49     .12       0   816.4     .06       0
  857.76     .08       0  894.13     .06       0  899.12     .12       0
Bank Sta=464.1,519.7
XS Rating Curve= 0 ,0
Exp/Cntr=0.3,0.1

Type RM Length L Ch R = 1 ,48089   ,504.2,508.7,524.2
XS GIS Cut Line= 3
     2125416.011      418292.553     2125857.199      418732.119
     2126064.817      418998.129
#Sta/Elev= 30
       0 2968.81     9.8 2967.55    32.8 2956.23    49.2  2944.2    68.8 2943.31
    98.3 2926.45   111.4 2916.71   121.3 2914.13   147.5 2900.07   190.1  2882.7
   272.1 2868.31   311.4 2866.24   344.2  2857.6   386.8 2854.98   409.7  2858.1
     472 2848.91   580.2  2846.2   606.4 2839.46   642.4 2840.85   665.4  2835.9
   694.9 2835.34   730.9 2835.68   763.7  2841.2   796.4 2867.39   819.4 2878.44
   845.6 2896.26   881.6 2904.48   891.4 2913.89   914.4 2928.68   960.2 2951.33
#Mann= 3 , 0 , 0
       0     .12       0   665.4     .04       0   730.9     .12       0
Bank Sta=665.4,730.9
XS Rating Curve= 0 ,0
Exp/Cntr=0.3,0.1

Type RM Length L Ch R = 1 ,47580   ,265.2,257.7,240
XS GIS Cut Line= 4
     2125190.551      418568.295     2125378.705       418845.66
     2125489.002       419103.56      2125737.17        419312.8
#Sta/Elev= 30
       0 2946.32    19.5 2938.92   69.17 2909.93  103.96 2908.75   113.9 2906.21
   126.9 2898.71   162.7 2889.82   195.2 2891.02  211.03 2881.29     218 2876.57
   237.5 2869.99   270.1 2868.73   292.9 2865.21   315.6 2843.96   325.4  2838.4
  384.06 2837.54   393.9 2836.69   410.2 2831.16   452.6 2831.02   475.4 2827.37
   517.8 2826.56   537.4 2827.48  544.68 2830.92   592.8 2835.47   746.8 2834.05
   809.1  2834.4   828.8  2836.7   881.2 2865.13   917.3 2889.71   940.3 2911.98
#Mann= 8 ,-1 , 0
       0     .12       0   69.17     .08       0  103.96     .12       0
  211.03     .12       0  384.06     .12       0   475.4     .04       0
   537.4     .12       0  544.68     .12       0
Bank Sta=475.4,537.4
XS Rating Curve= 0 ,0
Exp/Cntr=0.3,0.1

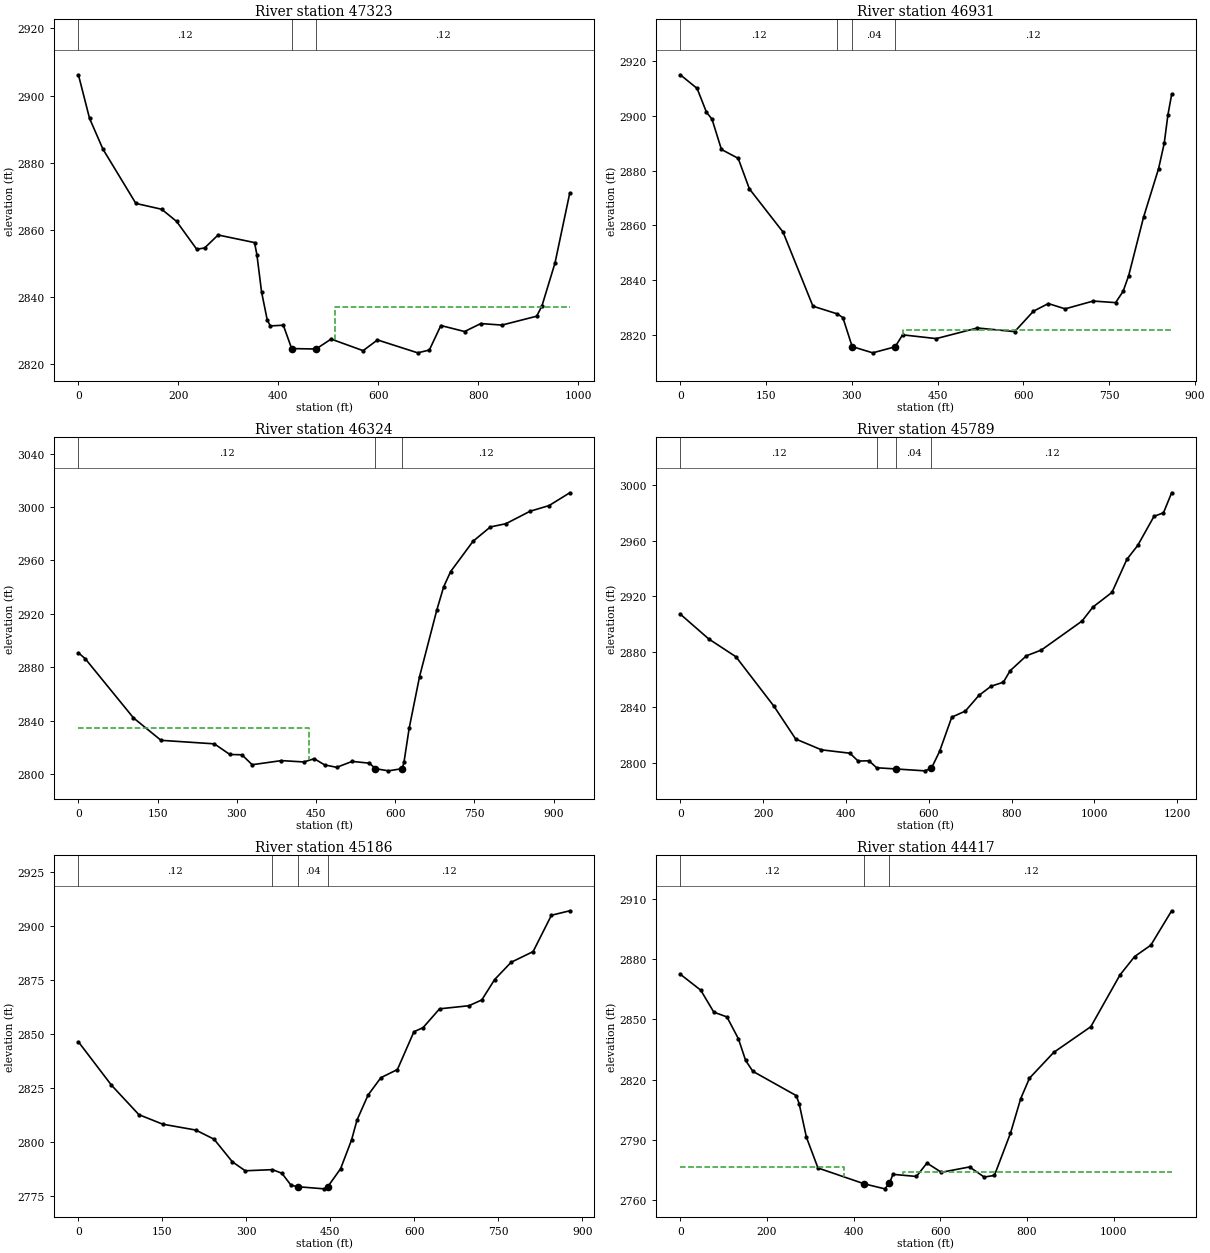
Type RM Length L Ch R = 1 ,47323   ,435,391.3,348.2
XS GIS Cut Line= 3
2124920.66090377 418795.207833762125371.32483887419283.243900066
2125687.88877377 419320.61603127
#Sta/Elev= 30
       0 2906.18    22.2 2893.23      49 2884.07   114.9  2867.9   166.6 2866.16
   196.4 2862.55   236.6 2854.28   252.5 2854.64   279.4 2858.51   352.3 2856.25
     357  2852.7   366.4 2841.56   377.8 2833.17     384 2831.45   409.9 2831.66
   426.6 2824.71   475.4 2824.58   505.5 2827.54   569.5 2824.09   598.3 2827.28
   678.8 2823.44     702 2824.27   725.1 2831.57   772.5 2829.78     805 2832.15
   847.3  2831.7   916.7 2834.34   927.2 2837.35   953.4 2850.16     983 2871.02
#Mann= 3 , 0 , 0
       0     .12       0   426.6     .04       0   475.4     .12       0
#XS Ineff= 2 , 0
                          512.73         2837.09
Permanent Ineff=
       F       F
Bank Sta=426.6,475.4
XS Rating Curve= 0 ,0
Exp/Cntr(USF)=0,0
Exp/Cntr=0.3,0.1

Type RM Length L Ch R = 1 ,46931   ,628.5,607,616.5
XS GIS Cut Line= 3
     2124924.541      419625.849     2125477.648      419351.728
     2125719.328      419346.862
#Sta/Elev= 30
       0 2914.94    29.4 2909.96    45.7 2901.31    55.5 2898.72    71.9  2887.7
   101.2 2884.46   120.8 2873.32   179.6 2857.57   231.9 2830.52  274.29 2827.72
   284.2 2826.37   300.5 2815.78   336.4  2813.5   375.6  2815.7   388.7 2820.07
   447.5 2818.69   519.3 2822.57   584.6 2821.24   617.3 2828.68   643.4 2831.47
   672.8 2829.55   721.8 2832.39     761 2831.82   774.1 2835.92   783.9 2841.69
     810 2863.07   836.2 2880.74     846 2889.91   852.5 2900.36     859 2907.77
#Mann= 4 ,-1 , 0
       0     .12       0  274.29     .12       0   300.5     .04       0
   375.6     .12       0
#XS Ineff= 2 , 0
                          389.36         2821.69
Permanent Ineff=
       F       F
Bank Sta=300.5,375.6
XS Rating Curve= 0 ,0
Exp/Cntr=0.3,0.1

Type RM Length L Ch R = 1 ,46324   ,556.2,535.7,543.8
XS GIS Cut Line= 3
     2125196.198      420075.648     2125570.663      419899.429
     2126031.235      419665.138
#Sta/Elev= 30
       0 2890.75      13 2886.29   104.3 2841.98   156.4 2825.19   257.4 2822.55
   286.8 2814.58   309.6 2814.35   329.1 2806.92   384.5 2809.99   426.9 2808.98
   446.6 2811.41   466.2  2806.8   489.1 2804.96   518.5  2809.4   551.2 2808.06
  562.53 2803.95   587.2 2802.33   613.4    2804   616.6 2808.81   626.4 2834.23
   646.1 2872.95   678.8 2922.86   691.8 2940.23   704.9 2951.58   747.4 2974.32
   780.2 2985.03   809.6 2987.46   855.4  2996.8   891.4 3001.04   930.6 3010.63
#Mann= 3 , 0 , 0
       0     .12       0  562.53     .04       0   613.4     .12       0
#XS Ineff= 2 , 0
          436.33 2834.76
Permanent Ineff=
       F       F
Bank Sta=562.53,613.4
XS Rating Curve= 0 ,0
Exp/Cntr=0.3,0.1

Type RM Length L Ch R = 1 ,45789   ,605,603.2,614.3
XS GIS Cut Line= 2
     2125240.253      420570.262     2126321.596      420081.655
#Sta/Elev= 30
       0 2907.24    68.8 2889.35   134.4 2876.52   226.2 2840.88   278.6 2817.29
   340.9 2809.48   409.7 2807.03   429.4 2801.38   455.6  2801.6  474.24 2796.56
   521.2 2795.69     590 2794.34   606.4 2796.17   626.1 2808.29   655.6 2833.01
   688.4  2837.4   721.1 2848.66   750.6 2855.31   780.2 2858.18   796.5 2866.45
   835.9 2877.24   871.9 2881.36   970.3 2902.28   996.5 2912.35  1042.4 2922.89
  1078.4 2946.66  1104.7 2956.75    1144  2977.7  1166.9 2980.25  1186.6 2994.67
#Mann= 4 ,-1 , 0
       0     .12       0  474.24     .12       0   521.2     .04       0
   606.4     .12       0
Bank Sta=521.2,606.4
XS Rating Curve= 0 ,0
Exp/Cntr=0.3,0.1

Type RM Length L Ch R = 1 ,45186   ,754.9,768.5,792.6
XS GIS Cut Line= 3
      2125624.73      420932.712     2125965.153      420884.652
       2126485.8      420766.506
#Sta/Elev= 30
       0  2846.4    58.9 2826.35     108 2812.66   150.6 2808.24   209.6 2805.53
   242.3 2801.28     275  2790.8     298 2786.66  346.49 2787.18   363.4 2785.52
   379.8 2779.95   392.9 2779.25   438.8 2778.29   445.3 2779.25   468.3  2787.6
   487.9 2800.94   497.7  2810.2   517.4 2821.75   540.3  2829.8   569.8 2833.56
   599.3 2851.08   615.6 2852.97   645.1 2861.69   697.5 2863.13   720.5  2865.8
   743.4 2875.24   772.9 2883.25   812.2 2888.21   844.9 2905.05   877.7 2907.12
#Mann= 4 ,-1 , 0
       0     .12       0  346.49     .12       0   392.9     .04       0
   445.3     .12       0
Bank Sta=392.9,445.3
XS Rating Curve= 0 ,0
Exp/Cntr=0.3,0.1

Type RM Length L Ch R = 1 ,44417   ,826,790.2,772.1
XS GIS Cut Line= 4
     2125588.686      421537.463     2125961.148       421607.55
     2126159.395      421677.6372126689.35142879421553.394131472
#Sta/Elev= 30
       02872.576  47.2392864.603  77.2852853.669  107.582851.277 134.0382840.401
  150.732829.565 167.4222824.146 267.5742812.027 274.2512807.988 290.9432791.287
 317.6512775.934   424.32768.036 471.6442765.531   482.52768.223 490.5762772.775
 544.7212771.701 569.0792778.379  602.332773.782 667.442 2776.45  701.14  2771.4
 724.7282772.225 761.796 2793.31 785.3842810.521 805.603 2820.73 861.662 2833.61
 947.1342846.402 1014.53 2872.251048.2282881.4071085.5072887.0511133.5962904.219
#Mann= 3 ,-1 , 0
       0     .12       0   424.3     .04       0   482.5     .12       0
#XS Ineff= 2 , 0
          377.51 2776.22  512.93         2774.05
Permanent Ineff=
       F       F
Bank Sta=424.3,482.5
XS Rating Curve= 0 ,0
Exp/Cntr=0.3,0.1

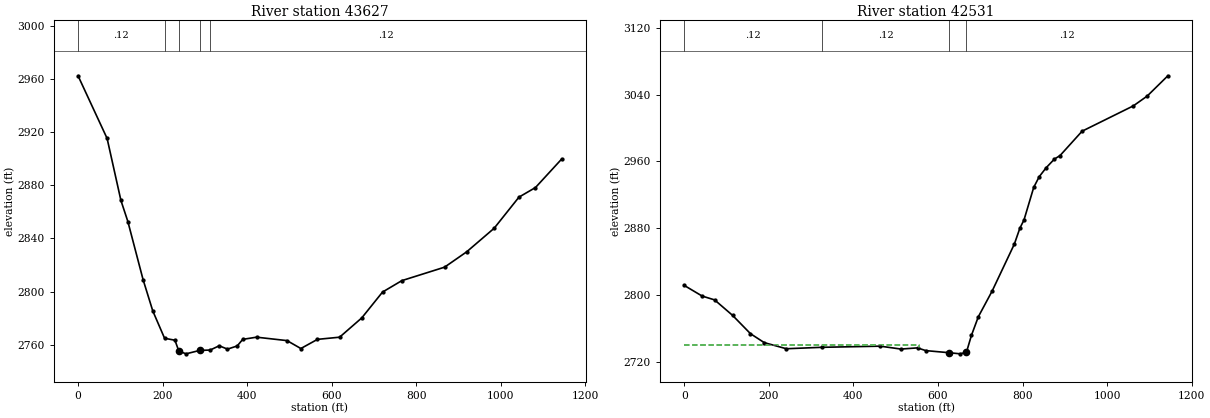
Type RM Length L Ch R = 1 ,43627   ,1097.9,1095.4,1106.5
XS GIS Cut Line= 3
     2125928.944      422523.893     2126433.796      421996.093
     2126797.679      421798.118
#Sta/Elev= 30
       0  2962.3    68.8 2915.16   101.5  2868.5   117.9 2852.68   153.9 2808.98
   176.9 2785.39  204.79 2764.84   229.3 2763.38  238.48 2755.27   255.5 2753.13
   288.2 2755.72  312.56 2755.98   334.1 2759.18   353.7 2756.68   376.6 2759.05
   389.8 2764.02   422.5 2765.66   494.6 2763.08   527.3 2757.13   566.6 2764.02
     619 2765.65   671.4 2780.14   720.6  2799.6   766.3  2808.2   867.4 2818.32
   919.6 2829.84   984.8 2847.61  1043.5 2871.02  1082.6 2878.24  1144.6 2899.69
#Mann= 5 ,-1 , 0
       0     .12       0  204.79     .06       0  238.48     .04       0
   288.2     .08       0  312.56     .12       0
#XS Ineff= 2 , 0
                          447.66         2764.07
Permanent Ineff=
       F       F
Bank Sta=238.48,288.2
XS Rating Curve= 0 ,0
Exp/Cntr=0.3,0.1

Type RM Length L Ch R = 1 ,42531   ,644.3,670.4,693.1
XS GIS Cut Line= 3
     2126594.091      422898.535      2127087.93      422645.593
     2127545.635      422275.214
#Sta/Elev= 30
       0 2811.36    42.4 2798.59    71.8    2794   114.2 2775.51   156.7 2753.47
   189.3 2742.75   241.5 2735.44  325.05 2737.16   463.5 2738.52   512.4 2735.06
   551.6 2736.48   571.2  2733.2   626.8 2730.66     653 2729.33  667.43 2731.42
   679.2 2751.56   695.5 2773.86   728.2 2804.72   780.6  2860.9   793.6  2879.9
   803.4 2889.82   826.4 2928.89   839.4 2941.69   855.8 2952.43   875.4 2962.86
   888.5 2966.94   940.8 2996.23  1061.9 3026.58  1094.6  3038.3  1143.6 3062.66
#Mann= 4 ,-1 , 0
       0     .12       0  325.05     .12       0   626.8     .04       0
  667.43     .12       0
#XS Ineff= 2 , 0
          554.04 2739.86
Permanent Ineff=
       F       F
Bank Sta=626.8,667.43
XS Rating Curve= 0 ,0
Exp/Cntr=0.3,0.1