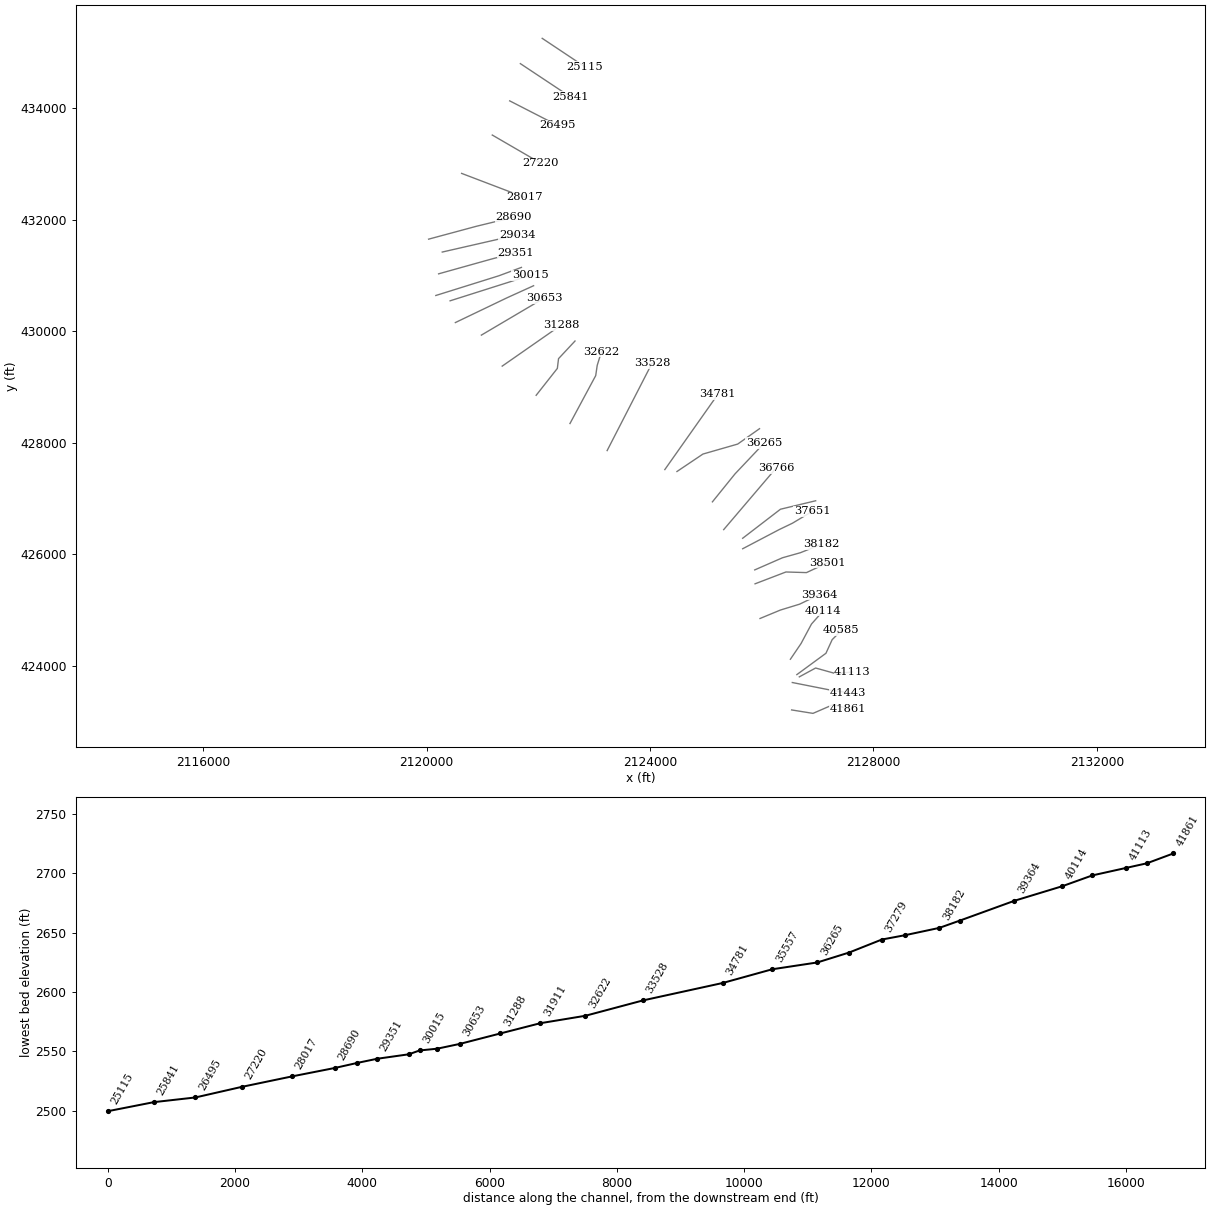
HEC-RAS study SFKCHERRYRV.prj: SFKCHERRYRV

--- SFKCHERRYRV.g01 (geometry) --- (continued)

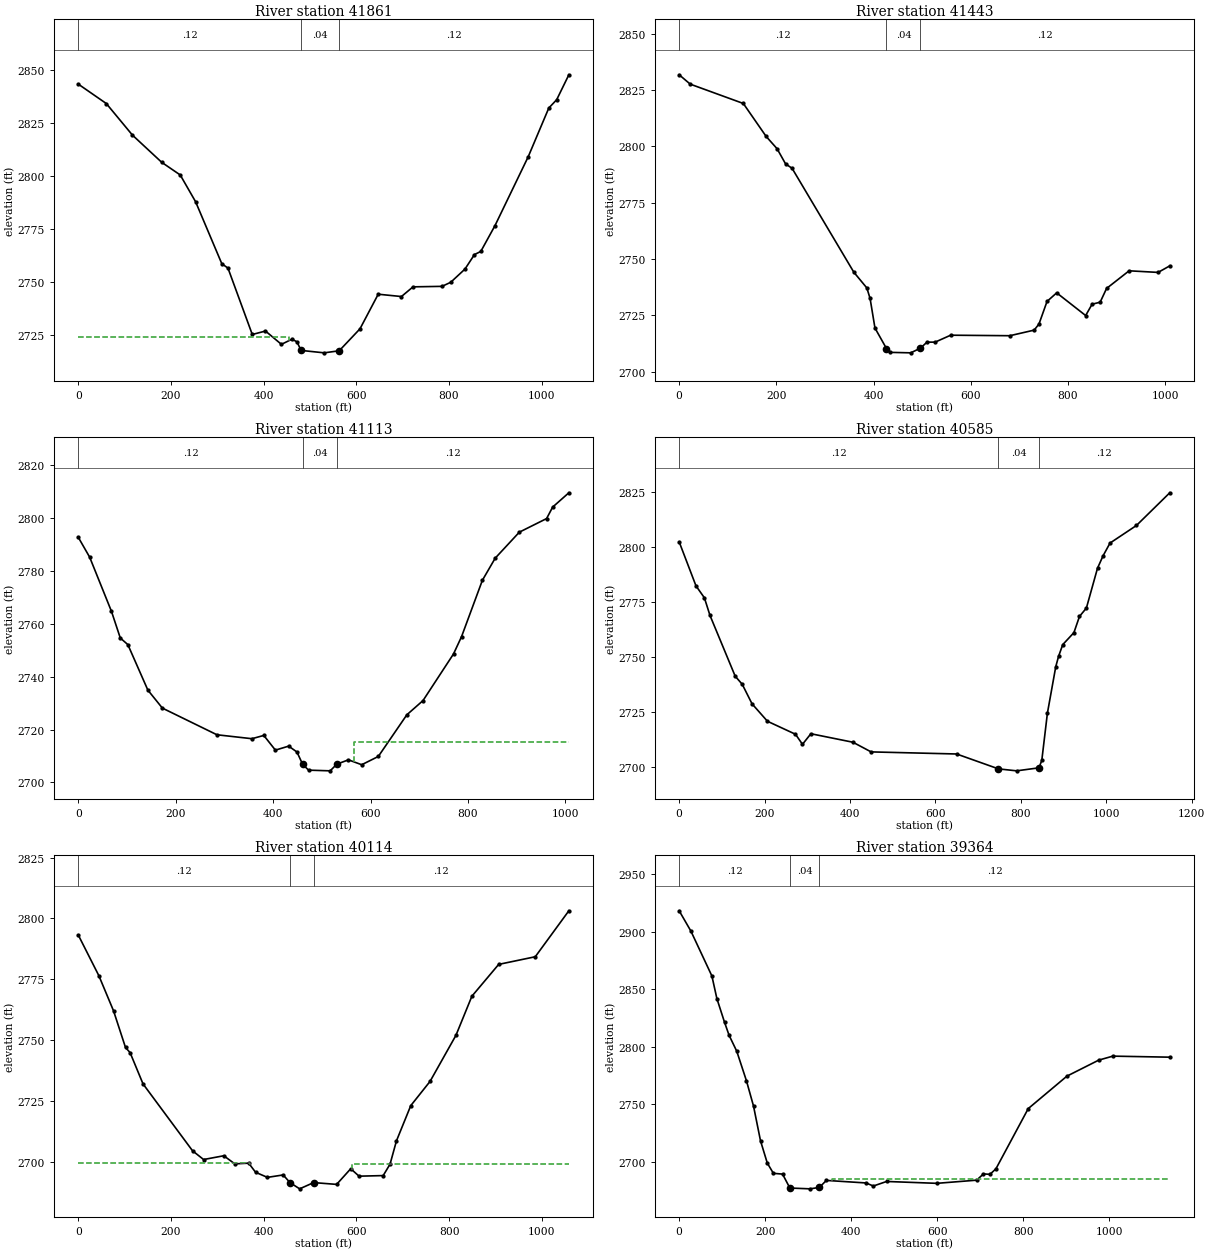
Type RM Length L Ch R = 1 ,41861   ,439.4,417.7,403.6
XS GIS Cut Line= 4
2126536.68514243423214.4278685282126919.07396211423152.749227391
     2127283.659      423311.0722127546.83047261423235.934065736
#Sta/Elev= 30
       02843.325  60.4812834.173 116.9762819.268 180.1182806.454 219.9972800.504
 253.2292787.858 309.7242758.674 323.0172756.609 375.4522725.326 403.9532726.948
  438.322720.681 461.182 2723.12 471.9132721.848 480.715 2717.82 530.5922716.676
 563.0122717.648 607.8322727.991 647.1772744.306 697.2532743.208 722.2912747.779
 784.8092748.008 803.6472749.932 834.3552756.158 854.8262762.994 868.4742764.458
 899.1812776.661 970.8322809.1071015.1872832.0411032.247 2835.981058.4962847.721
#Mann= 3 , 0 , 0
       0     .12       0 480.715     .04       0 563.012     .12       0
#XS Ineff= 2 , 0
          454.34 2723.92
Permanent Ineff=
       F       F
Bank Sta=480.715,563.012
XS Rating Curve= 0 ,0
Exp/Cntr=0.3,0.1

Type RM Length L Ch R = 1 ,41443   ,336.8,330.7,331.6
XS GIS Cut Line= 3
     2126548.923      423705.541     2127247.525      423567.025
2127542.14601096423526.256330182
#Sta/Elev= 30
       02831.801  22.7832827.642 132.013 2819.06 179.0932804.398 201.4242798.991
 218.9752792.238 232.3542790.282 359.4532744.137 386.2112737.163   392.92732.495
 402.9342719.355   426.62710.269 433.0362708.561 476.5182708.344   496.62710.432
 509.9652713.096 526.6882713.092 558.7052716.176 680.5442715.948 730.5342718.432
 740.4712721.137 757.0312731.169 776.9042734.983 836.5212724.906  849.772729.935
  866.332730.824 879.5792736.936 925.9482744.768 985.5662744.056 1009.632746.958
#Mann= 3 ,-1 , 0
       0     .12       0   426.6     .04       0   496.6     .12       0
Bank Sta=426.6,496.6
XS Rating Curve= 0 ,0
Exp/Cntr=0.3,0.1

Type RM Length L Ch R = 1 ,41113   ,492.5,527.5,633.8
XS GIS Cut Line= 4
2126674.24014159423806.9517257882126966.67723331423965.614403211
2127321.33498284423866.0613507112127626.21620613423894.060646726
#Sta/Elev= 30
       0  2792.8    23.4 2785.28    68.2 2764.75    86.3 2754.68   101.8 2752.18
   142.9 2734.96   172.7 2728.15   284.7 2718.06   356.5 2716.57   380.9 2717.81
   404.7 2712.25     432 2713.76     449 2711.53   460.7 2706.85   472.9 2704.67
   517.2 2704.41   530.8 2706.94   554.7 2708.57   581.9 2706.72     616 2709.85
   674.6 2725.62   707.8 2731.01   770.4 2748.65   786.9  2755.2   829.7 2776.54
     856  2784.9   905.5 2794.73   961.5 2799.88   973.9 2804.22  1007.2 2809.64
#Mann= 3 , 0 , 0
       0     .12       0   460.7     .04       0   530.8     .12       0
#XS Ineff= 2 , 0
                          566.38         2715.31
Permanent Ineff=
       F       F
Bank Sta=460.7,530.8
XS Rating Curve= 0 ,0
Exp/Cntr(USF)=0,0
Exp/Cntr=0.3,0.1

Type RM Length L Ch R = 1 ,40585   ,477.1,471.3,473.4
XS GIS Cut Line= 4
     2126630.226      423847.068     2127151.166      424229.492
     2127262.581      424473.401     2127428.198      424639.018
#Sta/Elev= 30
       0  2802.2    39.4 2782.19      59 2776.79    72.2 2768.74   131.2 2741.13
   147.6 2737.48   170.6 2728.59   206.7 2720.66   272.3 2714.76   288.7 2710.19
   308.4 2714.99   406.8 2711.13   449.4 2706.74   649.5 2705.79   747.6 2699.02
   790.1 2698.13   842.4  2699.5     849  2702.9   862.1 2724.32   881.7 2745.49
   888.2 2750.14     898 2755.49   924.2 2760.95   937.2 2768.31   953.4 2772.12
   979.4 2790.22   992.5 2795.89  1008.7 2801.65  1070.5 2809.64  1148.6 2824.51
#Mann= 3 , 0 , 0
       0     .12       0   747.6     .04       0   842.4     .12       0
Bank Sta=747.6,842.4
XS Rating Curve= 0 ,0
Exp/Cntr=0.3,0.1

Type RM Length L Ch R = 1 ,40114   ,766,750.3,704.2
XS GIS Cut Line= 4
2126514.53049435424122.572826797     2126705.506      424404.143
     2126892.201      424753.444     2127105.998      424994.341
#Sta/Elev= 30
       02793.201  44.3832776.526  76.0972762.088 101.9222747.045 111.7752744.953
 139.7162732.103 246.5612704.655 270.3472701.072 313.9542702.618 337.7392699.287
 367.6532699.581 382.5332695.844 408.036 2693.75 442.0542694.747 456.7572691.601
 477.6372689.045 507.783 2691.61 557.376 2690.87 587.7852697.295 605.7362694.243
 657.8172694.482 672.636 2699.18 686.4412708.729 717.3382723.195 758.9332733.138
 814.8342752.055 849.1682768.081 906.9522781.142 985.9112784.2811058.3772803.142
#Mann= 3 ,-1 , 0
       0     .12       0 456.757     .04       0 507.783     .12       0
#XS Ineff= 2 , 0
          371.35 2699.78  590.04         2699.31
Permanent Ineff=
       F       F
Bank Sta=456.757,507.783
XS Rating Curve= 0 ,0
Exp/Cntr=0.3,0.1

Type RM Length L Ch R = 1 ,39364   ,880.4,862.1,835.5
XS GIS Cut Line= 4
      2125970.77      424852.8142126336.06307643425004.124760122
2126680.03933378425109.562834774 2127027.3828361 425276.81416855
#Sta/Elev= 30
       02918.063  27.3112900.404  76.1052861.476  87.6812841.876 105.436 2821.37
  116.092810.007 133.8932796.203 156.4592770.544 172.9082748.554 189.1022718.533
 204.8692699.181 219.0732690.274  240.382689.609   257.42677.515 304.3012676.816
  325.862678.035 342.2762684.125 434.3862681.924 451.4932679.265 482.3772683.213
 599.0482681.591 691.699 2684.34 707.5352689.781 722.5822689.392 736.4262694.156
 811.6242746.434 901.5742774.599 975.4852788.4861008.2572791.9511140.6782791.048
#Mann= 3 ,-1 , 0
       0     .12       0   257.4     .04       0  325.86     .12       0
#XS Ineff= 2 , 0
                          354.47         2684.97
Permanent Ineff=
       F       F
Bank Sta=257.4,325.86
XS Rating Curve= 0 ,0
Exp/Cntr=0.3,0.1

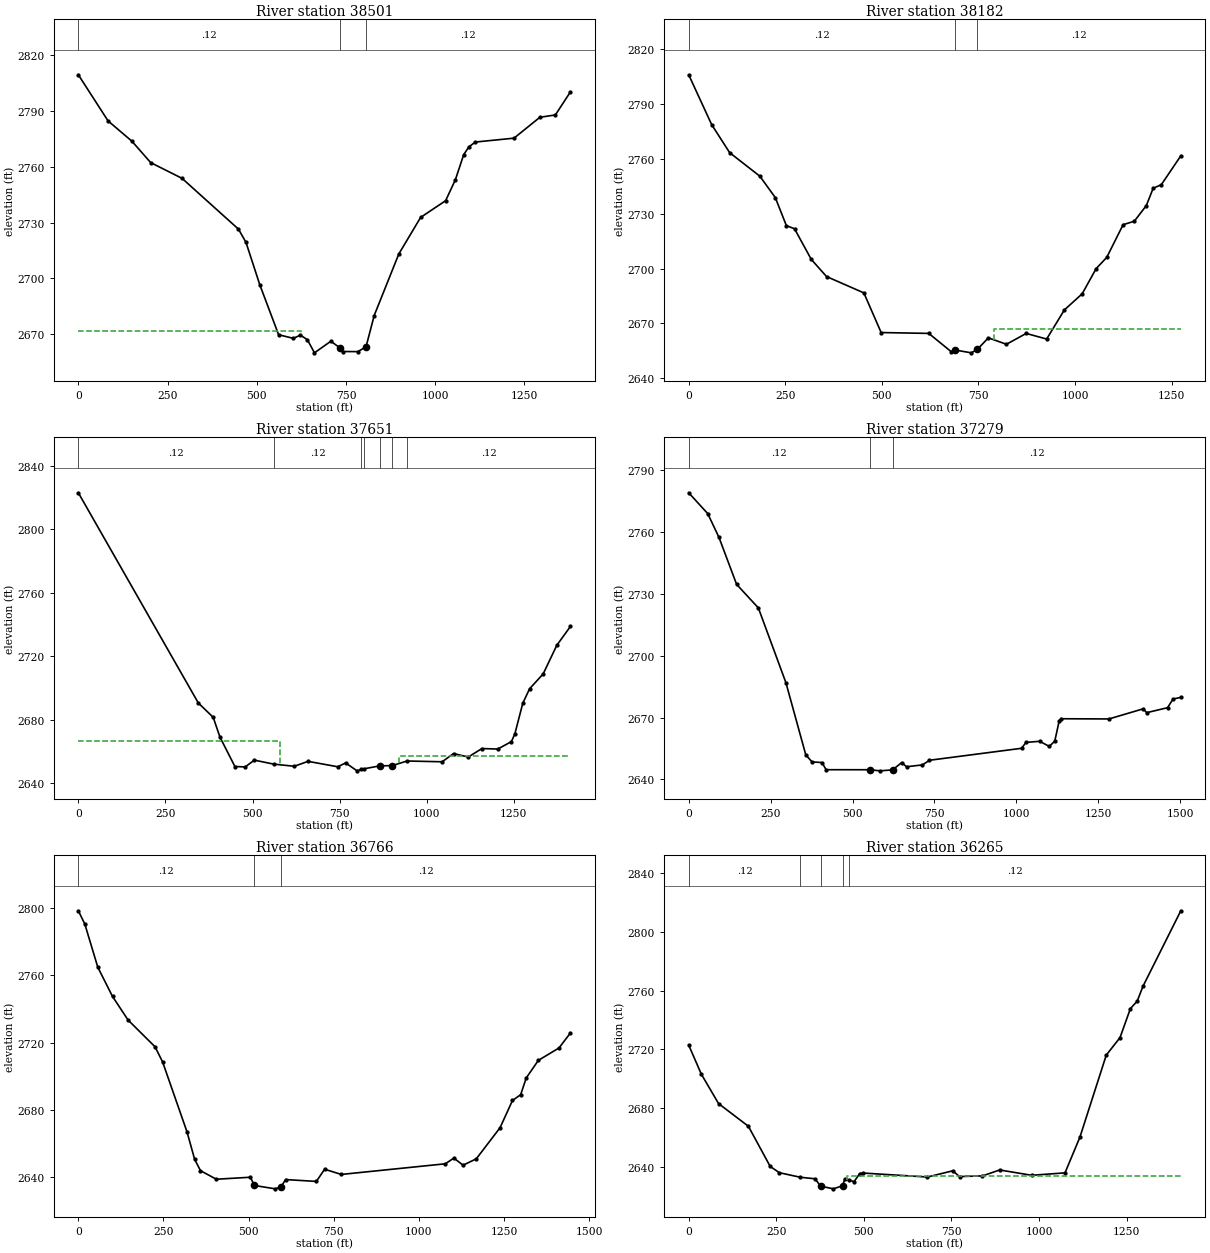
Type RM Length L Ch R = 1 ,38501   ,314.2,319.2,335.8
XS GIS Cut Line= 4
2125882.17417653425474.1130059832126434.65907377425686.080408398
     2126801.865      425674.8752127182.59016988425851.784829456
#Sta/Elev= 30
       02809.389  83.2642784.625  150.032773.726  202.742762.215  290.592753.769
 448.7212726.484 469.8052719.363 508.4592696.618 561.169 2669.78 602.5742667.827
 622.2682669.567 641.9622667.048 661.6562660.045 707.6092666.286 733.9992662.567
 740.4332660.752 783.1032660.695  806.082663.221 829.0562680.089 897.9862713.141
 959.1282732.7811029.213 2741.761056.5092753.0011079.8612766.4891094.332 2770.67
 1112.422773.2561220.9522775.3521293.3072786.5611336.7192787.8161378.9482800.208
#Mann= 3 , 0 , 0
       0     .12       0 733.999     .04       0  806.08     .12       0
#XS Ineff= 2 , 0
          623.56 2671.64
Permanent Ineff=
       F       F
Bank Sta=733.999,806.08
XS Rating Curve= 0 ,0
Exp/Cntr=0.3,0.1

Type RM Length L Ch R = 1 ,38182   ,527.6,531.5,534
XS GIS Cut Line= 4
2125875.94842217425723.0539074012126373.03657543425940.786734862
2126693.47356679426031.1663990912127063.20855682426179.060395103
#Sta/Elev= 30
       0 2805.84    59.4 2778.63     106  2763.3   184.2 2750.44   224.2 2738.74
   252.8 2723.46   273.9 2721.74   317.3    2705   356.7 2695.65   453.4 2686.71
   498.1 2665.05   621.4 2664.59   679.3 2654.63   690.2 2655.48   731.7 2653.97
   747.5 2655.96   775.7 2662.15   822.5 2658.65   873.6 2664.57   926.5 2661.51
   972.5 2677.43  1018.4 2686.18  1054.5 2699.92  1082.2 2706.15  1124.4 2723.95
  1153.5 2725.87  1184.5 2734.39  1202.2 2743.83  1223.4 2745.83  1273.8 2761.57
#Mann= 3 , 0 , 0
       0     .12       0   690.2     .04       0   747.5     .12       0
#XS Ineff= 2 , 0
                          790.05          2667.1
Permanent Ineff=
       F       F
Bank Sta=690.2,747.5
XS Rating Curve= 0 ,0
Exp/Cntr(USF)=0,0
Exp/Cntr=0.3,0.1

Type RM Length L Ch R = 1 ,37651   ,379.8,372.1,370.2
XS GIS Cut Line= 4
     2125660.615      426102.468     2126314.048      426445.746
     2126551.934      426560.173     2126904.246      426770.958
#Sta/Elev= 30
       0 2822.84   344.4 2690.59   387.1 2681.57   406.8 2668.98   449.4 2650.62
     479 2650.35   505.2 2654.63  560.84 2652.11     620 2650.76   659.4 2653.86
   744.6 2650.45   767.4 2652.87     800 2647.89  812.71 2648.78  820.47 2649.18
   865.2 2651.02   901.1 2651.19  943.81 2654.08  1044.4 2653.59    1077 2658.75
  1119.4 2656.59  1158.5 2661.91  1204.1 2661.61  1243.2 2666.29    1253 2671.12
  1275.8  2690.4  1295.3 2699.52  1334.4  2708.9  1373.5  2726.9  1412.6 2738.74
#Mann= 7 ,-1 , 0
       0     .12       0  560.84     .12       0  812.71     .12       0
  820.47     .08       0   865.2     .04       0   901.1     .12       0
  943.81     .12       0
#XS Ineff= 2 , 0
          578.61 2666.79  920.85         2657.23
Permanent Ineff=
       F       F
Bank Sta=865.2,901.1
XS Rating Curve= 0 ,0
Exp/Cntr=0.3,0.1

Type RM Length L Ch R = 1 ,37279   ,504.9,512.5,526.4
XS GIS Cut Line= 3
2125660.27907634426290.1829667622126336.88563473426810.461656067
2126967.08235699426961.904279245
#Sta/Elev= 30
       0 2779.04    58.1 2768.93    92.4 2757.39   146.2  2734.6   212.5  2723.2
   296.7 2686.89   357.3 2651.88   376.3 2648.49   406.4 2648.18   419.4  2644.7
   551.8 2644.68   584.5 2644.15   622.2 2644.62     650 2648.16   664.7 2646.13
   713.2 2647.03   734.7 2649.28  1015.8 2655.09  1029.3 2657.96  1071.2 2658.48
  1100.2 2656.01    1117 2658.53  1130.5 2668.32  1137.3 2669.42  1282.4 2669.32
  1386.8 2674.23  1397.7 2672.37  1461.2 2674.78  1478.1 2678.99  1501.7 2679.79
#Mann= 3 , 0 , 0
       0     .12       0   551.8     .04       0   622.2     .12       0
Bank Sta=551.8,622.2
XS Rating Curve= 0 ,0
Exp/Cntr(USF)=0,0
Exp/Cntr=0.3,0.1

Type RM Length L Ch R = 1 ,36766   ,504.8,500.7,506.5
XS GIS Cut Line= 2
2125320.59536623426445.1262854072126257.22852495427545.670246901
#Sta/Elev= 30
       0 2798.45      19 2790.59    57.2 2764.88   100.4 2747.54   146.1 2733.53
   225.2 2717.65   247.4 2708.68   319.2 2667.06   341.6 2650.76   358.7 2644.04
   405.3 2638.95   505.3 2640.13     517 2635.24   578.5 2633.24   595.7 2634.54
   608.7 2638.75   699.1 2637.65   723.2 2644.89   772.4  2641.8  1077.9 2648.12
  1102.8  2651.5  1129.9 2647.29  1168.7 2651.07  1238.5 2669.56    1275 2685.75
    1299 2689.17  1315.3 2699.08  1350.9 2709.57  1411.6 2716.93  1445.2 2725.87
#Mann= 3 , 0 , 0
       0     .12       0     517     .04       0   595.7     .12       0
Bank Sta=517,595.7
XS Rating Curve= 0 ,0
Exp/Cntr(USF)=0,0
Exp/Cntr=0.3,0.1

Type RM Length L Ch R = 1 ,36265   ,730.9,708.7,699.7
XS GIS Cut Line= 3
     2125118.596      426942.597     2125522.099      427442.458
      2126046.05      427996.522
#Sta/Elev= 30
       0 2722.79      36 2703.02    85.2 2682.97   170.4  2667.5   232.7 2640.12
   258.9 2635.86  318.36 2632.77   360.5 2631.73   376.9 2626.68     413 2624.87
   439.2 2626.97   445.8  2631.6  458.48 2630.86     472 2629.74   488.4  2635.3
   498.2 2635.62   681.7 2632.92   753.7 2637.15   773.3 2633.23   838.8 2633.69
   887.9 2637.73   979.5 2634.09  1074.4 2635.76    1117 2660.13  1192.2    2716
  1231.5 2727.93    1261 2747.64  1280.6 2752.78    1297 2762.89    1405 2814.32
#Mann= 5 ,-1 , 0
       0     .12       0  318.36     .12       0   376.9     .04       0
   439.2     .04       0  458.48     .12       0
#XS Ineff= 2 , 0
                          452.77         2633.36
Permanent Ineff=
       F       F
Bank Sta=376.9,439.2
XS Rating Curve= 0 ,0
Exp/Cntr=0.3,0.1

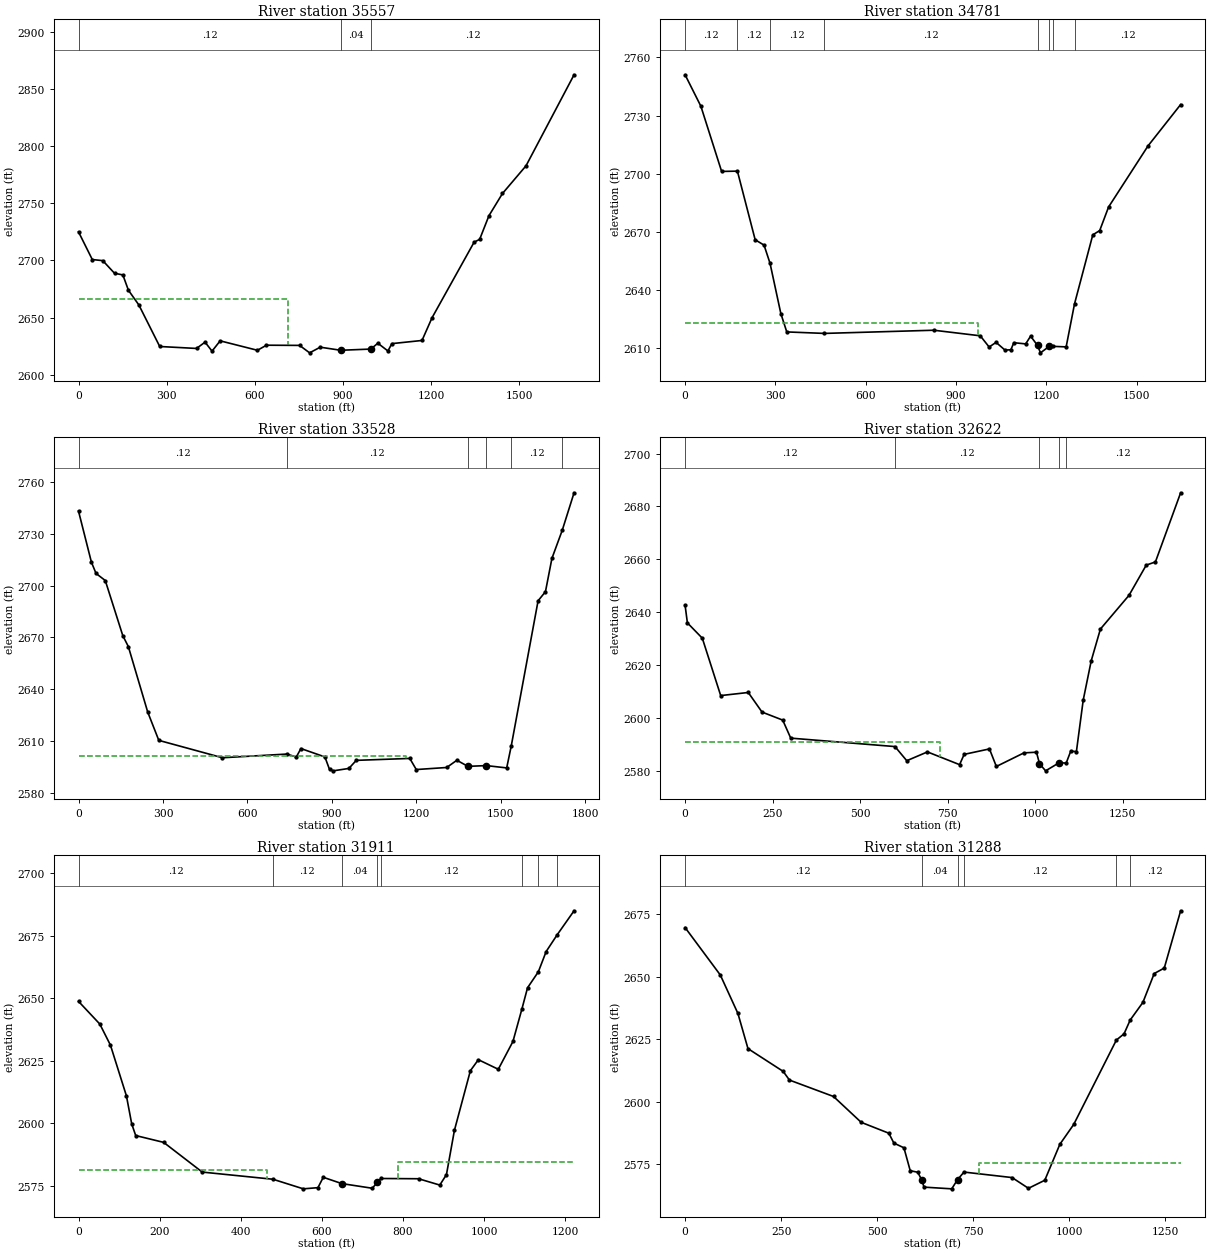
Type RM Length L Ch R = 1 ,35557   ,741.9,775.9,806.5
XS GIS Cut Line= 4
2124483.83965285427486.307174171 2124949.2075378427799.034392852
2125570.93903208 427977.735660672125961.84805543428253.233448556
#Sta/Elev= 30
       0 2724.98    46.9 2700.76    82.6 2699.79   122.5 2688.75   150.9  2687.3
   169.8 2673.89   205.2 2661.07   276.3 2624.68   401.5 2622.97   430.5 2628.49
   454.2 2620.62   481.9 2629.62   608.7 2621.37   639.4 2625.81   752.1 2625.64
   786.2 2619.13   822.3 2624.07     892 2621.38   994.4 2622.43  1018.3 2627.54
  1052.5 2620.77  1066.1  2627.2  1168.5 2629.95  1202.7 2649.85  1345.8 2715.96
  1364.6 2718.42  1396.3 2739.14  1442.3 2758.55  1522.4 2782.78  1685.8 2862.41
#Mann= 3 , 0 , 0
       0     .12       0     892     .04       0   994.4     .12       0
#XS Ineff= 2 , 0
          712.05  2666.2
Permanent Ineff=
       F       F
Bank Sta=892,994.4
XS Rating Curve= 0 ,0
Exp/Cntr(USF)=0,0
Exp/Cntr=0.3,0.1

Type RM Length L Ch R = 1 ,34781   ,1254.1,1252.7,1268.4
XS GIS Cut Line= 2
     2124266.422       427520.75     2125214.955      428866.763
#Sta/Elev= 30
       0 2751.03    52.5 2734.81   121.4 2701.18  173.89 2701.33   232.9 2665.92
   262.4 2663.17  282.29 2653.79   318.2 2627.86   337.9  2618.4  462.96 2617.63
   826.6 2619.27   980.8  2616.4  1010.3 2610.61  1033.3 2613.01  1062.8 2609.05
  1082.5 2609.18  1092.3 2612.84  1131.7 2612.22  1148.1 2616.22    1171 2611.44
  1180.9 2607.61  1210.4    2611 1221.76 2610.96  1266.2 2610.68 1294.03 2632.89
  1354.7 2668.46  1377.7 2670.68  1407.2 2682.84  1538.4 2714.38  1646.6 2735.67
#Mann= 8 ,-1 , 0
       0     .12       0  173.89     .12       0  282.29     .12       0
  462.96     .12       0    1171     .04       0  1210.4     .12       0
 1221.76     .04       0 1294.03     .12       0
#XS Ineff= 2 , 0
          972.77 2623.24
Permanent Ineff=
       F       F
Bank Sta=1171,1210.4
XS Rating Curve= 0 ,0
Exp/Cntr=0.3,0.1

Type RM Length L Ch R = 1 ,33528   ,891.4,905.8,923.3
XS GIS Cut Line= 2
     2123233.576      427861.017      2124037.57      429426.849
#Sta/Elev= 30
       0 2743.03    45.9 2713.47    62.3 2706.99    95.1  2702.9   157.3 2671.06
     177 2664.74   245.8 2626.91   285.2 2610.54   511.3  2600.5  740.15 2602.62
   773.6 2600.93     790 2605.81   875.2 2600.96   891.6 2593.72   904.7 2592.93
   960.4 2594.32   986.6 2598.99  1176.7  2600.1  1199.7 2593.68  1307.8 2594.86
  1343.9 2599.04  1383.2 2595.52  1448.8 2595.96  1520.9 2594.62 1537.01 2607.23
  1632.4  2691.2  1658.6 2696.46  1681.5 2715.67 1718.14  2731.9  1760.2 2753.61
#Mann= 6 ,-1 , 0
       0     .12       0  740.15     .12       0  1383.2     .04       0
  1448.8     .12       0 1537.01     .12       0 1718.14     .06       0
#XS Ineff= 2 , 0
         1161.81 2601.68
Permanent Ineff=
       F       F
Bank Sta=1383.2,1448.8
XS Rating Curve= 0 ,0
Exp/Cntr=0.3,0.1

Type RM Length L Ch R = 1 ,32622   ,711.5,711.1,716.6
XS GIS Cut Line= 4
     2122568.097      428345.823     2123028.813      429204.019
     2123055.914      429387.703     2123131.194      429631.612
#Sta/Elev= 30
       0 2642.66     6.6 2635.96    49.2 2630.16   101.7 2608.46   180.4 2609.63
   219.7 2602.22   278.8 2599.18   301.7 2592.36  599.34 2589.17     633 2583.82
     692 2587.15   783.8 2582.33   796.9 2586.22   869.1 2588.28   888.8 2581.64
   967.5 2586.78  1003.4 2587.04 1011.99 2582.69  1029.4 2579.99  1068.5 2583.08
 1088.17 2582.91  1101.1  2587.4  1117.4  2587.3  1136.9  2606.8  1159.7 2621.62
  1185.9 2633.62  1267.7  2646.4  1316.8 2657.81    1343 2659.01    1415 2685.17
#Mann= 5 ,-1 , 0
       0     .12       0  599.34     .12       0 1011.99     .04       0
  1068.5     .12       0 1088.17     .12       0
#XS Ineff= 2 , 0
          728.19 2590.74
Permanent Ineff=
       F       F
Bank Sta=1011.99,1068.5
XS Rating Curve= 0 ,0
Exp/Cntr=0.3,0.1

Type RM Length L Ch R = 1 ,31911   ,651,623.7,569.6
XS GIS Cut Line= 4
     2121962.843      428851.707     2122342.256      429333.501
     2122363.334      429508.152     2122658.434      429824.329
#Sta/Elev= 30
       0 2648.74    52.5 2639.66    78.7 2631.23   118.1 2610.93   131.2 2599.68
     141 2595.03   209.9  2592.3     305 2580.41  479.37 2577.54   554.2  2573.7
   590.3 2574.17   603.4 2578.32   649.1  2575.8     724 2573.94     737 2576.28
  745.31 2577.84   838.3 2577.74   890.7 2575.21   907.1  2579.4   926.8 2597.16
   966.1 2620.99   985.8 2625.39  1034.9 2621.56    1071 2632.68 1093.23 2645.75
    1107 2654.18 1133.63 2660.57  1152.9 2668.69 1180.23 2675.43  1221.7    2685
#Mann= 8 ,-1 , 0
       0     .12       0  479.37     .12       0   649.1     .04       0
     737     .12       0  745.31     .12       0 1093.23     .06       0
 1133.63     .12       0 1180.23     .06       0
#XS Ineff= 2 , 0
          465.65 2581.34  787.89          2584.6
Permanent Ineff=
       F       F
Bank Sta=649.1,737
XS Rating Curve= 0 ,0
Exp/Cntr=0.3,0.1

Type RM Length L Ch R = 1 ,31288   ,648.8,634.1,638.4
XS GIS Cut Line= 2
     2121354.861      429374.378     2122412.935      430111.957
#Sta/Elev= 30
       0 2669.68    91.7 2650.69   137.5 2635.31   163.7 2621.23   255.3 2612.12
   271.7 2608.64   386.3 2602.08   458.3 2591.74   530.3 2587.38   543.4 2583.43
   569.6 2581.54     586 2572.38   605.6 2571.76   615.4 2568.84     622  2565.8
     694 2565.12  709.15  2568.8  725.92 2571.83   851.1 2569.63   893.7 2565.33
   936.2 2568.55   975.5 2582.96  1011.5 2590.88 1122.52 2624.65  1142.5 2627.15
 1158.53 2632.68  1191.6 2639.73    1221 2651.27  1247.2 2653.47  1289.8 2676.39
#Mann= 6 ,-1 , 0
       0     .12       0   615.4     .04       0  709.15     .12       0
  725.92     .12       0 1122.52     .06       0 1158.53     .12       0
#XS Ineff= 2 , 0
                          764.35         2575.31
Permanent Ineff=
       F       F
Bank Sta=615.4,709.15
XS Rating Curve= 0 ,0
Exp/Cntr=0.3,0.1

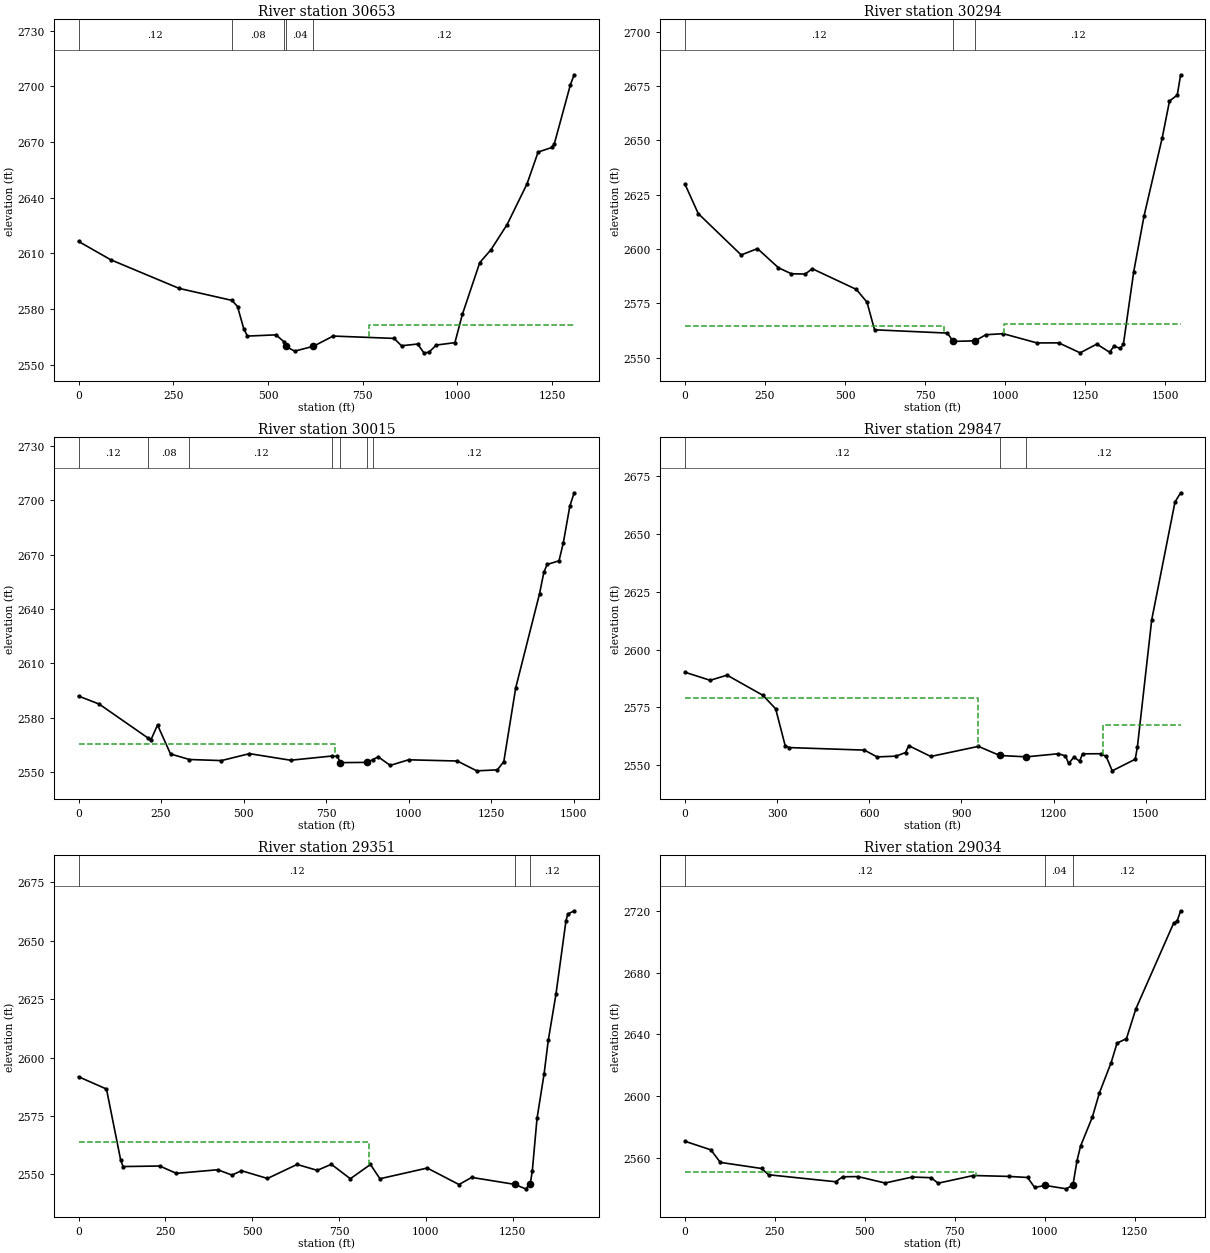
Type RM Length L Ch R = 1 ,30653   ,361.7,359.8,353.5
XS GIS Cut Line= 2
     2120981.681      429929.758     2122107.806      430594.896
#Sta/Elev= 30
       0 2616.41    85.2  2606.5   265.5 2591.09  405.19 2584.61   419.6  2581.3
     436 2569.33   445.8 2565.39   521.2 2566.05   542.4 2562.27   547.4 2559.79
   570.4 2557.28   619.5 2559.87     672  2565.4   832.6 2564.14   852.3 2560.18
   894.9 2561.11   911.3 2556.36   924.4 2556.63     944 2560.55   993.2 2561.85
  1012.9 2577.09  1058.8    2605  1088.3 2611.92  1130.9 2625.47  1183.3 2647.32
  1212.8 2664.56  1248.9 2667.04  1255.4  2668.9    1298 2700.88  1307.9 2706.21
#Mann= 5 ,-1 , 0
       0     .12       0  405.19     .08       0   542.4     .08       0
   547.4     .04       0   619.5     .12       0
#XS Ineff= 2 , 0
                          767.49         2571.26
Permanent Ineff=
       F       F
Bank Sta=547.4,619.5
XS Rating Curve= 0 ,0
Exp/Cntr=0.3,0.1

Type RM Length L Ch R = 1 ,30294   ,288.1,278.2,275.1
XS GIS Cut Line= 3
2120516.19401048430154.7401597622121437.62242267430597.025797611
2121916.76519701430814.817967764
#Sta/Elev= 30
       0 2629.84    41.4 2616.32   175.6 2597.28   226.5  2600.2     292 2591.39
   332.1 2588.64   375.7  2588.5   397.6 2590.95   535.2 2581.45   568.6 2575.57
   592.2 2562.86   819.7 2561.35   837.9 2557.52   906.9  2557.8   939.8  2560.6
   994.4 2561.07  1099.6 2556.83  1167.7 2556.85  1234.4 2552.27  1286.6 2556.29
  1326.2 2552.58  1340.6 2555.33  1359.5 2554.34  1369.5 2556.11  1401.9 2589.62
  1434.3 2615.35  1490.8 2651.11  1513.6 2668.04  1537.9 2670.83  1548.4 2680.14
#Mann= 3 , 0 , 0
       0     .12       0   837.9     .04       0   906.9     .12       0
#XS Ineff= 2 , 0
          808.69 2564.49  995.31          2565.7
Permanent Ineff=
       F       F
Bank Sta=837.9,906.9
XS Rating Curve= 0 ,0
Exp/Cntr(USF)=0,0
Exp/Cntr=0.3,0.1

Type RM Length L Ch R = 1 ,30015   ,165.9,168.4,166.7
XS GIS Cut Line= 2
     2120421.911      430544.407     2121853.165      430998.808
#Sta/Elev= 30
       0 2592.01    62.3 2587.63   209.6 2568.99   219.7 2567.96   239.4 2576.07
   278.7 2560.08  335.93 2557.01   432.8 2556.42     518 2560.24   642.6 2556.61
  767.41 2558.93   783.6 2558.97   793.4 2555.29   875.4 2555.43  891.36 2556.98
   908.2 2558.46   944.3 2553.76    1000 2556.85  1147.6 2556.18  1206.6 2550.76
  1268.9 2551.29  1288.5 2555.84  1324.6 2596.54  1396.7 2648.43  1409.8 2660.27
  1419.7 2664.62  1455.8 2666.66  1468.9 2676.64  1488.5 2696.77  1501.7 2704.18
#Mann= 7 ,-1 , 0
       0     .12       0   209.6     .08       0  335.93     .12       0
  767.41     .12       0   793.4     .04       0   875.4     .12       0
  891.36     .12       0
#XS Ineff= 2 , 0
          776.91 2565.48
Permanent Ineff=
       F       F
Bank Sta=793.4,875.4
XS Rating Curve= 0 ,0
Exp/Cntr=0.3,0.1

Type RM Length L Ch R = 1 ,29847   ,543.4,495.8,489.1
XS GIS Cut Line= 3
2120166.42512367430639.8433491522121295.61483952430993.195233024
 2121698.8968809431142.985705535
#Sta/Elev= 30
       0 2590.22      82 2586.72     137 2588.95   253.9 2580.21   295.2 2574.38
   326.1 2558.48   339.8 2557.61   583.9 2556.52   625.2 2553.58   687.1 2553.91
     718 2555.48   728.3 2558.44   800.1 2553.77   955.2 2558.14  1024.62554.188
  1111.12553.606  1215.6 2554.95  1238.6 2553.99  1248.8 2550.75  1266.1 2553.48
  1284.5 2551.72  1294.1 2554.91    1353 2554.95  1371.1 2553.78  1390.7 2547.55
  1465.6 2552.57  1472.6  2557.8  1519.3 2612.91    1595 2663.83  1613.4 2667.86
#Mann= 3 , 0 , 0
       0     .12       0  1024.6     .04       0  1111.1     .12       0
#XS Ineff= 2 , 0
          953.48 2578.93 1360.09         2567.24
Permanent Ineff=
       F       F
Bank Sta=1024.6,1111.1
XS Rating Curve= 0 ,0
Exp/Cntr(USF)=0,0
Exp/Cntr=0.3,0.1

Type RM Length L Ch R = 1 ,29351   ,326.6,317.6,317.9
XS GIS Cut Line= 3
2120216.35528118431027.7622651422121149.66514836  431288.9353967
 2121591.3550032431407.999618439
#Sta/Elev= 30
       0 2591.79    80.5 2586.52   121.4 2556.09   128.2 2553.34   233.8 2553.57
   281.5 2550.42   400.8 2551.97   441.7 2549.68     469 2551.56   543.9 2548.24
     629 2554.24   687.1 2551.72   727.8  2554.3   782.4 2548.12   840.3 2554.23
   867.5 2548.12  1003.7  2552.7  1095.1 2545.64  1131.6  2548.7  1255.2 2545.72
  1286.8  2543.8 1300.04  2545.8  1306.1 2551.45  1319.7 2573.94  1340.1 2593.07
    1352  2607.3  1374.1 2627.02  1403.1  2658.6  1408.2 2661.39  1426.6 2662.82
#Mann= 3 , 0 , 0
       0     .12       0  1255.2     .04       0 1300.04     .12       0
#XS Ineff= 2 , 0
          835.22 2564.01
Permanent Ineff=
       F       F
Bank Sta=1255.2,1300.04
XS Rating Curve= 0 ,0
Exp/Cntr(USF)=0,0
Exp/Cntr=0.3,0.1

Type RM Length L Ch R = 1 ,29034   ,336.2,344,342.2
XS GIS Cut Line= 2
      2120281.42      431418.087     2121624.867      431725.411
#Sta/Elev= 30
       0 2570.98      72 2565.45    98.2 2557.34   212.8 2553.41   232.4 2549.35
     419 2544.83   438.6 2548.05   481.2 2548.17   556.5 2544.01   631.8 2547.88
   684.2 2547.45   703.8 2543.89     802 2548.86   900.2 2548.28   952.6 2547.59
   972.2 2541.17  1001.7 2542.45  1060.6 2540.25 1078.86 2542.84  1090.1 2558.44
  1099.9 2567.86  1132.6 2586.54  1152.3  2602.2    1185 2621.84  1201.4  2634.4
  1227.6 2637.34  1253.8  2656.6  1358.5  2711.8  1368.3 2713.16  1378.2 2719.93
#Mann= 3 , 0 , 0
       0     .12       0  1001.7     .04       0 1078.86     .12       0
#XS Ineff= 2 , 0
          809.13 2551.04
Permanent Ineff=
       F       F
Bank Sta=1001.7,1078.86
XS Rating Curve= 0 ,0
Exp/Cntr=0.3,0.1

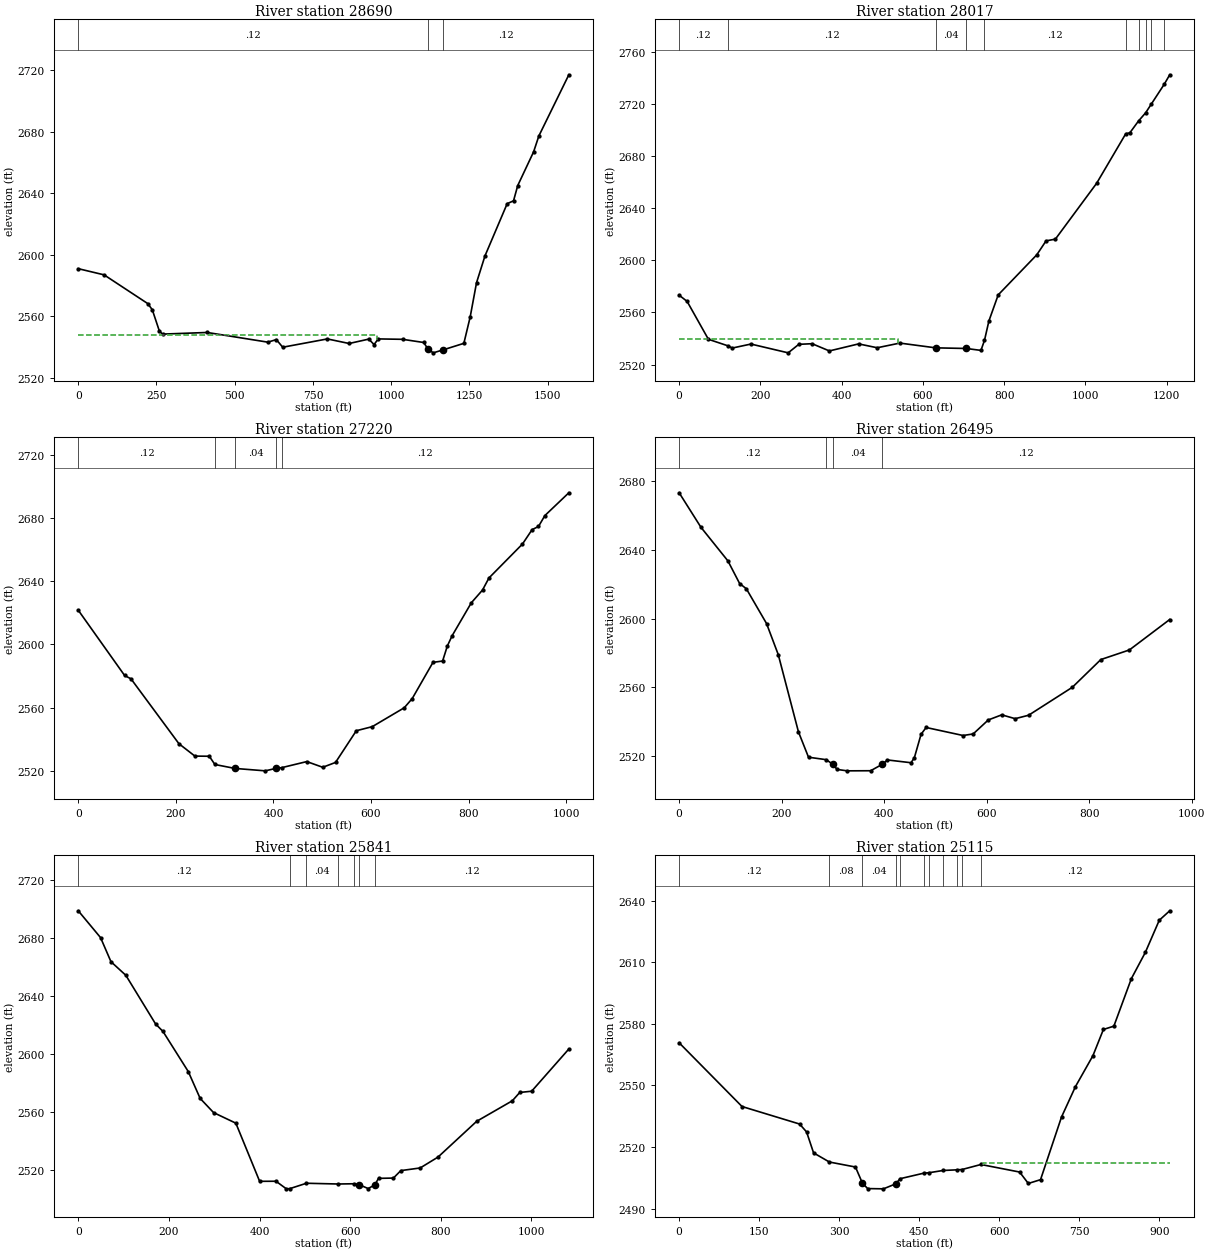
Type RM Length L Ch R = 1 ,28690   ,700.9,672.8,665.8
XS GIS Cut Line= 3
2120037.05123615431649.1295118882120894.81732167431880.324277127
2121554.89512967432041.155418163
#Sta/Elev= 30
       0 2590.85    82.5 2586.84   221.9 2568.16   236.6 2564.15   259.2 2550.27
   269.4 2548.28   412.1 2549.34   605.8 2543.04     633  2544.7   653.4 2539.74
     796 2545.14   865.6 2542.17   928.4 2545.02   945.3 2541.49   958.8 2545.15
  1036.4 2544.89    1104 2542.82  1117.7 2538.54  1134.4 2536.09  1164.7 2537.94
  1232.3 2542.27  1252.5 2559.45  1272.8 2581.74  1299.8 2599.18  1370.7 2633.15
    1391 2635.01  1404.5 2644.95  1455.2 2666.88    1472 2677.23  1567.8 2717.02
#Mann= 3 , 0 , 0
       0     .12       0  1117.7     .04       0  1164.7     .12       0
#XS Ineff= 2 , 0
          955.01 2547.83
Permanent Ineff=
       F       F
Bank Sta=1117.7,1164.7
XS Rating Curve= 0 ,0
Exp/Cntr(USF)=0,0
Exp/Cntr=0.3,0.1

Type RM Length L Ch R = 1 ,28017   ,818.3,797.1,807
XS GIS Cut Line= 2
     2120628.258       432827.39     2121756.578      432397.135
#Sta/Elev= 30
       0  2573.2    19.6 2568.45      72 2539.39  119.41 2534.44   130.9 2532.67
   176.7 2535.73   268.4 2528.99   294.5 2535.51   327.2    2536   369.8 2530.45
   441.8 2535.85   487.6 2532.89   543.2 2536.47   631.6 2532.82   706.9 2532.33
   742.9 2530.86  751.63  2538.6   762.5 2553.46   785.4 2573.45   880.3 2604.16
   903.2 2614.87   926.1  2616.2  1027.6    2659 1099.35 2697.03  1109.4 2697.73
 1130.96  2706.9 1148.34 2713.11 1162.57 2719.93 1194.18 2735.04  1207.6 2742.26
#Mann= 10 ,-1 , 0
       0     .12       0  119.41     .12       0   631.6     .04       0
   706.9     .12       0  751.63     .12       0 1099.35     .06       0
 1130.96     .12       0 1148.34     .06       0 1162.57     .12       0
 1194.18     .06       0
#XS Ineff= 2 , 0
          537.86 2539.79
Permanent Ineff=
       F       F
Bank Sta=631.6,706.9
XS Rating Curve= 0 ,0
Exp/Cntr=0.3,0.1

Type RM Length L Ch R = 1 ,27220   ,734.1,724.6,735.6
XS GIS Cut Line= 2
     2121177.051      433514.479     2122046.341      433009.589
#Sta/Elev= 30
       0 2621.62      95 2580.35   108.1 2578.23   206.3 2537.23     239 2529.41
   268.5 2529.31  279.99  2524.1   320.9 2521.62   383.1 2520.09     406  2521.7
  416.62 2522.08   468.3 2525.94     501 2522.34   527.2  2525.4   569.8 2545.44
   602.5 2548.02     668 2559.95   684.4 2565.79   726.9 2588.66   746.6 2589.49
   756.4 2599.06   766.2 2605.53   805.5 2626.32   828.4 2634.36   841.6 2641.99
   910.3 2663.46     930 2672.53   943.1 2674.54   956.2 2681.43  1005.3 2695.84
#Mann= 5 ,-1 , 0
       0     .12       0  279.99     .12       0   320.9     .04       0
     406     .12       0  416.62     .12       0
Bank Sta=320.9,406
XS Rating Curve= 0 ,0
Exp/Cntr=0.3,0.1

Type RM Length L Ch R = 1 ,26495   ,711.2,654.4,663.6
XS GIS Cut Line= 2
     2121488.766      434126.933     2122340.494      433690.094
#Sta/Elev= 30
       0 2673.31    42.6 2653.17    95.1 2633.62     118 2620.42   131.1 2617.37
   170.5  2597.1   193.4 2578.96   232.8 2533.92   252.4 2519.16  286.93 2517.73
  299.74 2515.07   308.2 2512.04   327.8 2511.22   373.7 2511.28   396.7  2515.1
   406.5 2517.56   452.4 2515.95   458.9 2518.82     472 2532.52   481.9 2536.49
     554 2531.82   573.7 2532.73   603.2 2540.89   629.4 2543.86   655.6 2541.63
   681.8 2543.62   767.1 2559.91   822.8 2576.09   878.5 2581.69   957.2 2599.44
#Mann= 4 ,-1 , 0
       0     .12       0  286.93     .12       0  299.74     .04       0
   396.7     .12       0
Bank Sta=299.74,396.7
XS Rating Curve= 0 ,0
Exp/Cntr=0.3,0.1

Type RM Length L Ch R = 1 ,25841   ,730.5,725.7,716.4
XS GIS Cut Line= 2
     2121680.016      434793.869     2122581.964      434194.984
#Sta/Elev= 30
       0  2698.8    49.2 2680.32    72.2 2663.71     105 2654.36   170.6 2620.86
     187 2615.67   242.8 2588.04     269 2569.55   298.6 2559.79   347.8 2552.49
   400.3 2512.44   436.4 2512.49   459.3 2507.26  466.89  2507.4  503.57 2511.11
  573.25 2510.59  608.71 2510.76   620.1 2510.11   639.8 2507.46  654.32 2509.96
   662.7 2514.48   695.5 2514.68   711.9 2519.82   754.6 2521.64     794 2529.14
   879.3 2553.78     958 2567.92   974.4 2573.66  1000.6  2574.5  1082.7 2603.58
#Mann= 7 ,-1 , 0
       0     .12       0  466.89     .12       0  503.57     .04       0
  573.25     .08       0  608.71     .12       0   620.1     .04       0
  654.32     .12       0
Bank Sta=620.1,654.32
XS Rating Curve= 0 ,0
Exp/Cntr=0.3,0.1

Type RM Length L Ch R = 1 ,25115   ,464.8,481.8,491.7
XS GIS Cut Line= 2
     2122070.979      435247.159     2122835.907      434737.207
#Sta/Elev= 30
       0 2570.82   117.8 2539.75   225.7 2531.21   238.8 2527.36   251.9 2517.14
  281.57 2512.68   330.4 2510.25   343.5 2502.34   353.3 2499.74   382.8 2499.61
   405.7 2502.02  414.14 2504.56  459.06 2507.29  467.39 2507.43  494.56 2508.56
  520.64 2508.88  530.06 2509.03  565.56 2511.48     638  2507.8   654.3 2502.23
   677.2 2504.08   716.5 2534.61   742.7 2549.49   775.4 2564.54     795 2577.32
   814.6 2578.93   847.4  2602.1   873.5 2614.85   899.7 2630.57   919.3 2635.19
#Mann= 11 ,-1 , 0
       0     .12       0  281.57     .08       0   343.5     .04       0
   405.7     .08       0  414.14     .12       0  459.06     .06       0
  467.39     .12       0  494.56     .06       0  520.64     .12       0
  530.06     .06       0  565.56     .12       0
#XS Ineff= 2 , 0
                          570.21         2512.16
Permanent Ineff=
       F       F
Bank Sta=343.5,405.7
XS Rating Curve= 0 ,0
Exp/Cntr=0.3,0.1