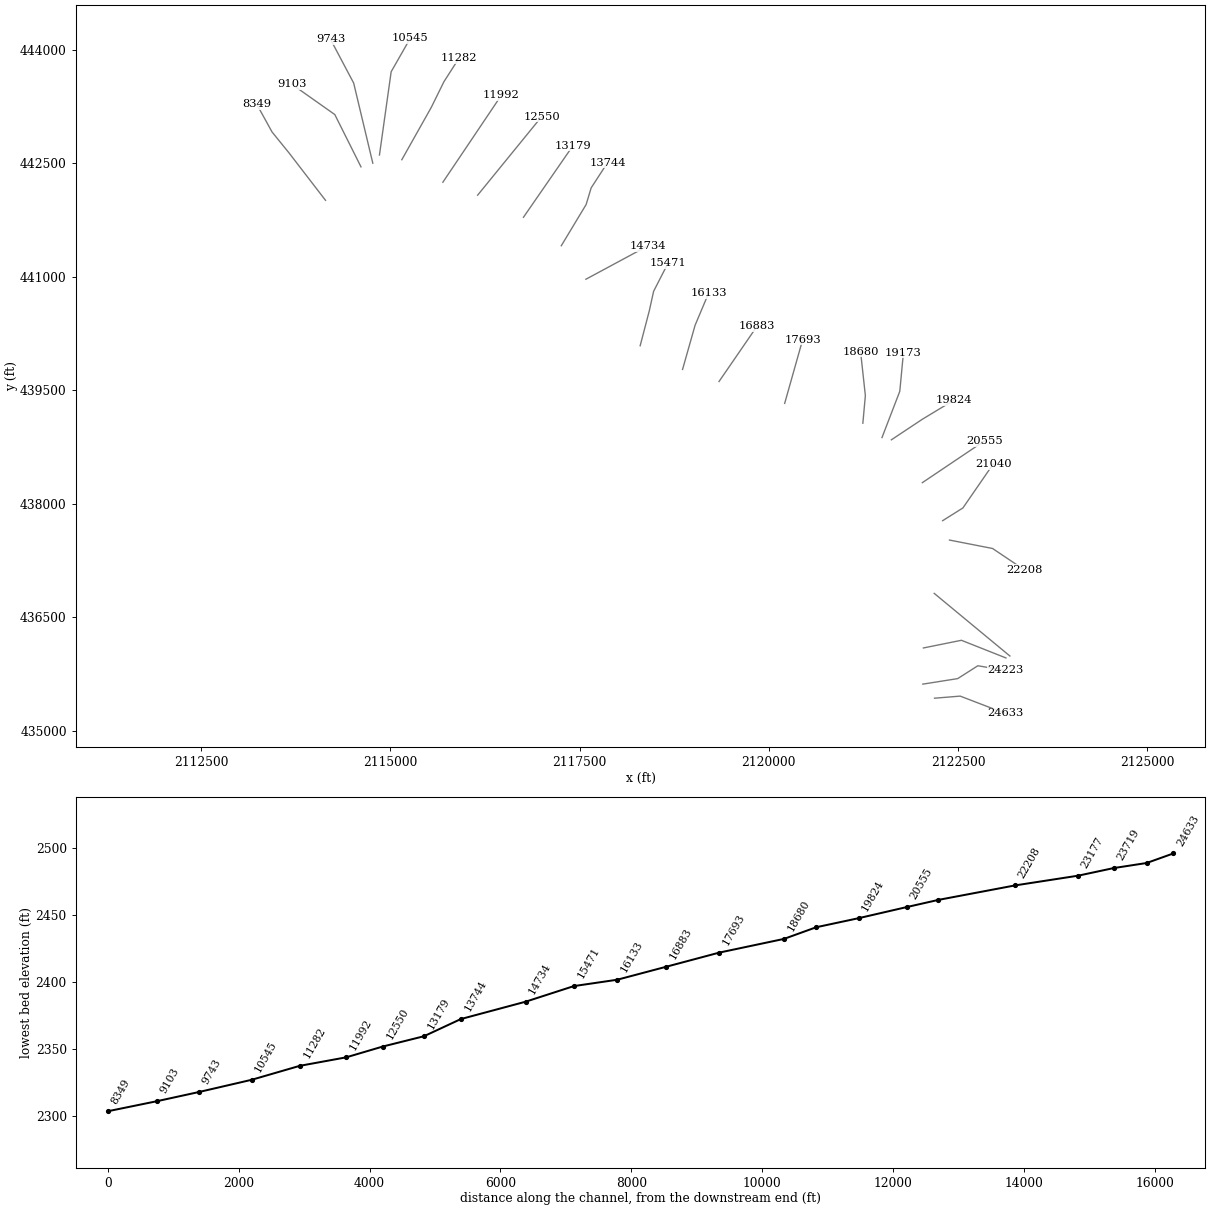
HEC-RAS study SFKCHERRYRV.prj: SFKCHERRYRV

--- SFKCHERRYRV.g01 (geometry) --- (continued)

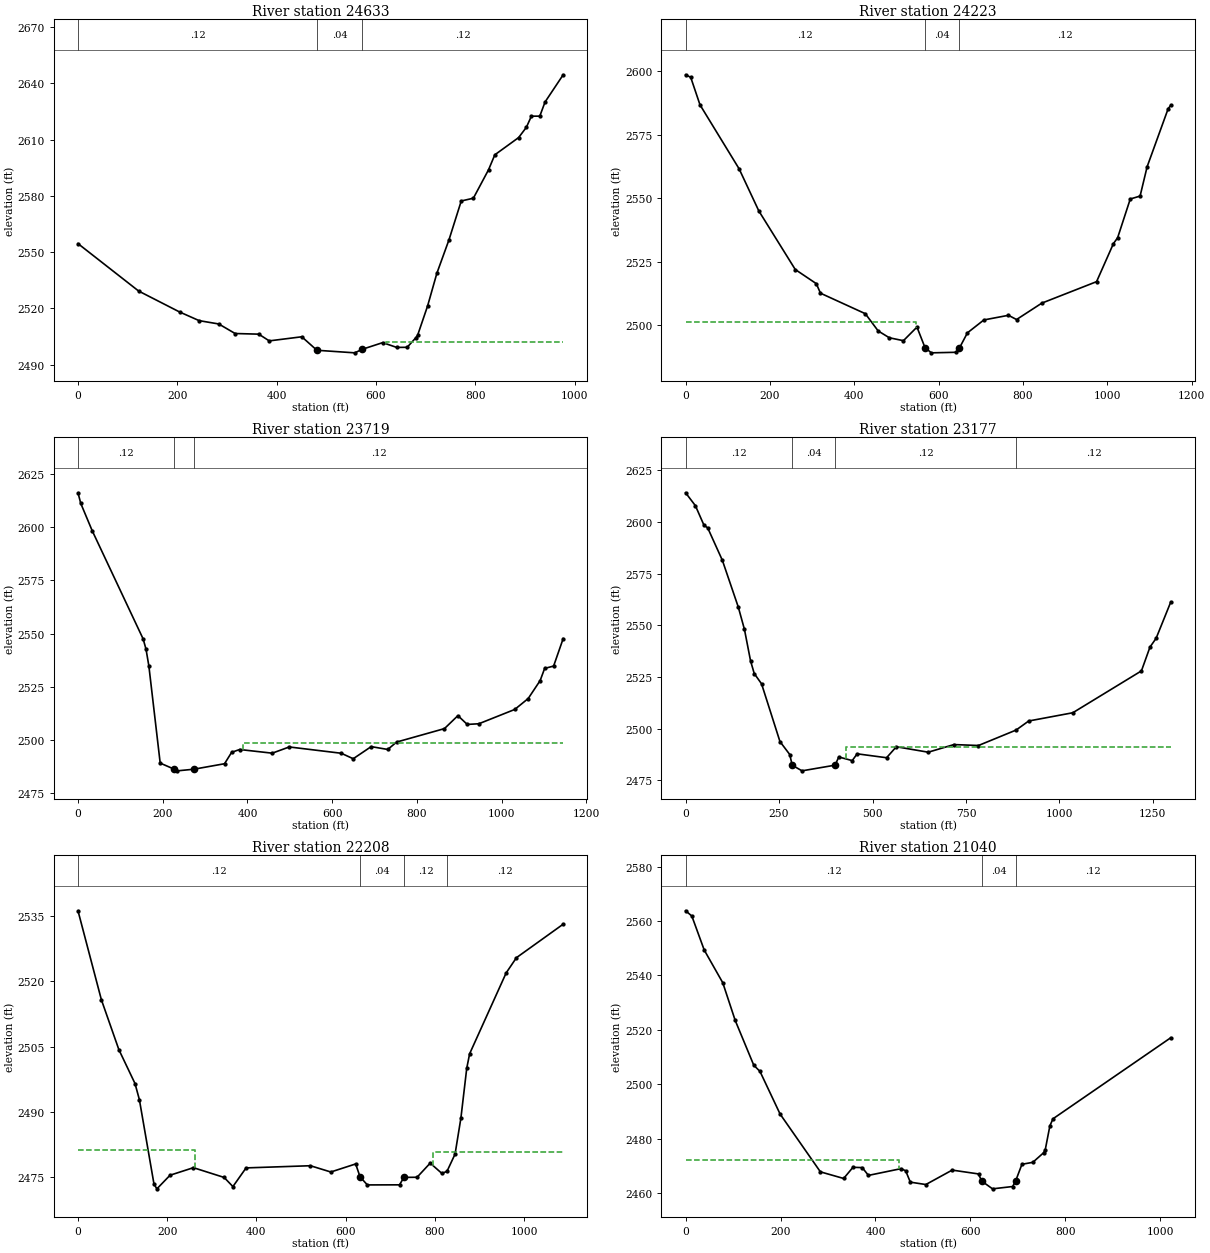
Type RM Length L Ch R = 1 ,24633   ,359.5,410.2,453.1
XS GIS Cut Line= 3
2122189.96633281435429.9843507582122528.72324757435457.637976452
    2123123.2762435229.495564472
#Sta/Elev= 30
       0 2554.53   122.1 2529.22   204.4 2518.07   243.9 2513.43   283.4 2511.65
   316.3 2506.56   363.9 2506.22     385 2502.63   450.5 2504.82     481 2497.62
   557.1 2496.25   572.4 2498.16   613.4  2501.7   641.5 2499.15   662.6  2499.2
   680.1 2504.29   683.7 2505.64   703.8 2521.29   722.4 2538.69   746.9 2556.62
   771.5 2577.28   795.9 2578.76   826.4 2593.91   839.1 2601.92     887 2611.11
   902.6 2616.59   912.7 2622.53   929.6 2622.55   940.2 2630.09   976.7 2644.62
#Mann= 3 , 0 , 0
       0     .12       0     481     .04       0   572.4     .12       0
#XS Ineff= 2 , 0
                          619.75         2502.03
Permanent Ineff=
       F       F
Bank Sta=481,572.4
XS Rating Curve= 0 ,0
Exp/Cntr(USF)=0,0
Exp/Cntr=0.3,0.1

Type RM Length L Ch R = 1 ,24223   ,536.6,503.6,499.9
XS GIS Cut Line= 4
2122035.15903099435616.132990824     2122495.939      435689.118
     2122762.247      435859.102     2123124.879      435796.774
#Sta/Elev= 30
       02598.621  12.0982597.621  34.1052586.774 126.7992561.582 173.6182544.968
 259.9832521.903 309.8092516.337 319.7752512.573  426.072504.494 456.5652497.701
 483.023 2495.01 516.4282493.861 548.5522499.222 567.5582491.147 582.5952489.073
 641.5652489.291 648.7632490.846 668.2242496.956 707.1462502.032  765.532503.864
 784.6242502.189 844.5452508.656 974.3742517.1141014.3212532.0991024.3082534.405
1054.2682549.6831077.5712550.8361094.2422562.381 1144.152585.2711150.4082586.618
#Mann= 3 ,-1 , 0
       0     .12       0 567.558     .04       0 648.763     .12       0
#XS Ineff= 2 , 0
          546.14 2501.08
Permanent Ineff=
       F       F
Bank Sta=567.558,648.763
XS Rating Curve= 0 ,0
Exp/Cntr=0.3,0.1

Type RM Length L Ch R = 1 ,23719   ,616.7,542.2,531.7
XS GIS Cut Line= 3
2122042.70630862436094.1614343012122544.81555434436195.597645558
2123133.14557963435962.294359668
#Sta/Elev= 30
       0 2616.33   6.5842611.301   33.362598.532  153.752547.462 160.5512542.634
 167.2452534.771 194.0222488.939 227.4932486.039 234.5032485.292   273.52486.056
 345.8862488.644 362.593    2494  381.462495.344 458.4442493.617 498.6092496.546
 621.3942493.575  649.632490.993 691.9822496.707 731.0932495.367 751.9822498.852
 864.9222505.192 896.6862511.303 918.7212507.164 946.0972507.4781030.8022514.219
1062.5672519.3631090.8022527.834 1101.392533.5611122.5662534.6671145.1532547.625
#Mann= 3 ,-1 , 0
       0     .12       0 227.493     .04       0   273.5     .12       0
#XS Ineff= 2 , 0
                          389.71         2498.62
Permanent Ineff=
       F       F
Bank Sta=227.493,273.5
XS Rating Curve= 0 ,0
Exp/Cntr(USF)=0,0
Exp/Cntr=0.3,0.1

Type RM Length L Ch R = 1 ,23177   ,961.9,969.6,983.2
XS GIS Cut Line= 2
     2122185.588      436815.896     2123185.311      435987.812
#Sta/Elev= 30
       0 2614.19    26.2 2607.93    49.2 2598.46      59 2597.24    98.3 2581.52
     141 2558.84   157.4 2548.08   173.7 2532.88   183.6 2526.71   203.2 2521.72
   252.4 2493.79   278.6 2487.52   285.2 2482.34   311.4 2479.62   399.9 2482.37
   409.8 2486.33   445.8 2484.57   458.9 2487.86   537.6 2485.96   563.8 2491.28
   649.1 2488.64   717.9 2492.33   783.5 2491.88   884.1 2499.35   917.9 2503.74
  1035.9 2507.73  1219.5 2527.99  1242.4 2539.53  1258.8 2543.76  1298.1 2561.38
#Mann= 4 ,-1 , 0
       0     .12       0   285.2     .04       0   399.9     .12       0
   884.1     .12       0
#XS Ineff= 2 , 0
                          428.24         2490.92
Permanent Ineff=
       F       F
Bank Sta=285.2,399.9
XS Rating Curve= 0 ,0
Exp/Cntr=0.3,0.1

Type RM Length L Ch R = 1 ,22208   ,1090.3,1167.1,1231.3
XS GIS Cut Line= 3
     2122387.339       437520.52     2122956.459      437409.105
     2123378.029      437126.051
#Sta/Elev= 30
       0 2536.19    52.4 2515.76    91.7 2504.27   127.8  2496.5   137.6 2492.81
   170.4 2473.38   176.9  2472.3   206.4 2475.43   258.8 2477.16   327.6 2474.92
   347.3 2472.82   376.8 2477.11     521 2477.61   566.8 2476.17   622.5 2478.02
   632.3 2475.06   648.7  2473.2   720.8 2473.22   730.6 2474.93   760.1 2474.96
   789.6 2478.21   815.8 2475.84  827.28 2476.33   845.3 2480.28   858.4 2488.55
   871.5 2500.01     878 2503.34   959.9 2521.92   982.9 2525.41  1087.7 2533.11
#Mann= 4 ,-1 , 0
       0     .12       0   632.3     .04       0   730.6     .12       0
  827.28     .12       0
#XS Ineff= 2 , 0
          262.78 2481.24  796.96         2480.79
Permanent Ineff=
       F       F
Bank Sta=632.3,730.6
XS Rating Curve= 0 ,0
Exp/Cntr=0.3,0.1

Type RM Length L Ch R = 1 ,21040   ,493,485,462
XS GIS Cut Line= 3
     2122297.003      437776.473     2122565.001      437945.101
     2122965.493      438526.266
#Sta/Elev= 30
       0 2563.74    13.1 2561.81    39.2 2549.31    78.3 2537.28   104.5 2523.43
   143.6 2506.97   156.7 2504.69   199.1 2489.01     284 2467.77     333 2465.33
   352.6 2469.43   372.2 2469.33   385.2 2466.46   453.9 2468.94   463.7 2468.16
   473.5 2463.98   506.2  2463.1   561.7 2468.41   617.2    2467   623.8 2464.39
   646.7 2461.52   689.1 2462.37   695.7 2464.55   708.7 2470.55   731.6 2471.26
   754.5 2474.81   757.8 2475.87   767.6 2484.69   774.1 2487.27  1022.4 2517.08
#Mann= 3 , 0 , 0
       0     .12       0   623.8     .04       0   695.7     .12       0
#XS Ineff= 2 , 0
          450.09  2472.2
Permanent Ineff=
       F       F
Bank Sta=623.8,695.7
XS Rating Curve= 0 ,0
Exp/Cntr=0.3,0.1

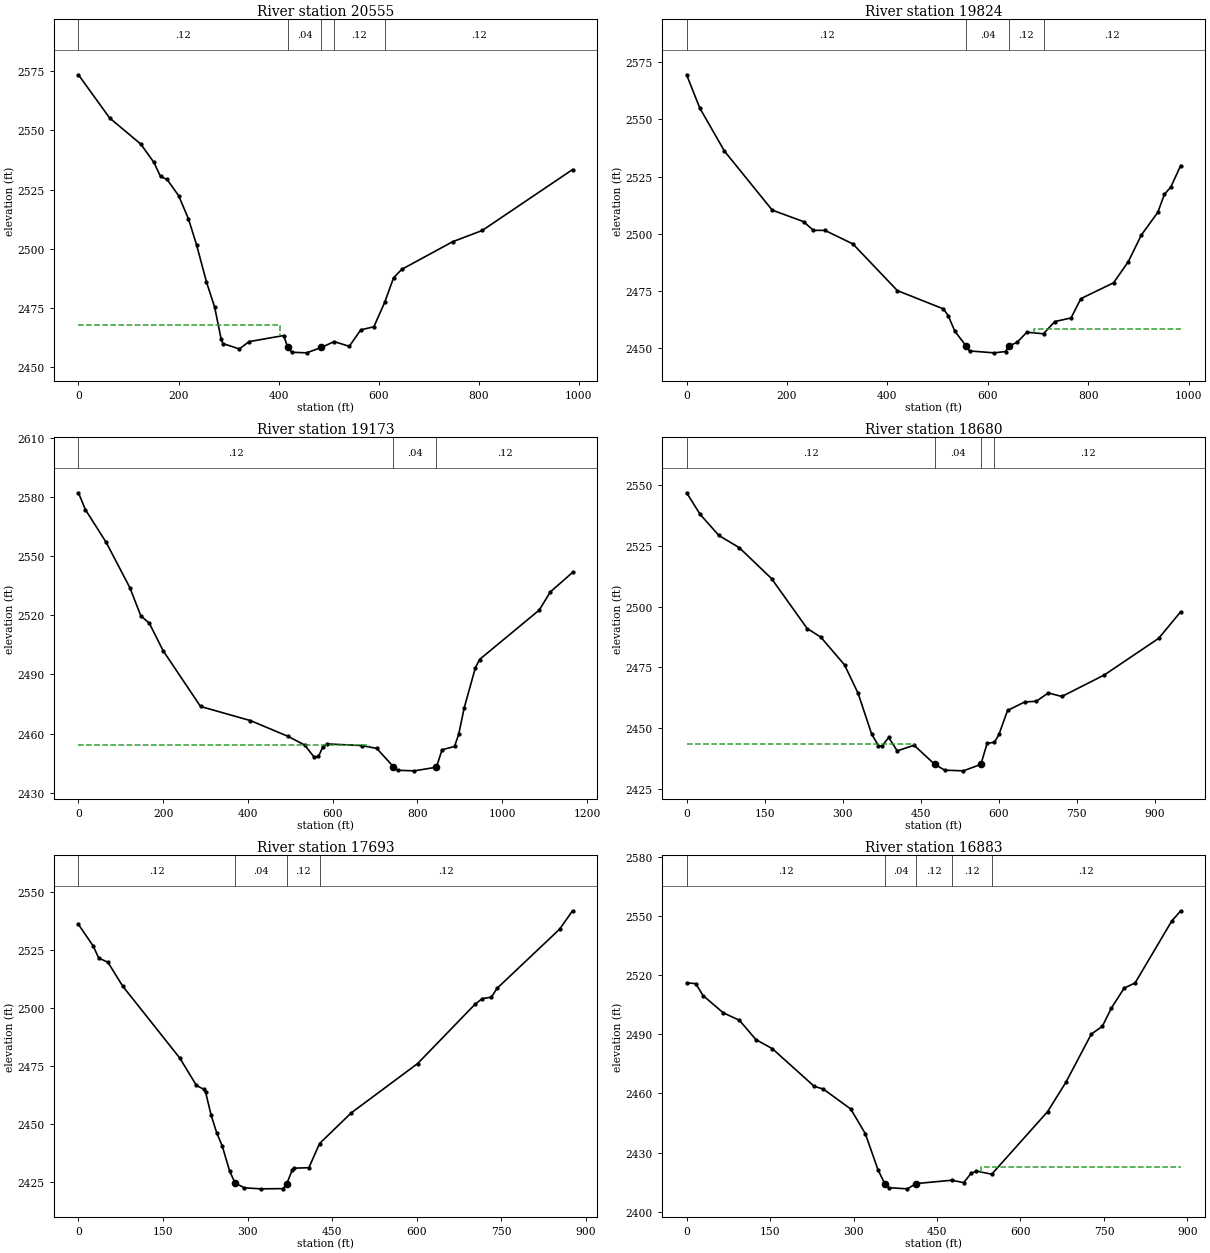
Type RM Length L Ch R = 1 ,20555   ,746.3,731.8,737.9
XS GIS Cut Line= 2
     2122029.005      438279.346     2122848.055      438830.399
#Sta/Elev= 30
       0 2573.49    62.3 2555.26   124.6 2544.23   150.9 2536.48     164 2530.57
   177.1 2529.31   200.1  2522.5   219.7 2512.75   236.1 2501.68   255.8 2486.04
   272.2  2475.4   285.3  2461.8   288.6 2460.07   321.4 2457.79   341.1 2460.87
     410 2463.44  418.26 2458.44   426.4 2456.39   455.9 2456.14   485.4 2458.42
  510.97 2460.89   541.1 2458.88   564.1 2465.85   590.3 2467.14  611.81 2477.42
   629.7 2487.84   646.1 2491.39   747.8 2503.05   806.8 2507.78   987.2 2533.48
#Mann= 5 ,-1 , 0
       0     .12       0  418.26     .04       0   485.4     .12       0
  510.97     .12       0  611.81     .12       0
#XS Ineff= 2 , 0
          401.94 2467.75
Permanent Ineff=
       F       F
Bank Sta=418.26,485.4
XS Rating Curve= 0 ,0
Exp/Cntr=0.3,0.1

Type RM Length L Ch R = 1 ,19824   ,617.5,650.6,686.5
XS GIS Cut Line= 3
      2121619.48      438845.455     2122032.016      439119.475
     2122450.575      439372.417
#Sta/Elev= 30
       0 2569.54    26.2 2555.01    75.4 2536.14   170.6 2510.31   232.9  2505.3
   252.5 2501.48   275.5 2501.46   331.3 2495.52   419.8 2475.12   511.6  2467.1
   521.3 2464.08   534.4 2457.31   557.2 2450.78   563.7 2448.71   612.6 2447.88
   635.4 2448.46     642 2450.87   658.3 2452.46   677.8  2456.9  710.99 2456.22
   733.3 2461.56   765.9 2463.15   785.4  2471.6   850.6 2478.52     880 2487.82
     906 2499.46   938.7 2509.37   951.7 2517.17   964.7  2520.5   984.3 2529.82
#Mann= 4 ,-1 , 0
       0     .12       0   557.2     .04       0     642     .12       0
  710.99     .12       0
#XS Ineff= 2 , 0
                          692.39         2458.22
Permanent Ineff=
       F       F
Bank Sta=557.2,642
XS Rating Curve= 0 ,0
Exp/Cntr=0.3,0.1

Type RM Length L Ch R = 1 ,19173   ,486.9,492.9,502.2
XS GIS Cut Line= 3
      2121496.02      438875.567     2121730.895      439486.843
     2121779.074      439995.739
#Sta/Elev= 30
       0 2582.01    16.4 2573.49    65.5 2556.86   121.2 2533.99   147.3  2519.6
     167 2515.99   199.7 2502.04   288.1 2473.71     406 2466.54   494.4 2458.58
   533.7 2454.18   556.6 2447.94   566.4 2448.35   576.3 2452.97   586.1 2454.72
     668  2453.9     704 2452.45   743.3 2443.17   753.2 2441.36   792.5 2441.08
   844.9 2442.92     858 2451.74   887.5 2453.45   897.3 2459.58   910.4 2473.04
   936.6 2493.22   946.5 2497.51  1087.4 2522.55  1113.6 2531.76    1166 2541.63
#Mann= 3 , 0 , 0
       0     .12       0   743.3     .04       0   844.9     .12       0
#XS Ineff= 2 , 0
          684.78 2453.97
Permanent Ineff=
       F       F
Bank Sta=743.3,844.9
XS Rating Curve= 0 ,0
Exp/Cntr=0.3,0.1

Type RM Length L Ch R = 1 ,18680   ,1010,987.1,977.1
XS GIS Cut Line= 3
     2121243.078      439065.273     2121276.201       439429.63
     2121212.966      440010.795
#Sta/Elev= 30
       0 2546.99    26.1 2538.08    62.1 2529.39   101.3 2524.36   163.3 2511.64
   231.9 2491.04   258.1  2487.5   303.8 2476.03   329.9  2464.3   356.1 2447.41
   369.1 2442.76   375.7 2442.52   388.7 2446.14     405 2440.62   437.7  2442.9
   476.9  2435.1   496.5 2432.64   532.4 2432.37  566.03 2435.04   578.1 2443.75
   592.2 2444.11     601 2447.48   617.3 2457.25     650 2460.74   672.8 2461.06
   695.7 2464.48   721.8 2463.02   803.5  2471.9     908 2486.98   950.4 2497.96
#Mann= 4 ,-1 , 0
       0     .12       0   476.9     .04       0  566.03     .12       0
   592.2     .12       0
#XS Ineff= 2 , 0
          438.04 2443.25
Permanent Ineff=
       F       F
Bank Sta=476.9,566.03
XS Rating Curve= 0 ,0
Exp/Cntr=0.3,0.1

Type RM Length L Ch R = 1 ,17693   ,824.6,810.3,799.9
XS GIS Cut Line= 2
     2120210.231      439327.249     2120448.117      440170.389
#Sta/Elev= 30
       0 2536.05    26.2 2526.74      36 2521.55    52.3 2519.73    78.4 2509.49
   179.8 2478.45   209.2 2466.69   222.3 2465.01   225.6 2463.67   235.4 2453.78
   245.2 2446.28     255 2440.62     268 2429.87   277.8 2424.64   294.2  2422.6
   323.6 2422.16   362.8 2422.25   369.4 2424.39   379.2  2430.3   382.5 2431.06
   408.6 2431.26  427.58 2441.68   483.8 2454.88   601.5 2476.13   702.8 2501.55
   715.9 2504.07   732.2  2504.7     742 2508.44   853.2    2534   876.1 2541.91
#Mann= 4 ,-1 , 0
       0     .12       0   277.8     .04       0   369.4     .12       0
  427.58     .12       0
Bank Sta=277.8,369.4
XS Rating Curve= 0 ,0
Exp/Cntr=0.3,0.1

Type RM Length L Ch R = 1 ,16883   ,744.1,750.3,764.9
XS GIS Cut Line= 2
     2119343.001      439616.326     2119845.874      440348.051
#Sta/Elev= 30
       0 2516.04    16.4 2515.64    29.5 2509.62    65.5 2500.91      95 2497.04
   124.5 2487.26     154 2482.68   229.3 2463.58   245.7 2462.18   294.9 2452.08
   321.1  2439.6     344 2421.19  356.22 2414.15   363.7 2412.18   396.4  2411.6
   412.8 2414.28  476.56 2415.96     498 2414.74   511.1 2419.43   520.9 2420.61
  548.24 2419.01   648.7 2450.74   681.5 2465.59   727.3 2490.08     747 2493.96
   763.4 2503.28   786.3 2513.38     806 2516.02   871.5 2547.25   887.9 2552.58
#Mann= 5 ,-1 , 0
       0     .12       0  356.22     .04       0   412.8     .12       0
  476.56     .12       0  548.24     .12       0
#XS Ineff= 2 , 0
                          528.26         2422.74
Permanent Ineff=
       F       F
Bank Sta=356.22,412.8
XS Rating Curve= 0 ,0
Exp/Cntr=0.3,0.1

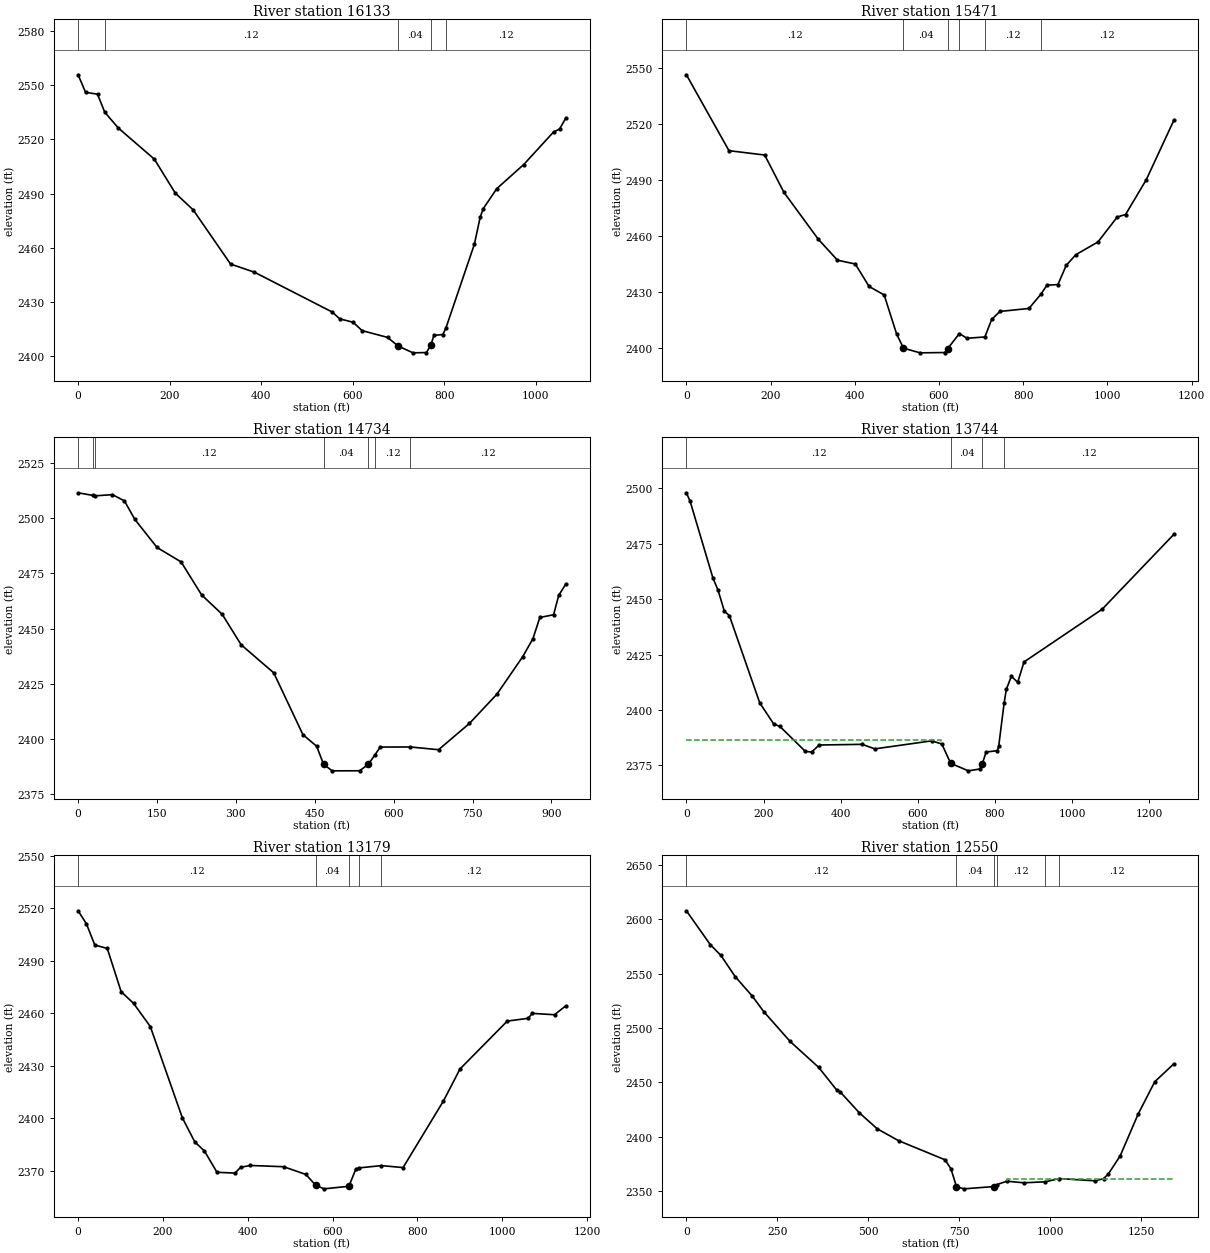
Type RM Length L Ch R = 1 ,16133   ,663.4,662,674.9
XS GIS Cut Line= 3
     2118861.207       439775.92     2119026.824      440360.096
     2119204.486      440781.666
#Sta/Elev= 30
       0 2555.69    16.3 2545.99    42.4 2544.96   58.15    2535    88.1 2526.18
   166.5 2509.03   212.2 2490.26   251.4 2480.94     333 2450.99   385.2 2446.48
     555 2424.46   571.3  2420.7   600.7 2418.79   620.3 2414.16   675.8 2410.43
   698.7  2405.7   731.4 2401.88   760.8 2402.04   770.6 2406.25   777.1 2411.54
   796.7 2412.01  803.23 2415.52   865.4 2461.86   878.4 2477.12     885 2481.69
   914.4  2492.7   973.2 2506.02  1038.5 2524.06  1051.6 2525.69  1064.7 2531.52
#Mann= 5 ,-1 , 0
       0     .08       0   58.15     .12       0   698.7     .04       0
   770.6     .12       0  803.23     .12       0
Bank Sta=698.7,770.6
XS Rating Curve= 0 ,0
Exp/Cntr=0.3,0.1

Type RM Length L Ch R = 1 ,15471   ,785,736.5,677.8
XS GIS Cut Line= 4
     2118301.121      440089.086      2118421.57      440549.802
     2118478.783      440808.767     2118668.489      441179.146
#Sta/Elev= 30
       0 2546.35   101.1 2505.63   185.9 2503.28   231.6 2483.26   313.1 2458.14
   358.8 2446.85   401.2  2444.8   433.8 2432.76   469.7 2428.19   499.1 2407.33
   515.5 2399.66   554.8 2397.14   613.7  2397.3   620.3 2399.39  648.41 2407.49
   666.1 2404.95  708.91 2405.66     725  2415.1   744.7 2419.36   813.5 2420.96
  841.96 2428.61   856.1 2433.42   882.3 2433.78     902 2444.08   924.9 2449.82
   977.3 2456.63  1023.2 2470.03  1042.9 2471.37    1092    2490  1157.6 2521.94
#Mann= 6 ,-1 , 0
       0     .12       0   515.5     .04       0   620.3     .12       0
  648.41     .12       0  708.91     .12       0  841.96     .12       0
Bank Sta=515.5,620.3
XS Rating Curve= 0 ,0
Exp/Cntr=0.3,0.1

Type RM Length L Ch R = 1 ,14734   ,985.6,990.3,1013.8
XS GIS Cut Line= 3
     2117584.452      440968.361     2117897.618      441136.989
     2118400.491      441407.998
#Sta/Elev= 30
       0 2511.58   27.88 2510.39   32.54  2510.2    65.3 2510.73    88.1  2507.9
   107.7 2499.57   150.1 2486.77   195.8 2480.24   234.9 2465.26   274.1 2456.44
     310 2442.66     372 2429.93   427.5  2401.9   453.6 2396.63   466.7 2388.49
     483 2385.49   535.2 2385.52   551.5 2388.38  564.66 2392.78   574.4 2396.28
  631.76 2396.31   685.4 2395.07   744.1 2406.98   796.4 2420.27   845.3 2437.21
   864.9 2445.46     878 2455.05   904.1 2456.26   913.9  2465.1   926.9 2470.01
#Mann= 7 ,-1 , 0
       0     .12       0   27.88     .06       0   32.54     .12       0
   466.7     .04       0   551.5     .12       0  564.66     .12       0
  631.76     .12       0
Bank Sta=466.7,551.5
XS Rating Curve= 0 ,0
Exp/Cntr=0.3,0.1

Type RM Length L Ch R = 1 ,13744   ,578.6,564.8,555.9
XS GIS Cut Line= 4
     2117259.241       441411.01     2117587.463      441956.039
      2117653.71      442175.858     2117870.517      442510.103
#Sta/Elev= 30
       0 2497.99     9.8 2494.08    68.9 2459.48      82 2454.09    98.4 2444.59
   111.5 2442.55   190.2 2403.19   226.3  2393.7   242.7 2392.53   308.3 2381.32
   324.7 2380.98   344.4 2384.18   455.8 2384.48   488.6 2382.43   636.2 2386.05
   662.5 2384.62   685.4  2375.9   731.3 2372.52   760.9 2373.35   767.4 2375.73
   777.3 2381.02   806.8 2381.62   810.1 2383.85  823.88 2402.95   829.7 2409.24
   842.8 2415.24   859.2 2412.44   875.6 2421.66  1078.1 2445.42  1264.2 2479.23
#Mann= 4 ,-1 , 0
       0     .12       0   685.4     .04       0   767.4     .12       0
  823.88     .12       0
#XS Ineff= 2 , 0
          660.43 2386.37
Permanent Ineff=
       F       F
Bank Sta=685.4,767.4
XS Rating Curve= 0 ,0
Exp/Cntr=0.3,0.1

Type RM Length L Ch R = 1 ,13179   ,625.6,629.3,628.6
XS GIS Cut Line= 2
     2116759.379      441787.411     2117412.813      442732.933
#Sta/Elev= 30
       0 2518.52    19.6 2511.08    39.3 2498.97    68.8 2496.99   101.5 2472.28
     131 2465.58   170.3 2452.35   245.6 2400.35   275.1 2386.47     298 2381.25
   327.4 2369.12     370 2368.67   383.1 2371.96     406 2373.03   484.6  2372.3
     537 2367.89   559.9 2361.81   579.6 2359.67   638.5 2361.13   654.9 2371.03
  663.19 2371.65  715.14 2372.94   766.2 2371.82   861.2  2409.8   900.5 2428.17
  1011.8  2455.5  1060.9 2457.08  1070.8 2459.92  1123.2 2459.12  1149.3 2464.14
#Mann= 5 ,-1 , 0
       0     .12       0   559.9     .04       0   638.5     .12       0
  663.19     .12       0  715.14     .12       0
#XS Ineff= 2 , 0
          486.52 2372.05
Permanent Ineff=
       F       F
Bank Sta=559.9,638.5
XS Rating Curve= 0 ,0
Exp/Cntr=0.3,0.1

Type RM Length L Ch R = 1 ,12550   ,559.4,557.3,565.1
XS GIS Cut Line= 2
     2116154.125      442079.499     2117000.276      443118.368
#Sta/Elev= 30
       0 2607.99    65.5 2576.91      95 2566.84   134.3  2547.3   180.2  2529.8
   212.9 2515.03     285 2487.73   363.6 2463.82   412.8 2443.11   422.6  2441.3
     475 2422.11   524.2 2407.34   583.1 2396.34   710.9 2378.73   727.3 2370.38
  742.33  2353.9   763.3 2351.98   845.2 2354.08  853.89 2355.94   881.2 2359.03
   927.1 2357.53  986.75 2358.47 1024.85 2361.42  1123.6 2359.36  1146.6 2361.34
  1159.7 2365.61  1192.4 2382.36  1241.6 2420.73  1287.4 2450.61  1339.9 2467.09
#Mann= 6 ,-1 , 0
       0     .12       0  742.33     .04       0   845.2     .12       0
  853.89     .12       0  986.75     .07       0 1024.85     .12       0
#XS Ineff= 2 , 0
                           881.7         2360.64
Permanent Ineff=
       F       F
Bank Sta=742.33,845.2
XS Rating Curve= 0 ,0
Exp/Cntr=0.3,0.1

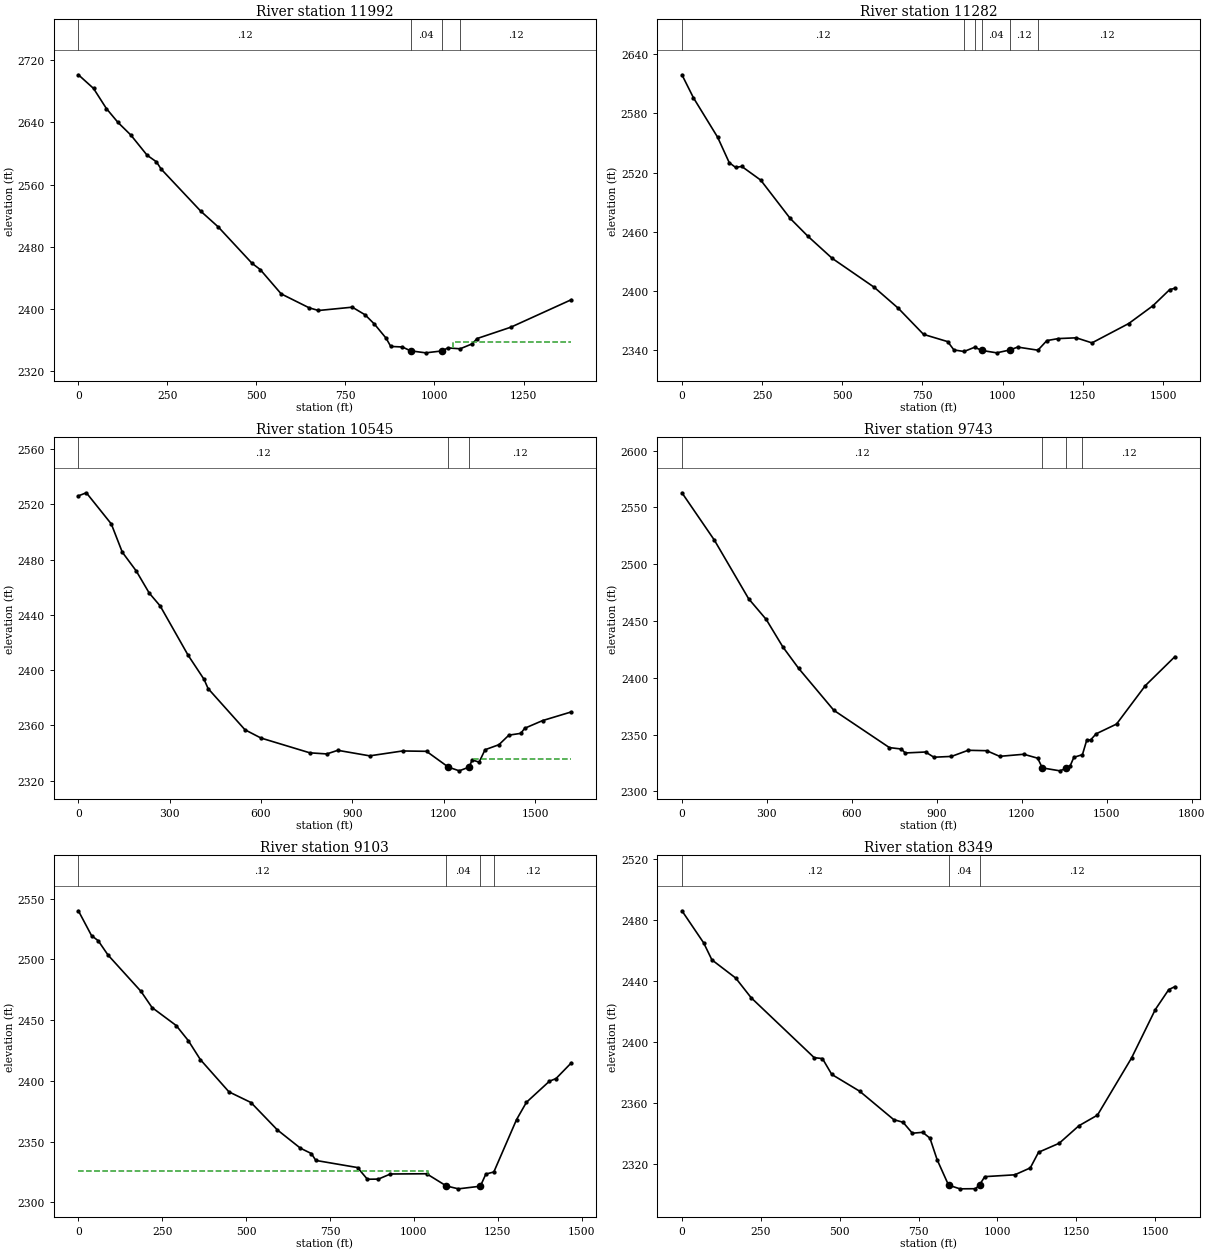
Type RM Length L Ch R = 1 ,11992   ,708.8,710.6,718.3
XS GIS Cut Line= 2
     2115694.614      442250.235      2116466.99      443399.315
#Sta/Elev= 30
       0 2701.01    42.6 2683.46    78.6 2657.68   111.3 2639.77   147.3 2623.62
   193.1 2597.66   219.3 2589.18   232.4 2579.94   343.7 2525.83   392.8 2505.61
   487.7 2458.89   510.6 2450.94   569.5 2419.65   648.1 2401.74   674.3 2398.31
   769.2 2402.56   805.2 2392.76   831.4 2380.84   864.1 2362.76   877.2 2352.15
   909.9 2351.45   932.8 2346.51   975.4 2343.93  1021.2 2346.38  1037.6 2350.26
 1072.03 2349.12  1106.3 2355.55  1119.4 2362.25  1214.3 2376.83  1384.5 2412.21
#Mann= 4 ,-1 , 0
       0     .12       0   932.8     .04       0  1021.2     .12       0
 1072.03     .12       0
#XS Ineff= 2 , 0
                         1053.04         2357.79
Permanent Ineff=
       F       F
Bank Sta=932.8,1021.2
XS Rating Curve= 0 ,0
Exp/Cntr=0.3,0.1

Type RM Length L Ch R = 1 ,11282   ,736.7,736.9,726.4
XS GIS Cut Line= 4
     2115152.595      442548.345     2115542.848      443242.129
     2115708.164      443578.181     2115906.001      443887.131
#Sta/Elev= 30
       0 2618.98      36 2595.62   111.4 2555.71   147.4 2530.11   167.1 2525.27
   186.7 2526.19   245.7 2512.36   337.4 2473.67   393.1 2455.47   468.4 2433.24
   599.5 2403.94   674.8 2382.64   753.4 2356.25   828.6 2348.93   848.1 2340.51
  879.64 2338.93  912.56 2343.19     936 2339.95   981.6 2337.57    1024 2340.58
  1046.8  2343.4 1110.06 2340.25    1138 2349.98  1173.8    2352  1229.5 2352.78
  1278.6 2347.65  1393.3 2367.25  1468.6  2385.2    1521 2401.57  1537.4 2402.92
#Mann= 6 ,-1 , 0
       0     .12       0  879.64     .04       0  912.56     .12       0
     936     .04       0    1024     .12       0 1110.06     .12       0
Bank Sta=936,1024
XS Rating Curve= 0 ,0
Exp/Cntr=0.3,0.1

Type RM Length L Ch R = 1 ,10545   ,762.7,802.2,844
XS GIS Cut Line= 3
     2114857.195      442610.677      2115011.67      443710.975
     2115263.709       444152.72
#Sta/Elev= 30
       0 2526.24    26.2 2528.47   108.2 2505.89   144.2 2485.48   190.1 2471.86
   232.7 2455.87   268.8  2446.5   360.5 2410.83     413 2393.32   426.1 2386.72
   547.4 2356.84   599.8 2350.88   760.4 2340.16   816.1 2339.36   852.2 2341.98
     957 2337.98  1065.2 2341.51  1143.7 2341.25  1215.4 2329.83  1251.3 2327.12
  1283.9 2329.88  1293.7 2335.06  1316.5  2333.4    1336  2342.4  1381.7 2346.05
  1414.3 2352.97  1453.4 2354.26  1466.4 2357.96  1525.1 2363.51  1619.7 2369.81
#Mann= 3 , 0 , 0
       0     .12       0  1215.4     .04       0  1283.9     .12       0
#XS Ineff= 2 , 0
                         1298.36         2335.43
Permanent Ineff=
       F       F
Bank Sta=1215.4,1283.9
XS Rating Curve= 0 ,0
Exp/Cntr=0.3,0.1

Type RM Length L Ch R = 1 ,9743    ,644.9,639.3,674
XS GIS Cut Line= 3
     2114769.245      442501.928     2114516.452      443561.429
     2114211.613       444137.65
#Sta/Elev= 30
       0 2562.83   114.5 2521.15   235.5 2469.54   297.7  2451.3   356.5 2427.07
   412.2 2408.22   536.4 2371.33   732.7 2338.49   775.2 2337.23   788.3 2333.76
   860.3 2334.61   889.7 2330.02   951.9 2330.73  1010.7 2336.12  1076.2 2335.76
    1122 2330.79  1207.2 2332.63  1256.3 2329.16  1272.7 2320.61  1334.9 2318.03
  1357.9 2320.46    1371 2322.44  1384.1 2329.92 1414.38  2332.3  1429.9 2345.35
    1443 2345.16  1462.7 2350.62  1534.8 2359.21  1636.3 2393.01  1741.1 2418.62
#Mann= 4 ,-1 , 0
       0     .12       0  1272.7     .04       0  1357.9     .12       0
 1414.38     .12       0
Bank Sta=1272.7,1357.9
XS Rating Curve= 0 ,0
Exp/Cntr=0.3,0.1

Type RM Length L Ch R = 1 ,9103    ,777.5,754.3,754.1
XS GIS Cut Line= 3
     2114613.108        442453.6     2114267.376      443145.064
     2113698.591      443546.559
#Sta/Elev= 30
       0 2540.09    39.3 2519.62      59 2515.48    88.4 2503.64   186.7 2473.72
   219.5 2460.44   291.5 2445.65   327.6  2433.2   363.6 2417.57   448.8 2391.02
   514.3 2382.27   592.9 2359.74   661.7 2344.67   694.5 2340.22   707.6 2334.59
   831.9 2328.72   861.3  2319.1     894 2319.22     930 2323.42  1037.8 2323.61
  1096.7 2313.56  1132.6  2311.2    1198 2313.37  1214.3 2323.34 1238.16 2325.09
  1305.9 2368.23  1335.3 2382.44  1403.9 2399.81  1423.5 2401.98  1469.3 2414.97
#Mann= 4 ,-1 , 0
       0     .12       0  1096.7     .04       0    1198     .12       0
 1238.16     .12       0
#XS Ineff= 2 , 0
         1041.74 2325.68
Permanent Ineff=
       F       F
Bank Sta=1096.7,1198
XS Rating Curve= 0 ,0
Exp/Cntr=0.3,0.1

Type RM Length L Ch R = 1 ,8349    ,418.5,378.6,334.2
XS GIS Cut Line= 4
     2114144.697      442011.212     2113661.416      442639.477
     2113438.363      442914.576     2113237.615      443278.896
#Sta/Elev= 30
       0 2486.07    68.8 2465.03      95 2453.86   170.3 2441.96   219.4 2429.02
   419.2 2389.72   445.4 2389.11   474.9 2378.72   563.4 2367.69   671.4 2349.04
   700.9 2347.32   730.4 2340.14   763.2 2340.73   786.1 2336.91     809 2322.72
   845.1 2306.09   881.2 2303.65   930.4 2303.73   943.5  2306.3   959.9 2311.65
    1055 2312.85  1104.2 2317.38  1130.4 2327.65  1195.9 2333.56  1258.2 2345.02
  1317.1    2352  1425.2 2389.49  1500.5 2421.27  1543.1 2434.35  1562.8 2436.32
#Mann= 3 , 0 , 0
       0     .12       0   845.1     .04       0   943.5     .12       0
Bank Sta=845.1,943.5
XS Rating Curve= 0 ,0
Exp/Cntr=0.3,0.1