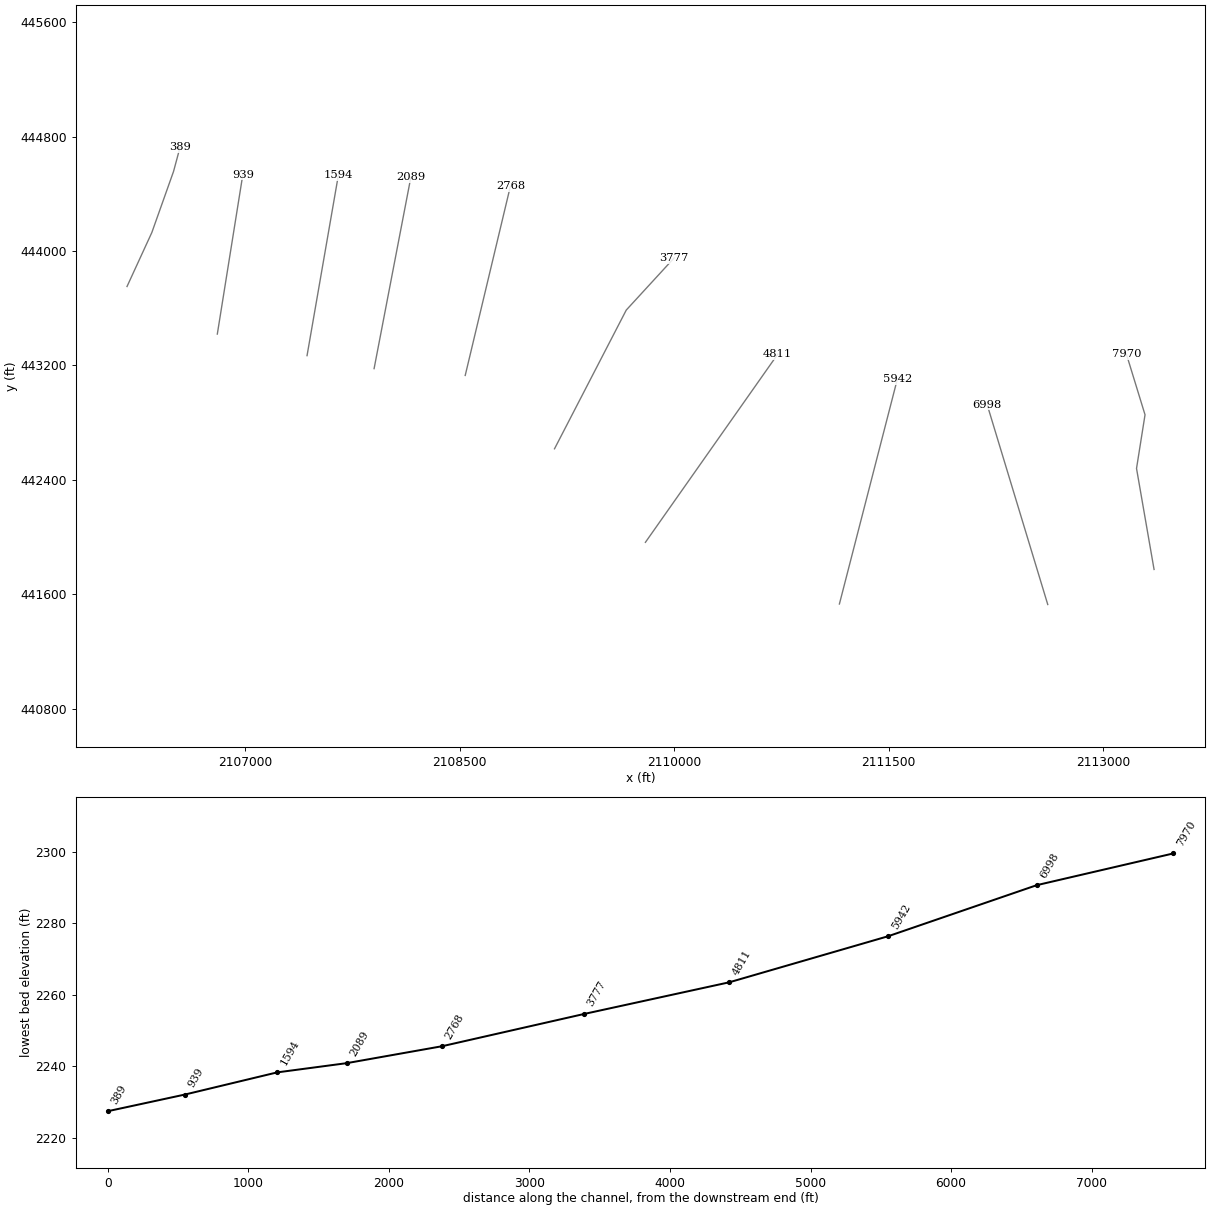
HEC-RAS study SFKCHERRYRV.prj: SFKCHERRYRV

--- SFKCHERRYRV.g01 (geometry) --- (continued)

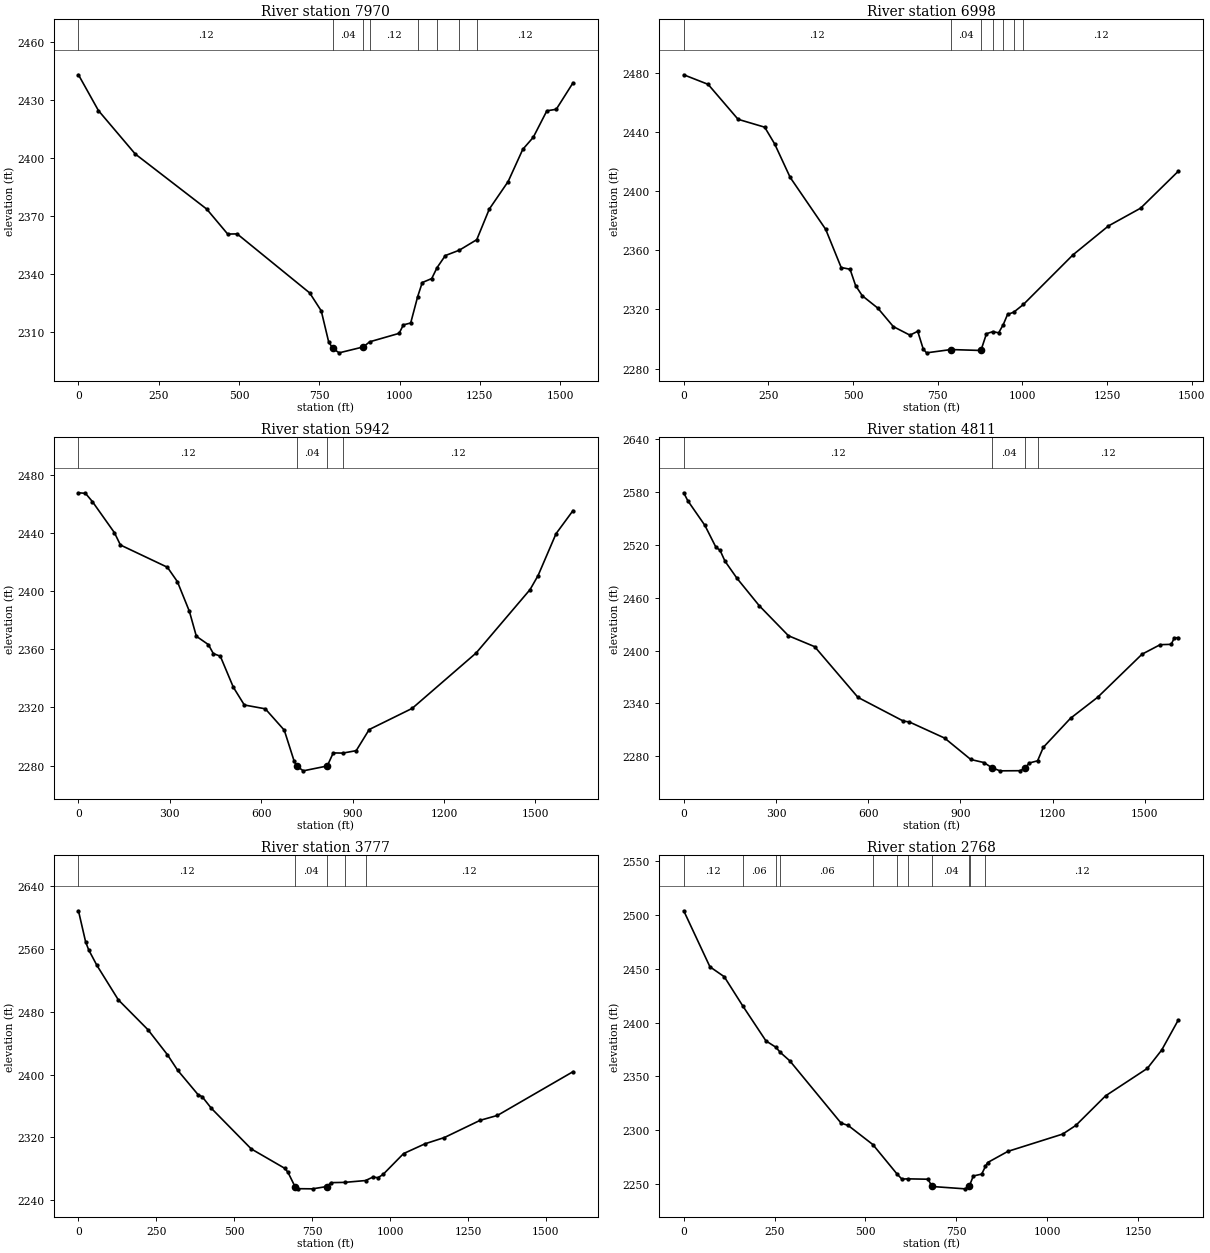
Type RM Length L Ch R = 1 ,7970    ,952.5,972.3,994
XS GIS Cut Line= 4
     2113356.577      441773.288     2113233.897      442479.623
     2113293.378      442855.095     2113163.264      443278.896
#Sta/Elev= 30
       0    2443    62.2 2424.53   176.8 2402.13   399.4  2373.7   464.8  2360.8
   494.3 2360.87   720.2 2330.41   756.2 2321.16   779.2  2305.2   792.3 2301.76
     812 2299.49   887.3 2302.55     907 2305.18   998.8 2309.55  1011.9 2313.91
  1034.8  2314.9 1056.52 2328.51  1070.8 2335.76  1100.3 2337.83 1116.97 2343.48
  1142.7  2349.7 1186.41 2352.48 1240.56 2357.89  1279.6 2373.69  1338.3  2387.9
  1383.9 2404.52  1416.5 2410.71  1458.9  2424.4  1488.2 2425.19  1540.4 2438.86
#Mann= 8 ,-1 , 0
       0     .12       0   792.3     .04       0   887.3     .12       0
     907     .12       0 1056.52     .12       0 1116.97     .06       0
 1186.41     .08       0 1240.56     .12       0
Bank Sta=792.3,887.3
XS Rating Curve= 0 ,0
Exp/Cntr=0.3,0.1

Type RM Length L Ch R = 1 ,6998    ,1084.3,1056.6,1037.2
XS GIS Cut Line= 2
     2112613.067       441527.93     2112189.266      442925.729
#Sta/Elev= 30
       0 2478.99      72 2472.51   160.5 2448.83   239.1 2443.49   268.6 2432.12
   314.4 2409.45   419.2  2374.3     465 2348.42   491.2 2347.25   507.6 2336.17
   527.3 2329.28   573.1 2320.92     619 2308.39   668.1 2302.58     691 2305.21
   707.4 2293.12   717.2 2290.61   789.3 2292.84   877.7 2292.21   894.1 2303.57
  912.89 2304.97   930.1 2304.18  943.76 2309.78   956.3 2316.61  974.62 2318.15
 1003.21  2323.4  1149.5 2356.98  1254.3 2376.58  1349.3 2388.62  1460.6 2413.65
#Mann= 7 ,-1 , 0
       0     .12       0   789.3     .04       0   877.7     .12       0
  912.89     .06       0  943.76     .12       0  974.62     .06       0
 1003.21     .12       0
Bank Sta=789.3,877.7
XS Rating Curve= 0 ,0
Exp/Cntr=0.3,0.1

Type RM Length L Ch R = 1 ,5942    ,1133.4,1130.1,1102.7
XS GIS Cut Line= 2
     2111155.788      441531.648        2111561.      443104.171
#Sta/Elev= 30
       0 2467.45      23 2467.07    45.9 2461.36   118.1 2440.02   137.8 2431.56
     292 2416.27   324.8 2406.39   364.2    2386   387.1 2368.83   426.5 2363.12
   442.9 2356.92   465.8 2355.14   508.5 2333.83   544.6  2321.6   613.5 2318.96
   675.8 2304.29   708.6 2282.76   718.4 2279.46   738.1 2276.34   816.9 2279.68
   836.6 2288.67  867.83 2288.53     912 2290.21   954.6 2304.72  1095.7 2319.26
  1305.7 2357.33  1482.8 2400.92  1509.1 2410.54  1568.1 2439.32  1623.9 2455.22
#Mann= 4 ,-1 , 0
       0     .12       0   718.4     .04       0   816.9     .12       0
  867.83     .12       0
Bank Sta=718.4,816.9
XS Rating Curve= 0 ,0
Exp/Cntr=0.3,0.1

Type RM Length L Ch R = 1 ,4811    ,1027.1,1034,1037.8
XS GIS Cut Line= 2
     2109798.882      441962.883     2110724.552      443278.896
#Sta/Elev= 30
       0 2579.26    13.1 2570.29    68.8 2542.26   104.9  2517.3     118 2514.06
   134.4 2501.47   173.7 2481.94   245.8 2450.96   340.8 2416.88     426 2404.48
   566.9 2346.89   714.4 2319.99     734 2318.97   848.7 2300.68   933.9 2276.35
   976.5 2272.88  1002.7 2266.97    1029 2263.46  1094.5 2263.61  1110.9 2266.71
    1124 2272.33  1151.2 2274.85  1169.9 2290.18  1258.3 2323.14  1346.8 2347.06
    1491 2395.92    1550 2406.74    1586 2407.13  1595.8 2414.35    1609 2414.79
#Mann= 4 ,-1 , 0
       0     .12       0  1002.7     .04       0  1110.9     .12       0
  1151.2     .12       0
Bank Sta=1002.7,1110.9
XS Rating Curve= 0 ,0
Exp/Cntr=0.3,0.1

Type RM Length L Ch R = 1 ,3777    ,980.6,1009.2,1006.4
XS GIS Cut Line= 3
     2109163.181      442617.172      2109665.05      443587.452
      2109999.63      443951.772
#Sta/Elev= 30
       0 2608.38      23  2568.8    32.8  2558.7      59 2539.04   127.9 2495.09
   223.1 2457.02   285.4 2425.29   318.2 2405.54   383.8 2374.44   396.9 2371.86
   426.5 2357.04   554.4  2305.4   662.6 2280.56   672.5 2275.46   695.5 2256.91
   705.3 2254.78   751.2 2254.59   797.2 2257.54   810.3 2262.47  854.63 2262.82
  921.13 2265.14   944.8 2269.54   961.2 2268.74   977.6 2272.96  1043.2 2299.44
    1112 2311.89  1174.3 2319.88  1288.9 2341.76  1344.6 2348.03    1587 2403.66
#Mann= 5 ,-1 , 0
       0     .12       0   695.5     .04       0   797.2     .12       0
  854.63     .06       0  921.13     .12       0
Bank Sta=695.5,797.2
XS Rating Curve= 0 ,0
Exp/Cntr=0.3,0.1

Type RM Length L Ch R = 1 ,2768    ,675.9,679.5,681.5
XS GIS Cut Line= 2
     2108538.633      443130.194     2108854.625      444453.641
#Sta/Elev= 30
       0 2503.98    72.1 2451.91   111.5  2442.7  161.89 2415.84   226.2 2383.06
  252.99 2377.29  265.95 2372.28   291.8 2364.54   432.8 2306.69   452.5 2304.46
  520.32 2286.72  587.02  2259.3     600 2254.68  617.39 2254.86   672.1 2254.52
  683.06 2247.76   773.8 2245.58  785.39 2247.92   786.9 2249.22   796.7 2257.52
   819.7 2259.29  829.96 2266.37   836.1 2270.02   891.8  2280.4  1042.6 2296.48
  1078.7 2304.52  1160.6 2332.02  1275.4 2357.51  1314.8  2374.5  1360.6 2402.47
#Mann= 11 ,-1 , 0
       0     .12       0  161.89     .06       0  252.99     .12       0
  265.95     .06       0  520.32     .12       0  587.02     .06       0
  617.39     .12       0  683.06     .04       0  785.39     .12       0
   786.9     .04       0  829.96     .12       0
Bank Sta=683.06,785.39
XS Rating Curve= 0 ,0
Exp/Cntr=0.3,0.1

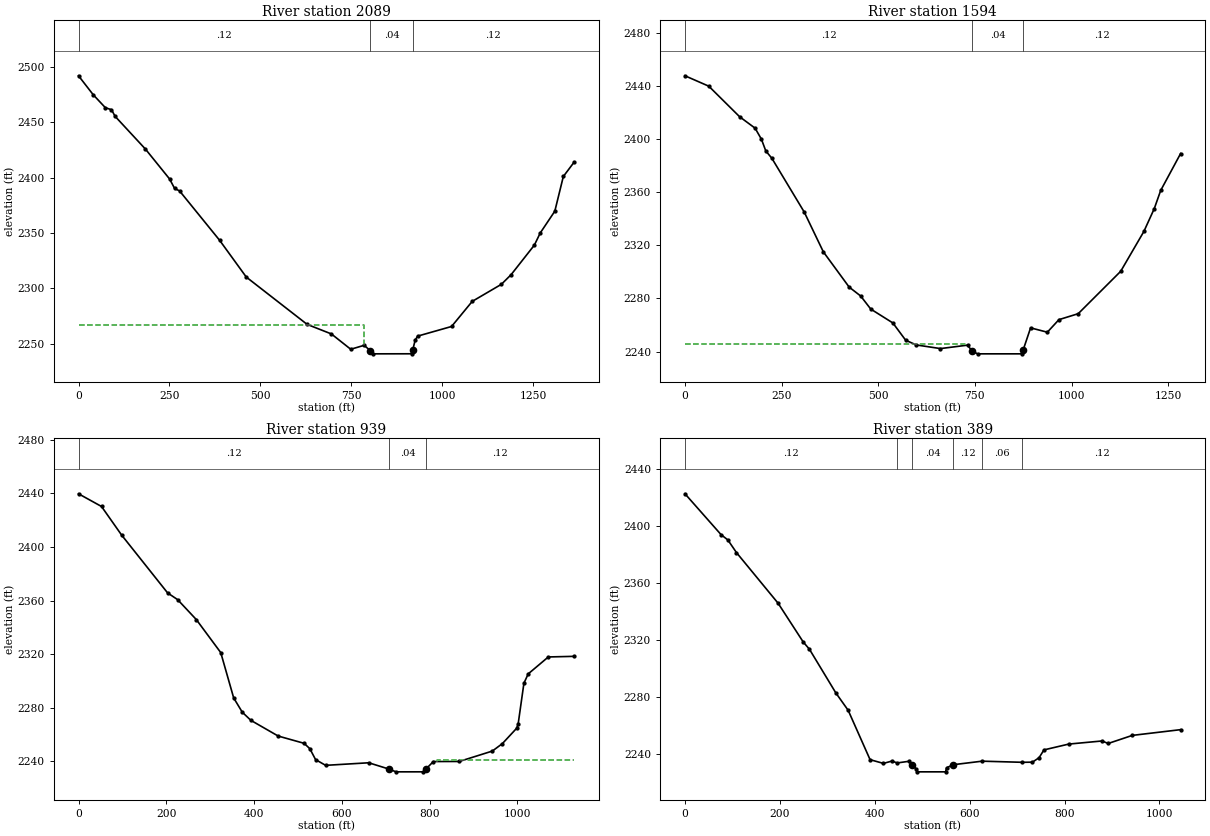
Type RM Length L Ch R = 1 ,2089    ,494.4,494.3,495.4
XS GIS Cut Line= 2
2107901.29702206443177.8327249382108158.47794945444516.686376337
#Sta/Elev= 30
       0 2491.87    40.6 2474.69      74 2463.01    90.7 2461.25   100.7 2455.24
   184.2 2425.64   250.6 2398.66   264.4 2390.11   277.8 2387.97     388 2343.39
   461.5 2310.14   628.9 2267.41   695.4 2258.83   748.8 2244.97   785.6 2248.53
   802.7  2243.7   808.9 2240.84   915.9 2240.89   919.2 2244.29   925.9 2253.05
   932.6 2256.82  1026.1 2265.54  1082.9 2288.19  1163.1 2303.61  1189.8 2312.28
  1253.9 2339.03    1270 2349.96  1310.1 2369.64  1333.5 2400.96  1363.3 2413.95
#Mann= 3 , 0 , 0
       0     .12       0   802.7     .04       0   919.2     .12       0
#XS Ineff= 2 , 0
          786.21 2266.96
Permanent Ineff=
       F       F
Bank Sta=802.7,919.2
XS Rating Curve= 0 ,0
Exp/Cntr(USF)=0,0
Exp/Cntr=0.3,0.1

Type RM Length L Ch R = 1 ,1594    ,655.7,655.6,656.8
XS GIS Cut Line= 2
2107432.32003682443268.602464016 2107651.6802396444531.814666184
#Sta/Elev= 30
       0 2447.47    61.6 2439.64   141.4 2416.64   181.4 2408.04   197.7 2399.76
   209.1 2390.89   224.7 2385.42   308.4 2344.97   357.9    2315   424.7 2288.47
   454.4 2281.79   480.6 2271.93   537.7 2261.51     571 2248.45   598.7 2244.93
   660.9 2242.22   730.8 2244.79  742.36 2240.52   756.7 2238.26   870.7 2238.26
  874.41 2240.84     894 2257.81   937.3 2254.53   967.3 2263.99  1017.2 2268.47
  1127.1 2300.37    1187 2330.32    1214 2347.58  1230.5 2361.17  1282.1 2388.99
#Mann= 3 , 0 , 0
       0     .12       0  742.36     .04       0  874.41     .12       0
#XS Ineff= 2 , 0
          723.76 2245.72
Permanent Ineff=
       F       F
Bank Sta=742.36,874.41
XS Rating Curve= 0 ,0
Exp/Cntr(USF)=0,0
Exp/Cntr=0.3,0.1

Type RM Length L Ch R = 1 ,939     ,555,550,539.7
XS GIS Cut Line= 2
     2106804.801      443419.602     2106983.243      444534.867
#Sta/Elev= 30
       0 2439.76    52.4 2430.28    98.2 2408.93     203 2365.72   225.9 2360.68
   268.4 2345.81   324.1 2321.14   353.6 2287.24   373.2  2276.6   392.8 2270.52
     455  2258.8     514 2253.38   527.1 2249.35   540.2  2241.2   563.1 2236.92
   661.3 2238.84   707.1 2234.17   723.5 2232.07   785.7 2232.08   792.2 2234.38
   808.6 2239.76   867.6 2239.82   942.8 2247.57   965.8 2253.14   998.5 2264.68
  1001.8 2267.87  1014.9 2298.26  1024.7 2305.24  1070.5 2317.88  1129.4 2318.34
#Mann= 3 , 0 , 0
       0     .12       0   707.1     .04       0   792.2     .12       0
#XS Ineff= 2 , 0
                          816.52          2241.1
Permanent Ineff=
       F       F
Bank Sta=707.1,792.2
XS Rating Curve= 0 ,0
Exp/Cntr=0.3,0.1

Type RM Length L Ch R = 1 ,389     ,398.9,388.7,378.6
BEGIN DESCRIPTION:
Channel burnt to match with the effective
END DESCRIPTION:
XS GIS Cut Line= 4
2106173.23701984443752.3038795292106346.84813094444129.908046171
2106498.75785318 444557.425407292106544.33076987444726.696240619
#Sta/Elev= 30
       0 2422.69      76 2394.01    90.4 2390.25   108.5 2381.39   196.3  2345.8
   249.3 2318.55   262.3 2313.51   317.9 2282.85   343.9 2270.63   390.1 2235.95
   418.2 2233.33   436.2 2234.97   447.3 2233.65   471.1 2234.77   479.4 2232.43
   487.6 2229.21   488.5  2227.4   549.2  2227.4   551.2 2230.22   565.1  2232.4
   626.3 2234.89   711.1  2234.1   732.3  2234.2   746.2 2237.31   756.6 2242.82
   808.9  2246.9     879 2249.08   891.9 2247.32   942.8    2253  1044.6 2257.03
#Mann= 6 ,-1 , 0
       0     .12       0   447.3     .12       0   479.4     .04       0
   565.1     .12       0   626.3     .06       0   711.1     .12       0
Bank Sta=479.4,565.1
XS Rating Curve= 0 ,0
Exp/Cntr=0.3,0.1
LCMann Table=0

Chan Stop Cuts=-1
Use User Specified Reach Order=0
Composite Channel Slope=5